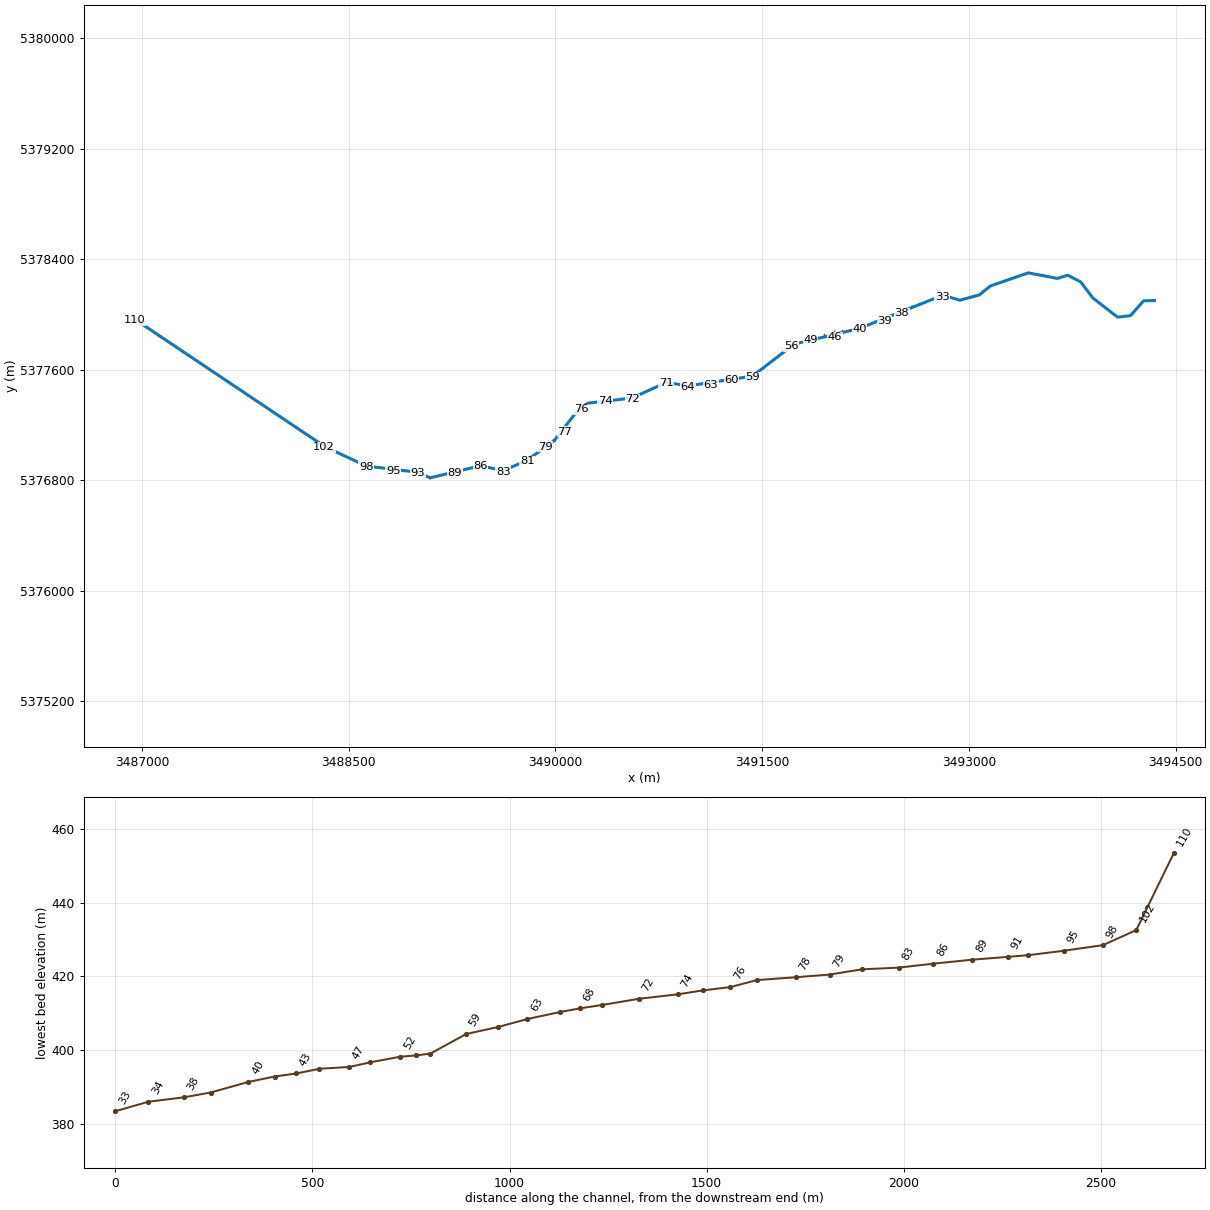
--- Amm_final.prj (project) ---

Proj Title=Amm_final
Current Plan=p07
Default Exp/Contr=0.3,0.1
SI Units
Geom File=g04
Flow File=f01
QuasiSteady File=q03
Sediment File=s03
Plan File=p07
Y Axis Title=Elevation
X Axis Title(PF)=Main Channel Distance
X Axis Title(XS)=Station
BEGIN DESCRIPTION:
END DESCRIPTION:
DSS Export Rating Curves= 0
DSS Export Rating Curve Sorted= 0
DSS Export Volume Flow Curves= 0
DXF Filename=..\Prj_lessXS\Amm_less_XS_100m.
DXF OffsetX= 0
DXF OffsetY= 0
DXF ScaleX= 1
DXF ScaleY= 10

--- Amm_final.p07 (plan) ---

Plan Title=Amm_final
Program Version=5.00
Short Identifier=Amm_final
Simulation Date=01JAN2013,0000,31DEC2016,2300
Geom File=g04
Flow File=q03
Sediment File=s03
Subcritical Flow
K Sum by GR= 0
Std Step Tol= 0.003
Critical Tol= 0.003
Num of Std Step Trials= 20
Max Error Tol= 0.1
Flow Tol Ratio= 0.001
Split Flow NTrial= 30
Split Flow Tol= 0.006
Split Flow Ratio= 0.02
Log Output Level= 0
Friction Slope Method= 1
Unsteady Friction Slope Method= 2
Unsteady Bridges Friction Slope Method= 1
Parabolic Critical Depth
Global Vel Dist= 0 , 0 , 0
Global Log Level= 0
CheckData=True
Encroach Param=-1 ,0,0, 0
Computation Interval=1MIN
Output Interval=1HOUR
Instantaneous Interval=1HOUR
Mapping Interval=1HOUR
Run HTab= 0
Run UNet= 0
Run Sediment= 0
Run PostProcess= 0
Run WQNet= 0
Run RASMapper= 0
UNET Theta= 1
UNET Theta Warmup= 1
UNET ZTol= 0.006
UNET ZSATol= 0.006
UNET MxIter= 20
UNET Max Iter WO Improvement= 0
UNET MaxInSteps= 0
UNET DtIC= 0
UNET DtMin= 0
UNET MaxCRTS= 20
UNET WFStab= 2
UNET SFStab= 1
UNET WFX= 1
UNET SFX= 1
UNET DSS MLevel= 4
UNET Pardiso=0
UNET DZMax Abort= 30
UNET Use Existing IB Tables=-1
UNET Froude Reduction=False
UNET Froude Limit= 0.8
UNET Froude Power= 4
UNET Time Slicing=0,0, 5
UNET Junction Losses=0
UNET D1 Cores= 0
UNET D2 Coriolis=0
UNET D2 Cores= 0
UNET D2 Theta= 1
UNET D2 Theta Warmup= 1
UNET D2 Z Tol= 0.003
UNET D2 Volume Tol= 0.003
UNET D2 Max Iterations= 20
UNET D2 Equation= 0
UNET D2 RampUpFraction=0.1
UNET D2 TimeSlices= 1
UNET D2 BCVolumeCheck=0
UNET D1D2 MaxIter= 0
UNET D1D2 ZTol=0.003
UNET D1D2 QTol=0.1
UNET D1D2 MinQTol=0.03
Write IC File= 0
Write IC File at Fixed DateTime=0
Write IC File at Sim End=0
Echo Input=False
Echo Parameters=False
Echo Output=False
Write Detailed= 0
HDF Write Warmup=0
HDF Write Time Slices=0
HDF Flush=0
HDF Face Node Velocities=0
HDF Compression= 1
HDF Chunk Size= 1
HDF Spatial Parts= 1
HDF Use Max Rows=0
HDF Fixed Rows= 1
Calibration Method= 0
Calibration Iterations= 20
Calibration Max Change=0.05
Calibration Tolerance=0.2
Calibration Maximum=1.5
Calibration Minimum=0.5
Calibration Optimization Method= 1
WQ AD Non Conservative
WQ ULTIMATE=-1
WQ Max Comp Step=1HOUR
WQ Output Interval=15MIN
WQ Output Selected Increments= 0
WQ Output face flow=0
WQ Output face velocity=0
WQ Output face area=0
WQ Output face dispersion=0
WQ Output cell volume=0
WQ Output cell surface area=0
WQ Output cell continuity=0
WQ Output cumulative cell continuity=0
WQ Output face conc=0
WQ Output face dconc_dx=0
WQ Output face courant=0
WQ Output face peclet=0
WQ Output face adv mass=0
WQ Output face disp mass=0
WQ Output cell mass=0
WQ Output cell source sink temp=0
WQ Output nsm pathways=0
WQ Output nsm derived pathways=0
WQ Output MaxMinRange=-1
WQ Daily Max Min Mean=-1
WQ Daily Range=0
WQ Daily Time=0
WQ Create Restart=0
WQ Fixed Restart=0
WQ System Summary=0
WQ Write To DSS=0
WQ Use Fixed Temperature=0
Sorting and Armoring Iterations= 10
XS Update Threshold= 0.02
Bed Roughness Predictor= 0
Hydraulics Update Threshold= 0.02
Energy Slope Method= 1
Volume Change Method= 1
Sediment Retention Method= 0
XS Weighting Method= 0
Number of US Weighted Cross Sections= 1
Number of DS Weighted Cross Sections= 1
Upstream XS Weight=0
Main XS Weight=1
Downstream XS Weight=0
Number of DS XS's Weighted with US Boundary= 1
Upstream Boundary Weight= 1
Weight of XSs Associated with US Boundary= 0
Number of US XS's Weighted with DS Boundary= 1
Downstream Boundary Weight= 0.5
Weight of XSs Associated with DS Boundary= 0.5
Percentile Method= 0
Sediment Output Level= 4
Mass or Volume Output= 0
Output Increment Type= 1
Profile and TS Output Increment= 1
XS Output Flag= 0
XS Output Increment= 10
Write Gradation File= 0
Read Gradation Hotstart= 0
Write HDF5 File= 1
Write DSS Sediment File= 0
SV Curve= 0
Specific Gage Flag= 0

--- Amm_final.f01 (steady flow) ---

Flow Title=flow_steady
Program Version=5.00
Number of Profiles= 1
Profile Names=PF 1
River Rch & RM=Ammer,UpperAmmer      ,243
       1
River Rch & RM=Ammer,MiddleAmmer     ,69.3
       1
River Rch & RM=Ammer,LowerAmmer      ,11
       1
River Rch & RM=Kasbach,KasAmmer        ,109
       1
River Rch & RM=Kochhartgraben,KochAmmer       ,110
       1
Boundary for River Rch & Prof#=Ammer,UpperAmmer      , 1
Up Type= 0
Dn Type= 0
Boundary for River Rch & Prof#=Ammer,MiddleAmmer     , 1
Up Type= 0
Dn Type= 0
Boundary for River Rch & Prof#=Ammer,LowerAmmer      , 1
Up Type= 0
Dn Type= 2
Boundary for River Rch & Prof#=Kasbach,KasAmmer        , 1
Up Type= 0
Dn Type= 0
Boundary for River Rch & Prof#=Kochhartgraben,KochAmmer       , 1
Up Type= 0
Dn Type= 0
DSS Import GetInterval= 0
DSS Import GetPeak= 0
DSS Import FillOption= 0

--- Amm_final.g04 (geometry) ---

Geom Title=Amm_final
Program Version=5.00

Junct Name=KochToAmm
Junct Desc=, 0 , 0 ,-1 ,0
Up River,Reach=Ammer           ,UpperAmmer
Up River,Reach=Kochhartgraben  ,KochAmmer
Dn River,Reach=Ammer           ,MiddleAmmer
Junc L&A=10.756,0
Junc L&A=36.66,0

Junct Name=KasToAmm
Junct Desc=, 0 , 0 ,-1 ,0
Up River,Reach=Ammer           ,MiddleAmmer
Up River,Reach=Kasbach         ,KasAmmer
Dn River,Reach=Ammer           ,LowerAmmer
Junc L&A=32.98,0
Junc L&A=37.85,0

River Reach=Kochhartgraben  ,KochAmmer
Reach XY= 30
3486952.176622665377961.203581673488326.029999385377042.20999924
3488627.400000075376901.330000213489002.699999985376856.04999993
3489089.600551135376816.06751669      3489456.22      5376903.36
3489620.463167465376868.521747363489791.584347645376940.88278916
3489991.770331395377086.894730963490175.532123695377322.50881729
3490237.187343045377356.647062643490556.01999994 5377394.3800002
3490803.091110065377506.227612553490964.538355555377482.70919928
3491430.099999935377552.800000163491731.039999995377784.14000008
3492203.49010948 5377897.65656783492811.669999975378138.87999972
3492934.979999915378102.249999913493076.509999895378141.44000005
3493156.279999975378205.790000043493430.962121115378300.60825411
3493641.680000015378260.330000133493717.71000001 5378283.4099999
 3493811.00999995378235.36999995 3493898.87965785378119.03922373
3494078.771871435377979.734544573494172.769999495377991.05000017
  3494267.6930945378097.799559593494346.195783445378100.06183718

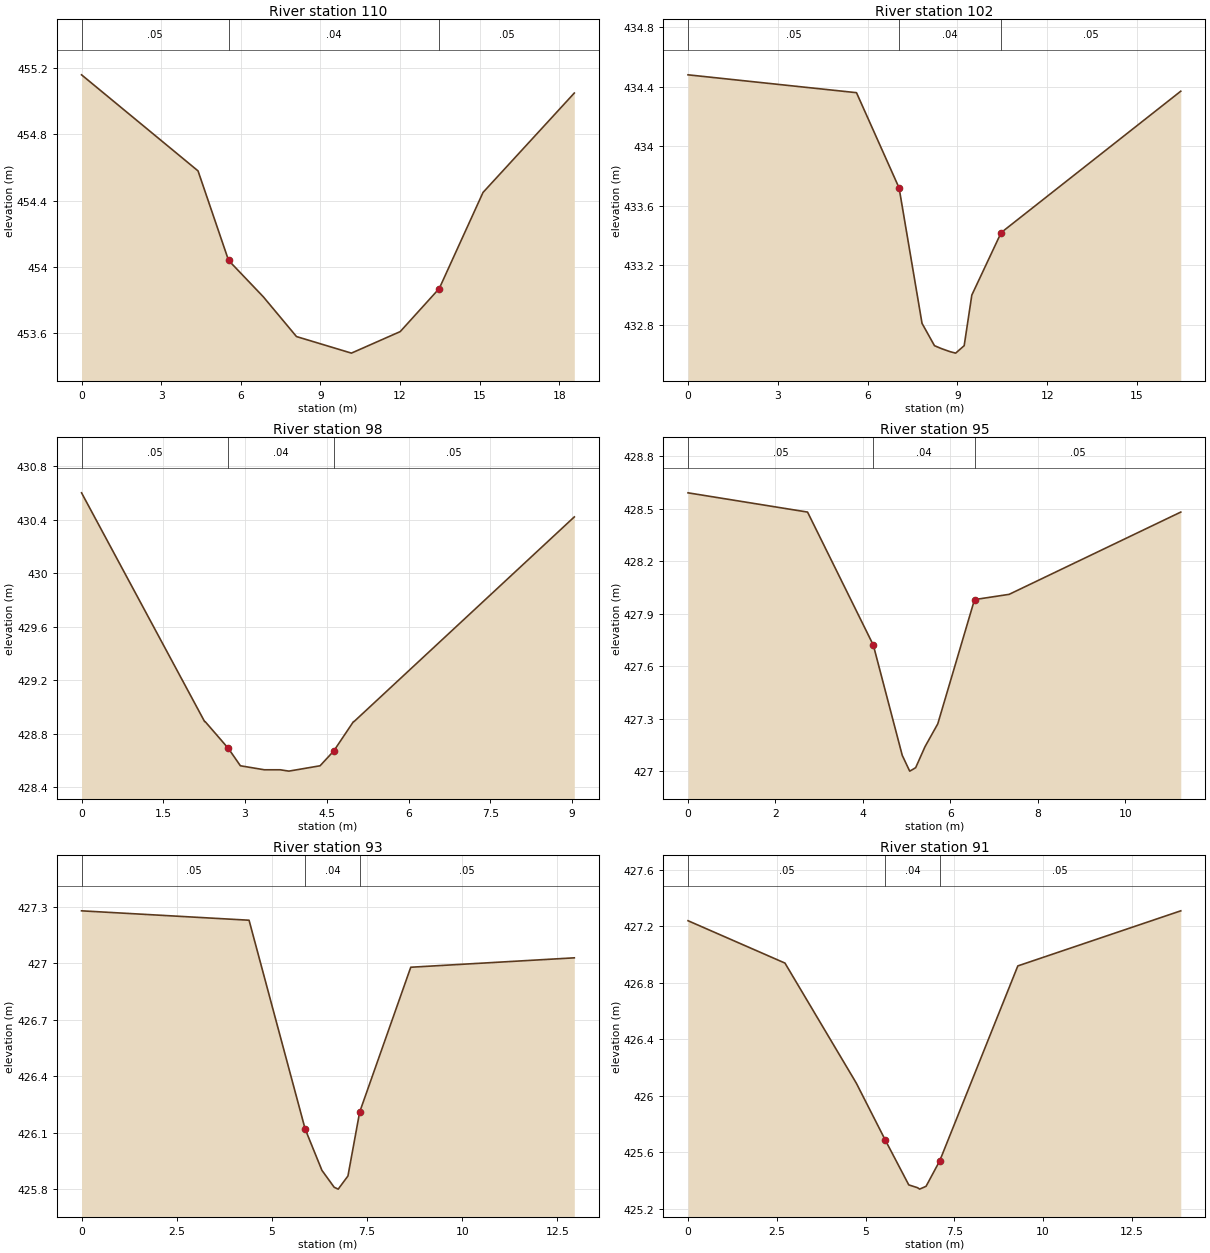
Type RM Length L Ch R = 1 ,110     ,94.882,94.882,94.882
XS GIS Cut Line= 6
      3486959.89     5377967.741      3486958.62     5377966.894
      3486955.98     5377964.566      3486954.58      5377963.17
      3486947.62     5377957.5813486945.662867165377955.84519736
#Sta/Elev= 10
       0  455.16    4.39  454.58    5.54  454.04    6.85  453.82     8.1  453.58
   10.17  453.48   12.01  453.61   13.48  453.87   15.13  454.45   18.57  455.05
#Mann= 3 , 0 , 0
       0     .05       0    5.54     .04       0   13.48     .05       0
Bank Sta=5.54,13.48
XS Rating Curve= 0 ,0
Exp/Cntr=0.3,0.1

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
Type RM Length L Ch R = 1 ,102     ,84.677,84.677,84.677
XS GIS Cut Line= 6
      3488331.42      5377049.33      3488328.04      5377044.83
      3488326.65      5377043.14      3488325.68       5377041.8
      3488325.19      5377040.953488321.436268985377036.27028228
#Sta/Elev= 12
       0  434.48   5.628  434.36   7.051  433.72   7.817  432.81   8.233  432.66
    8.47  432.64    8.75  432.62    8.94  432.61   9.225  432.66    9.48     433
  10.461  433.42   16.46  434.37
#Mann= 3 , 0 , 0
       0     .05       0   7.051     .04       0  10.461     .05       0
Bank Sta=7.051,10.461
XS Rating Curve= 0 ,0
Exp/Cntr=0.3,0.1

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
Type RM Length L Ch R = 1 ,98      ,98.64,98.64,98.64
XS GIS Cut Line= 6
      3488628.59      5376904.88      3488627.53      5376902.42
      3488627.53      5376901.76       3488627.4      5376901.33
      3488627.35      5376900.763488627.196061085376896.11071414
#Sta/Elev= 13
       0   430.6   2.258  428.89   2.268  428.89   2.693  428.69   2.914  428.56
   3.355  428.53   3.646  428.53   3.804  428.52   4.376  428.56   4.626  428.67
   4.988  428.89   4.998  428.89    9.04  430.42
#Mann= 3 , 0 , 0
       0     .05       0   2.693     .04       0   4.626     .05       0
Bank Sta=2.693,4.626
XS Rating Curve= 0 ,0
Exp/Cntr=0.3,0.1

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
Type RM Length L Ch R = 1 ,95      ,90.395,90.395,90.395
XS GIS Cut Line= 6
      3488823.42      5376879.55      3488822.93      5376876.86
      3488822.83      5376875.36      3488822.89       5376874.7
      3488822.89      5376873.083488822.710888115376868.36698486
#Sta/Elev= 12
       0  428.59   2.734  428.48   4.238  427.72     4.9  427.09    5.07     427
   5.143  427.01   5.207  427.02   5.421  427.14   5.712  427.27   6.553  427.98
   7.345  428.01   11.27  428.48
#Mann= 3 , 0 , 0
       0     .05       0   4.238     .04       0   6.553     .05       0
Bank Sta=4.238,6.553
XS Rating Curve= 0 ,0
Exp/Cntr=0.3,0.1

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
Type RM Length L Ch R = 1 ,93      ,51.02,51.02,51.02
XS GIS Cut Line= 6
      3489003.89      5376862.62      3489002.83      5376858.35
       3489002.7      5376856.05      3489002.43      5376855.56
      3489002.25      5376854.23      3489000.61      5376850.26
#Sta/Elev= 10
       0  427.28     4.4  427.23   5.873  426.12   6.314   425.9   6.636  425.81
   6.742   425.8   6.998  425.87   7.306  426.21   8.648  426.98  12.944  427.03
#Mann= 3 , 0 , 0
       0     .05       0   5.873     .04       0   7.306     .05       0
Bank Sta=5.873,7.306
XS Rating Curve= 0 ,0
Exp/Cntr=0.3,0.1

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
Type RM Length L Ch R = 1 ,91      ,91.04,91.04,91.04
XS GIS Cut Line= 6
      3489088.66       5376822.3      3489089.35      5376817.61
      3489089.74      5376815.69      3489089.92      5376815.35
      3489090.28      5376813.183489090.951372025376808.63836574
#Sta/Elev= 11
       0  427.24   2.731  426.94   4.741  426.09   5.551  425.69   6.218  425.37
   6.466  425.35   6.524  425.34   6.705  425.36    7.09  425.54    9.29  426.92
   13.88  427.31
#Mann= 3 , 0 , 0
       0     .05       0   5.551     .04       0    7.09     .05       0
Bank Sta=5.551,7.09
XS Rating Curve= 0 ,0
Exp/Cntr=0.3,0.1

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
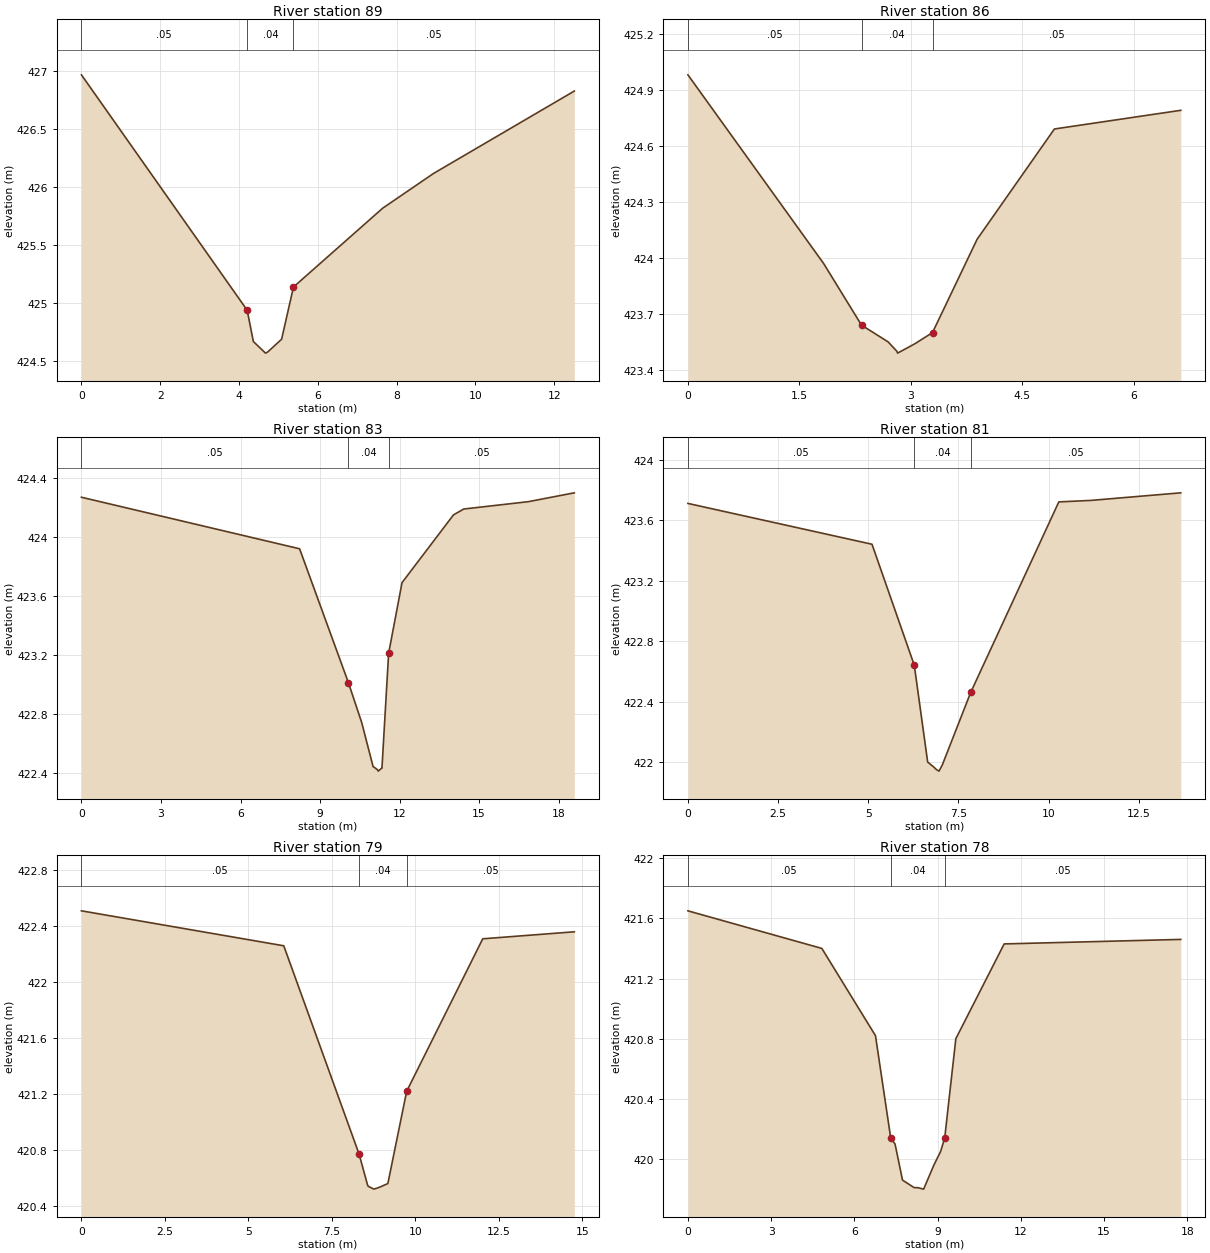
Type RM Length L Ch R = 1 ,89      ,98.48,98.48,98.48
XS GIS Cut Line= 6
      3489265.97      5376860.23      3489267.18      5376856.04
      3489267.28      5376855.05      3489267.99       5376852.9
      3489268.46      5376851.193489268.953857855376848.13970154
#Sta/Elev= 10
       0  426.97   4.207  424.94   4.364  424.67   4.672  424.57   4.729  424.58
   5.081  424.69   5.382  425.14   7.647  425.82    8.94  426.12   12.51  426.83
#Mann= 3 , 0 , 0
       0     .05       0   4.207     .04       0   5.382     .05       0
Bank Sta=4.207,5.382
XS Rating Curve= 0 ,0
Exp/Cntr=0.3,0.1

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
Type RM Length L Ch R = 1 ,86      ,88.33,88.33,88.33
XS GIS Cut Line= 6
      3489456.52      5376906.14      3489456.35      5376903.81
      3489456.06      5376902.92      3489456.03      5376902.32
      3489455.71      5376901.33      3489455.39      5376899.66
#Sta/Elev= 11
       0  424.98   1.827  423.97   2.337  423.64   2.696  423.55   2.813   423.5
   2.823  423.49   3.055  423.54   3.293   423.6   3.894   424.1   4.934  424.69
   6.635  424.79
#Mann= 3 , 0 , 0
       0     .05       0   2.337     .04       0   3.293     .05       0
Bank Sta=2.337,3.293
XS Rating Curve= 0 ,0
Exp/Cntr=0.3,0.1

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
Type RM Length L Ch R = 1 ,83      ,93.65,93.65,93.65
XS GIS Cut Line= 6
      3489618.56       5376879.1      3489619.62      5376870.94
      3489620.42      5376869.28      3489620.82      5376865.38
      3489620.83       5376862.43489621.198598215376860.86583448
#Sta/Elev= 16
       0  424.27   8.229  423.92  10.071  423.01  10.571  422.74  11.002  422.44
  11.012  422.44  11.164  422.42  11.195  422.41  11.325  422.43  11.335  422.43
  11.587  423.21  12.092  423.69  14.032  424.15   14.42  424.19   16.86  424.24
   18.59   424.3
#Mann= 3 , 0 , 0
       0     .05       0  10.071     .04       0  11.587     .05       0
Bank Sta=10.071,11.587
XS Rating Curve= 0 ,0
Exp/Cntr=0.3,0.1

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
Type RM Length L Ch R = 1 ,81      ,81.295,81.295,81.295
XS GIS Cut Line= 6
      3489788.07       5376946.9      3489790.55      5376942.44
      3489791.59      5376941.01      3489791.95      5376940.14
      3489793.55      5376937.21      3489794.56      5376934.94
#Sta/Elev= 12
       0  423.71   5.103  423.44   6.275  422.64   6.646     422     6.8  421.97
    6.89  421.95    6.96  421.94    7.05  421.98   7.838  422.46  10.281  423.72
  11.177  423.73  13.661  423.78
#Mann= 3 , 0 , 0
       0     .05       0   6.275     .04       0   7.838     .05       0
Bank Sta=6.275,7.838
XS Rating Curve= 0 ,0
Exp/Cntr=0.3,0.1

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
Type RM Length L Ch R = 1 ,79      ,85.41,85.41,85.41
XS GIS Cut Line= 6
      3489913.03      5377048.74      3489916.69      5377043.91
      3489918.46      5377042.51      3489919.21      5377041.46
      3489921.47      5377041.17      3489923.93      5377039.96
#Sta/Elev= 12
       0  422.51    6.06  422.26   8.317  420.77   8.569  420.55   8.591  420.54
    8.76  420.52    8.89  420.53    8.99  420.54   9.178  420.56   9.742  421.22
   12.02  422.31  14.762  422.36
#Mann= 3 , 0 , 0
       0     .05       0   8.317     .04       0   9.742     .05       0
Bank Sta=8.317,9.742
XS Rating Curve= 0 ,0
Exp/Cntr=0.3,0.1

Type RM Length L Ch R = 1 ,78      ,99.54,99.54,99.54
XS GIS Cut Line= 6
      3489985.15      5377091.68      3489991.03      5377087.38
      3489992.65      5377086.45      3489993.05      5377086.47
      3489994.53      5377085.55      3489999.73      5377081.88
#Sta/Elev= 15
       0  421.65   4.828   421.4   6.761  420.82    7.31  420.14   7.466   420.1
   7.735  419.86   8.154  419.81   8.276  419.81   8.496   419.8   8.866  419.96
   9.108  420.05   9.256  420.14   9.657   420.8  11.399  421.43  17.764  421.46
#Mann= 3 , 0 , 0
       0     .05       0    7.31     .04       0   9.256     .05       0
Bank Sta=7.31,9.256
XS Rating Curve= 0 ,0
Exp/Cntr=0.3,0.1

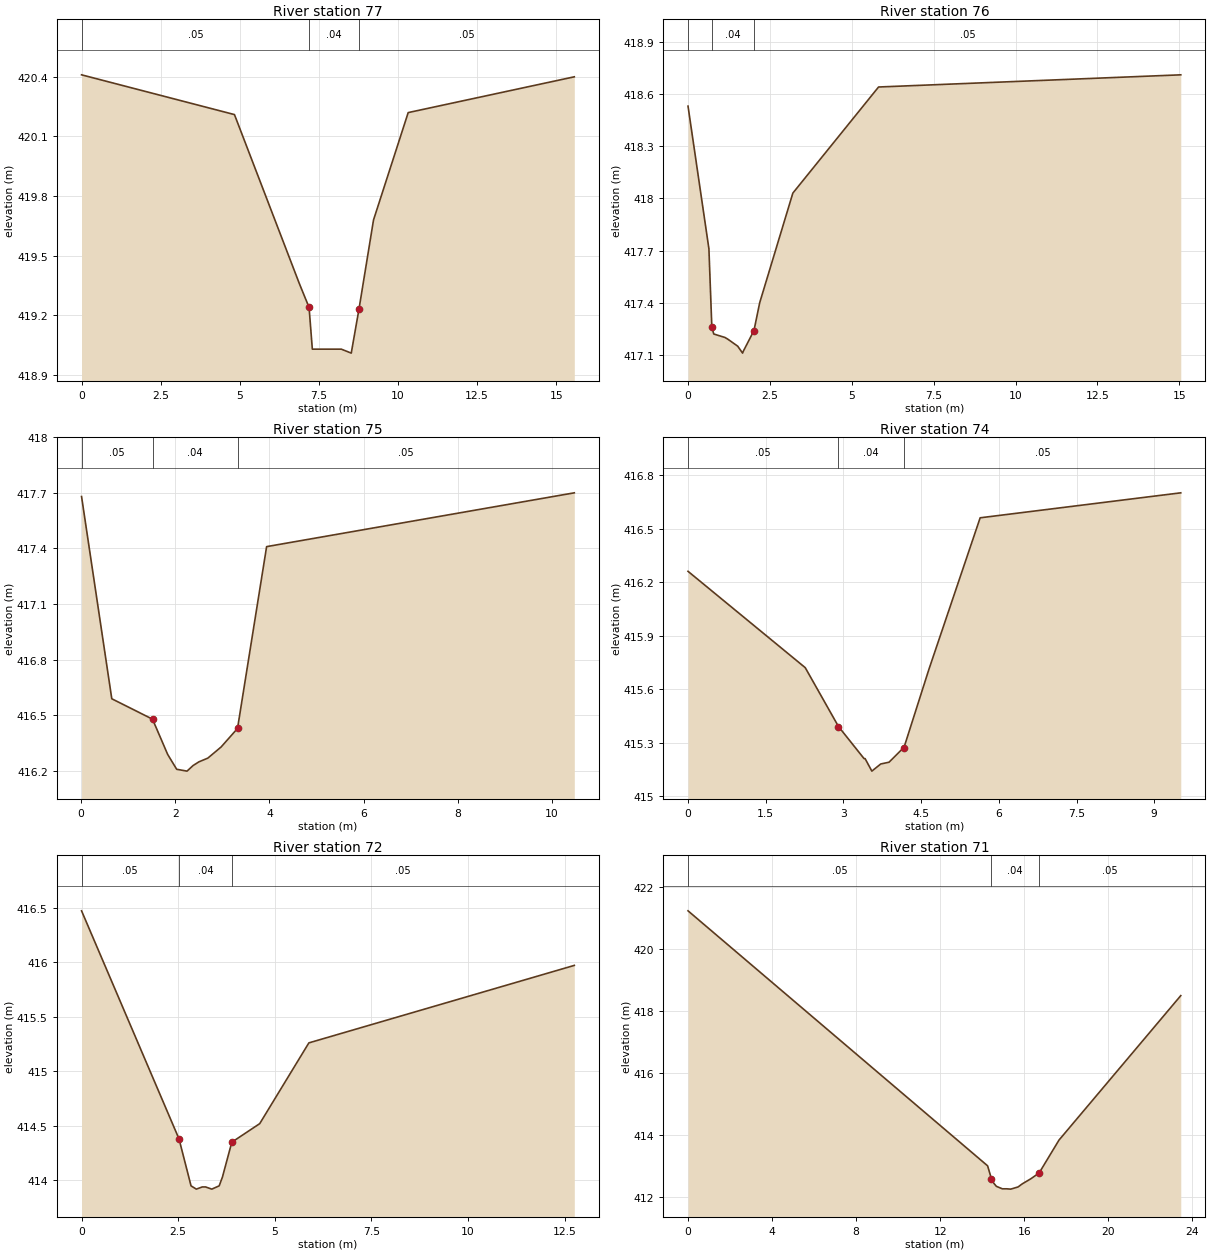
Type RM Length L Ch R = 1 ,77      ,67.36,67.36,67.36
XS GIS Cut Line= 6
      3490056.71      5377161.55      3490061.91      5377157.04
      3490062.57      5377156.73       3490063.1      5377156.21
      3490063.22      5377155.54      3490067.37      5377150.74
#Sta/Elev= 12
       0  420.41   4.833  420.21   6.883  419.36   7.191  419.24   7.294  419.03
    8.21  419.03   8.525  419.01   8.535  419.02   8.767  419.23   9.228  419.68
  10.324  420.22  15.574   420.4
#Mann= 3 , 0 , 0
       0     .05       0   7.191     .04       0   8.767     .05       0
Bank Sta=7.191,8.767
XS Rating Curve= 0 ,0
Exp/Cntr=0.3,0.1

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
Type RM Length L Ch R = 1 ,76      ,70.05,70.05,70.05
XS GIS Cut Line= 6
      3490174.74      5377323.38      3490175.73      5377322.26
      3490175.89      5377322.21      3490176.73      5377320.95
      3490178.57      5377319.09      3490184.11      5377311.71
#Sta/Elev= 14
       0  418.53    .638  417.71    .727  417.26    .786  417.22   1.128   417.2
   1.217  417.19   1.517  417.15   1.666  417.11   1.686  417.12   2.014  417.24
   2.189   417.4   3.201  418.03   5.818  418.64  15.046  418.71
#Mann= 3 , 0 , 0
       0     .05       0    .727     .04       0   2.014     .05       0
Bank Sta=0.727,2.014
XS Rating Curve= 0 ,0
Exp/Cntr=0.3,0.1

Type RM Length L Ch R = 1 ,75      ,63.35,63.35,63.35
XS GIS Cut Line= 6
3490236.118436615377358.67463124      3490236.66      5377358.33
      3490237.01      5377357.22      3490237.03      5377356.81
      3490237.73      5377355.44      3490240.24      5377349.27
#Sta/Elev= 13
     .01  417.68    .652  416.59   1.517  416.48   1.839  416.29    2.03  416.21
    2.25   416.2   2.378  416.23   2.502  416.25   2.691  416.27   2.973  416.33
   3.322  416.43    3.94  417.41  10.474   417.7
#Mann= 3 , 0 , 0
     .01     .05       0   1.517     .04       0   3.322     .05       0
Bank Sta=1.517,3.322
XS Rating Curve= 0 ,0
Exp/Cntr=0.3,0.1

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
Type RM Length L Ch R = 1 ,74      ,98.4,98.4,98.4
XS GIS Cut Line= 6
      3490359.95      5377380.49      3490360.52       5377378.3
       3490361.3       5377376.8      3490361.35      5377376.32
      3490360.91      5377375.48       3490361.1      5377371.57
#Sta/Elev= 13
       0  416.26   2.263  415.72   2.905  415.39   3.399  415.21   3.419  415.21
   3.549  415.14    3.72  415.18   3.881  415.19   4.157  415.27   4.167  415.27
    4.65  415.71    5.64  416.56   9.513   416.7
#Mann= 3 , 0 , 0
       0     .05       0   2.905     .04       0   4.167     .05       0
Bank Sta=2.905,4.167
XS Rating Curve= 0 ,0
Exp/Cntr=0.3,0.1

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
Type RM Length L Ch R = 1 ,72      ,92.437,92.437,92.437
XS GIS Cut Line= 6
       3490555.5      5377397.44      3490555.95      5377394.61
      3490556.12      5377393.96      3490556.33      5377393.71
      3490557.02      5377391.843490558.982568765377385.25845627
#Sta/Elev= 13
       0  416.47   2.522  414.38   2.833  413.95    2.97  413.92   3.123  413.94
    3.21  413.94    3.37  413.92   3.561  413.95   3.645  414.03   3.888  414.35
    4.61  414.52   5.882  415.26   12.75  415.97
#Mann= 3 , 0 , 0
       0     .05       0   2.522     .04       0   3.888     .05       0
Bank Sta=2.522,3.888
XS Rating Curve= 0 ,0
Exp/Cntr=0.3,0.1

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
Type RM Length L Ch R = 1 ,71      ,57.155,57.155,57.155
XS GIS Cut Line= 6
      3490804.81      5377522.51      3490803.45      5377508.14
      3490803.33      5377507.65      3490803.53      5377507.31
      3490803.06      5377506.063490802.382884115377499.35299052
#Sta/Elev= 14
       0  421.22  14.258  413.01   14.44  412.59  14.552  412.45  14.674  412.35
  14.958  412.27  15.165  412.27  15.357  412.26  15.706  412.33  15.907  412.43
  16.307  412.59  16.709  412.78  17.656  413.84   23.45  418.49
#Mann= 3 , 0 , 0
       0     .05       0   14.44     .04       0  16.709     .05       0
Bank Sta=14.44,16.709
XS Rating Curve= 0 ,0
Exp/Cntr=0.3,0.1

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
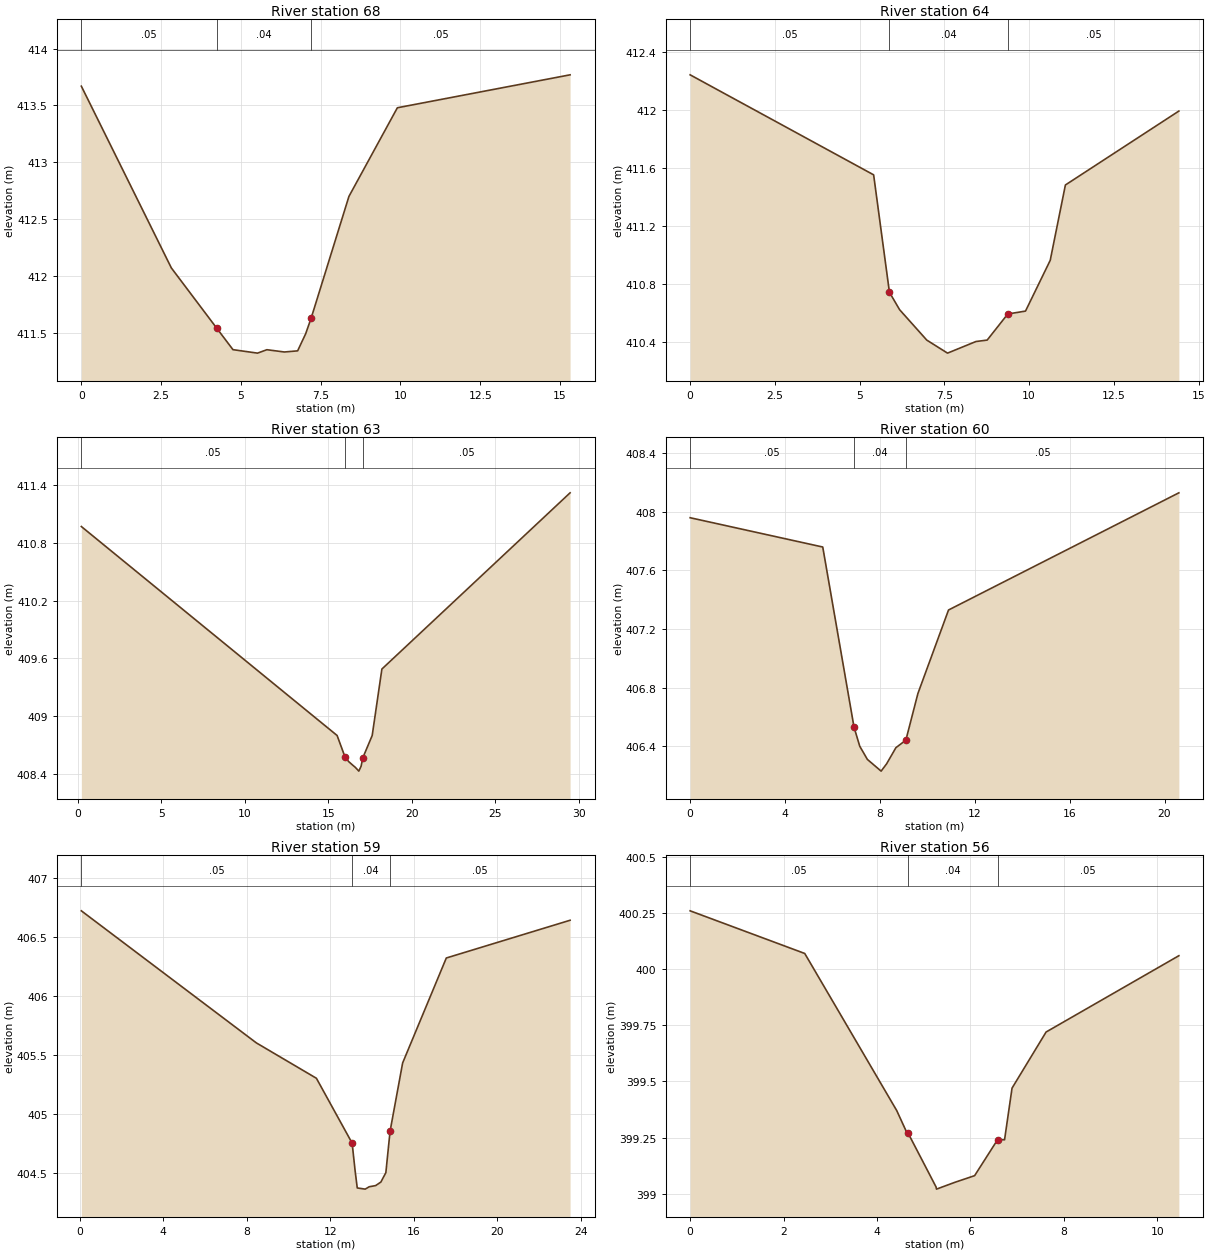
Type RM Length L Ch R = 1 ,68      ,50.65,50.65,50.65
XS GIS Cut Line= 6
      3490916.43      5377498.25      3490916.42       5377493.5
      3490916.65      5377492.78      3490916.46      5377492.55
       3490916.4      5377490.01      3490915.23      5377483.18
#Sta/Elev= 14
       0  413.67    2.82  412.07   4.241  411.54   4.752  411.35   4.762  411.35
    5.52  411.32   5.813  411.35   6.362  411.33   6.777  411.34   7.028  411.49
   7.203  411.63   8.385   412.7   9.902  413.48  15.314  413.77
#Mann= 3 , 0 , 0
       0     .05       0   4.241     .04       0   7.203     .05       0
Bank Sta=4.241,7.203
XS Rating Curve= 0 ,0
Exp/Cntr=0.3,0.1

Type RM Length L Ch R = 1 ,64      ,82.185,82.185,82.185
XS GIS Cut Line= 6
      3490968.28      5377489.45      3490965.72      5377484.68
      3490965.19      5377484.13      3490963.98      5377481.87
      3490963.54      5377480.833490960.840907415377477.21681597
#Sta/Elev= 13
       0  412.24   5.414  411.55    5.88  410.74   6.179  410.62   6.981  410.41
   7.594  410.32   8.432   410.4   8.764  410.41   9.372  410.59   9.895  410.61
  10.624  410.96  11.072  411.48   14.42  411.99
#Mann= 3 , 0 , 0
       0     .05       0    5.88     .04       0   9.372     .05       0
Bank Sta=5.88,9.372
XS Rating Curve= 0 ,0
Exp/Cntr=0.3,0.1

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
Type RM Length L Ch R = 1 ,63      ,75.455,75.455,75.455
XS GIS Cut Line= 6
3491120.975322315377516.88471905      3491124.13       5377501.9
      3491124.19      5377500.96      3491124.59       5377499.9
      3491124.44      5377499.34      3491125.84      5377488.16
#Sta/Elev= 13
     .22  410.97  15.533   408.8      16  408.58   16.22  408.53  16.481  408.49
  16.619  408.47  16.727  408.45  16.833  408.43  16.967  408.48  17.077  408.57
  17.634   408.8  18.214  409.49  29.482  411.32
#Mann= 3 , 0 , 0
     .22     .05       0      16     .04       0  17.077     .05       0
Bank Sta=16,17.077
XS Rating Curve= 0 ,0
Exp/Cntr=0.3,0.1

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
Type RM Length L Ch R = 1 ,60      ,79.89,79.89,79.89
XS GIS Cut Line= 6
      3491267.91      5377542.46       3491269.5       5377537.1
      3491270.67      5377536.49      3491271.14      5377535.46
      3491271.32      5377533.94      3491276.84      5377524.43
#Sta/Elev= 13
       0  407.96   5.591  407.76    6.91  406.53   7.151   406.4   7.473  406.31
   8.052  406.23   8.284  406.28   8.675  406.39   9.083  406.44   9.093  406.44
   9.603  406.76  10.894  407.33  20.606  408.13
#Mann= 3 , 0 , 0
       0     .05       0    6.91     .04       0   9.093     .05       0
Bank Sta=6.91,9.093
XS Rating Curve= 0 ,0
Exp/Cntr=0.3,0.1

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
Type RM Length L Ch R = 1 ,59      ,90.76,90.76,90.76
XS GIS Cut Line= 6
3491426.933409625377566.00129642      3491428.54      5377557.77
      3491430.23      5377552.07      3491430.97      5377551.61
      3491431.78      5377549.68      3491432.56       5377543.8
#Sta/Elev= 15
     .07  406.72   8.457   405.6  11.334   405.3  13.046  404.75  13.186  404.52
  13.291  404.37  13.672  404.36  13.862  404.38  14.172  404.39  14.424  404.42
  14.662   404.5  14.863  404.85  15.466  405.43  17.559  406.32   23.49  406.64
#Mann= 3 , 0 , 0
     .07     .05       0  13.046     .04       0  14.863     .05       0
Bank Sta=13.046,14.863
XS Rating Curve= 0 ,0
Exp/Cntr=0.3,0.1

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
Type RM Length L Ch R = 1 ,56      ,36.31,36.31,36.31
XS GIS Cut Line= 6
      3491703.61      5377775.51      3491705.47      5377773.91
      3491706.29      5377772.12      3491707.85      5377770.96
      3491708.13      5377771.06      3491710.33      5377768.25
#Sta/Elev= 14
       0  400.26   2.453  400.07   4.422  399.37   4.642  399.27   4.664  399.27
   5.263  399.03   5.273  399.02   5.662  399.05   6.089  399.08    6.58  399.24
    6.73  399.24    6.89  399.47   7.619  399.72  10.461  400.06
#Mann= 3 , 0 , 0
       0     .05       0   4.664     .04       0    6.58     .05       0
Bank Sta=4.664,6.58
XS Rating Curve= 0 ,0
Exp/Cntr=0.3,0.1

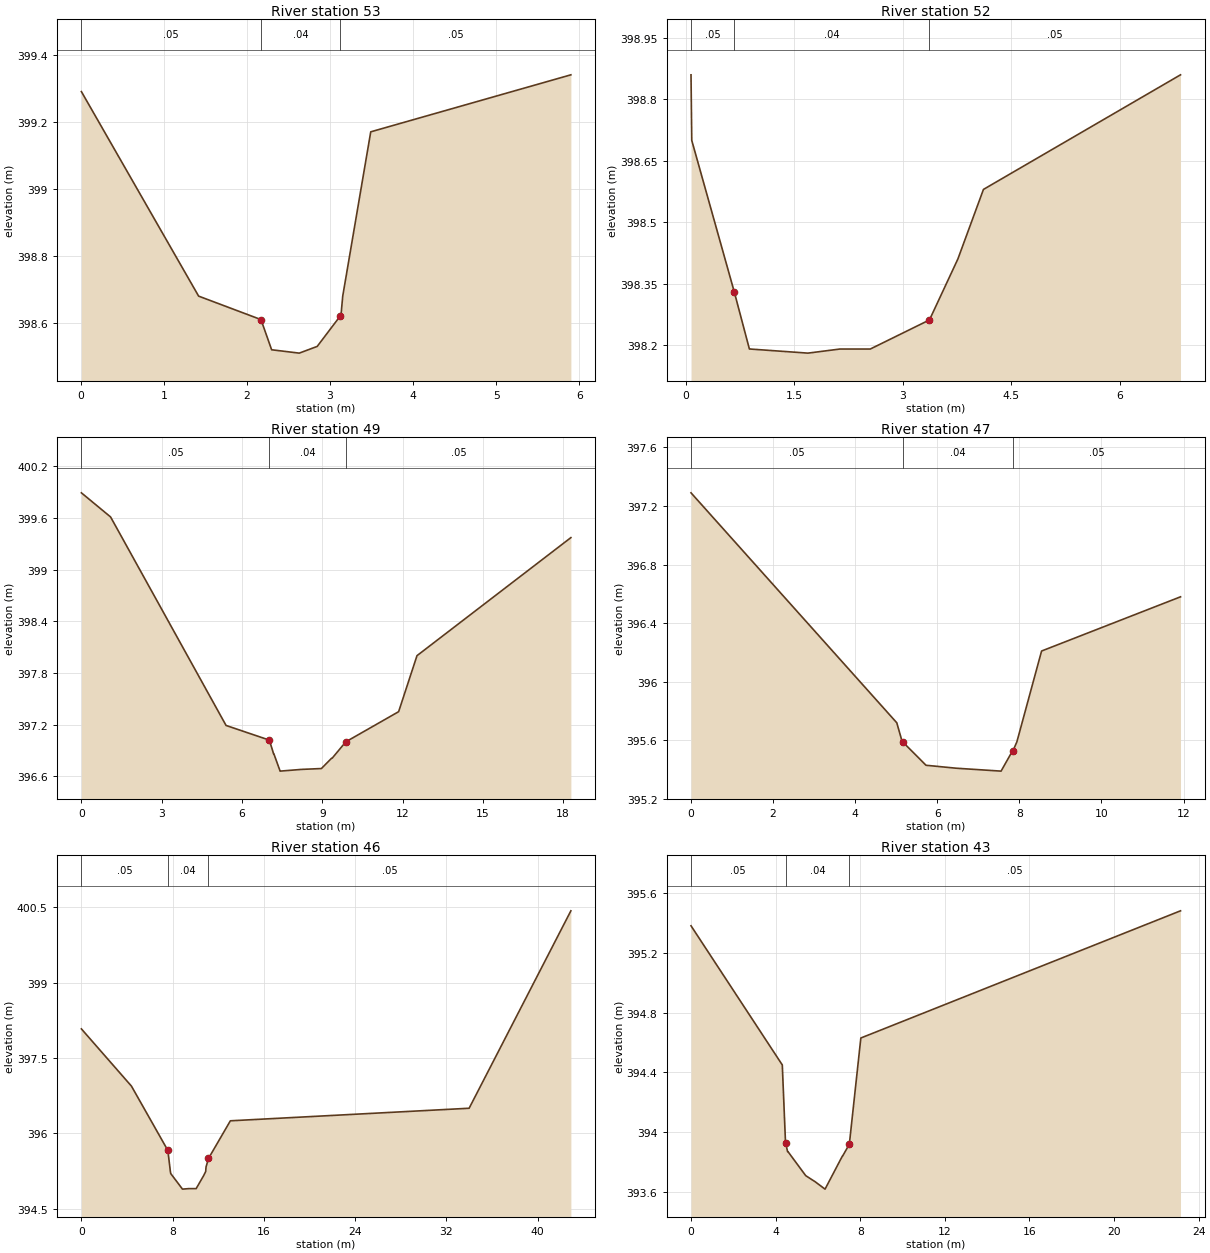
Type RM Length L Ch R = 1 ,53      ,39.97,39.97,39.97
XS GIS Cut Line= 6
3491738.936056195377787.73204245      3491739.79      5377786.61
        3491740.      5377785.47      3491739.88      5377785.29
      3491740.13      5377784.72      3491740.43      5377782.33
#Sta/Elev= 11
     .01  399.29    1.42  398.68    2.17  398.61   2.298  398.52    2.63  398.51
   2.846  398.53   3.121  398.62   3.131  398.62   3.153  398.68    3.49  399.17
   5.897  399.34
#Mann= 3 , 0 , 0
     .01     .05       0    2.17     .04       0   3.121     .05       0
Bank Sta=2.17,3.121
XS Rating Curve= 0 ,0
Exp/Cntr=0.3,0.1

Type RM Length L Ch R = 1 ,52      ,75.76,75.76,75.76
XS GIS Cut Line= 6
3491777.657344375377799.49129285      3491777.95      5377798.97
      3491777.96      5377797.96      3491778.39      5377795.95
      3491778.26      5377795.62      3491779.05      5377793.01
#Sta/Elev= 13
     .07  398.86     .08   398.7    .668  398.33    .878  398.19    .888  398.19
   1.688  398.18   2.131  398.19   2.551  398.19   3.357  398.26   3.367  398.26
   3.763  398.41   4.117  398.58   6.844  398.86
#Mann= 3 , 0 , 0
     .07     .05       0    .668     .04       0   3.357     .05       0
Bank Sta=0.668,3.357
XS Rating Curve= 0 ,0
Exp/Cntr=0.3,0.1

Type RM Length L Ch R = 1 ,49      ,53.645,53.645,53.645
XS GIS Cut Line= 6
      3491846.83      5377829.91      3491848.77      5377824.87
      3491848.64      5377821.38      3491849.85      5377818.78
      3491849.58      5377818.153491851.377189075377812.68815165
#Sta/Elev= 16
       0  399.89   1.091  399.61   5.406  397.19   7.023  397.02   7.183  396.86
   7.193  396.86   7.414  396.67   7.424  396.66   8.224  396.68   8.968  396.69
    9.35  396.81    9.37  396.81    9.88     397  11.854  397.35   12.54     398
   18.29  399.37
#Mann= 3 , 0 , 0
       0     .05       0   7.023     .04       0    9.88     .05       0
Bank Sta=7.023,9.88
XS Rating Curve= 0 ,0
Exp/Cntr=0.3,0.1

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
Type RM Length L Ch R = 1 ,47      ,75.89,75.89,75.89
XS GIS Cut Line= 6
      3491951.11      5377854.31      3491952.56      5377849.51
      3491952.81       5377848.1      3491952.84        5377847.
      3491953.51      5377846.32      3491954.64      5377843.13
#Sta/Elev= 13
       0  397.29   5.014  395.72   5.146  395.59   5.156  395.59   5.726  395.43
   6.455  395.41   7.555  395.39   7.575   395.4   7.837  395.53   7.847  395.53
    7.94  395.59   8.542  396.21  11.927  396.58
#Mann= 3 , 0 , 0
       0     .05       0   5.156     .04       0   7.847     .05       0
Bank Sta=5.156,7.847
XS Rating Curve= 0 ,0
Exp/Cntr=0.3,0.1

Type RM Length L Ch R = 1 ,46      ,58.44,58.44,58.44
XS GIS Cut Line= 6
      3492026.41      5377877.83      3492026.32      5377873.44
      3492026.53      5377870.06      3492026.46      5377869.01
      3492028.22      5377843.97      3492029.36      5377835.12
#Sta/Elev= 15
       0  398.08   4.391  396.94   7.583  395.66   7.798  395.25   7.834   395.2
   8.864  394.89   9.413   394.9  10.063   394.9    10.7  395.15    10.9  395.24
   10.93  395.33  11.144   395.5  13.063  396.25      34   396.5  42.923  400.43
#Mann= 3 , 0 , 0
       0     .05       0   7.583     .04       0  11.144     .05       0
Bank Sta=7.583,11.144
XS Rating Curve= 0 ,0
Exp/Cntr=0.3,0.1

Type RM Length L Ch R = 1 ,43      ,55.4,55.4,55.4
XS GIS Cut Line= 6
      3492082.85      5377882.58      3492083.32      5377878.29
      3492083.85      5377876.86      3492084.09      5377876.45
      3492084.26      5377875.65      3492086.84      5377859.88
#Sta/Elev= 13
       0  395.38   4.316  394.45   4.468  393.93   4.568  393.87   4.588  393.87
   5.424  393.71   5.863  393.67   6.338  393.62   7.154  393.84   7.164  393.84
   7.486  393.92    8.03  394.63  23.145  395.48
#Mann= 3 , 0 , 0
       0     .05       0   4.468     .04       0   7.486     .05       0
Bank Sta=4.468,7.486
XS Rating Curve= 0 ,0
Exp/Cntr=0.3,0.1

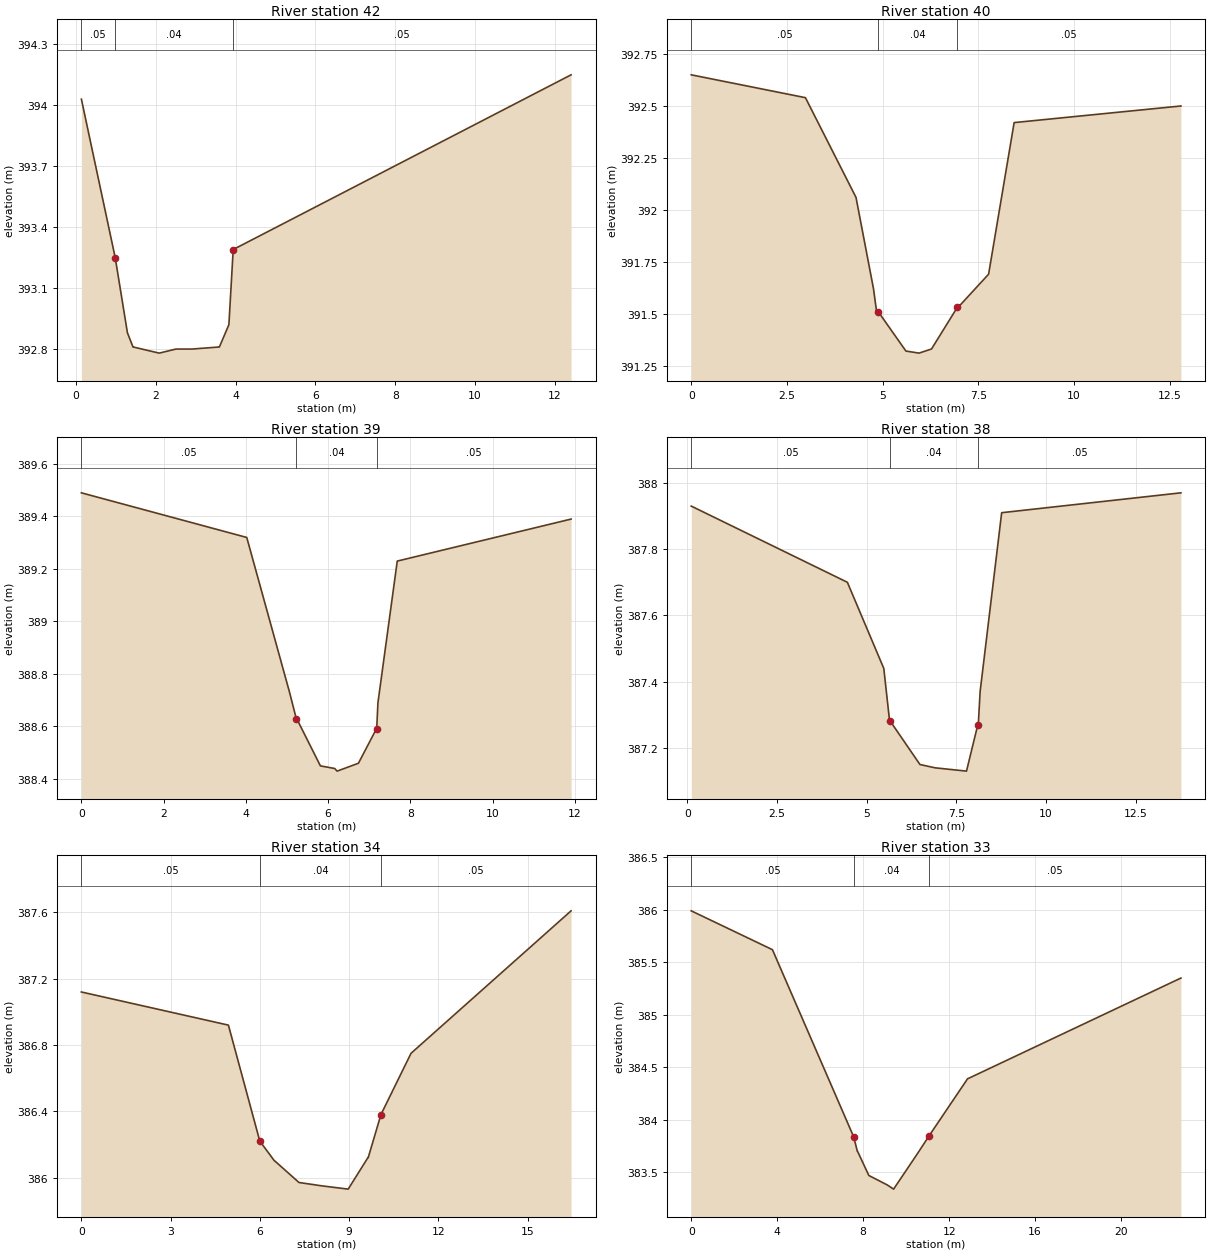
Type RM Length L Ch R = 1 ,42      ,66,66,66
XS GIS Cut Line= 6
3492138.932984235377888.06103791      3492138.66      5377886.82
      3492138.92       5377885.4       3492138.9      5377884.73
      3492139.09      5377884.43      3492141.37      5377876.28
#Sta/Elev= 13
     .14  394.03    .987  393.25   1.293  392.88   1.433  392.81   1.443  392.81
   2.088  392.78   2.509   392.8   2.905   392.8   3.575  392.81   3.595  392.81
   3.834  392.92   3.942  393.29  12.404  394.15
#Mann= 3 , 0 , 0
     .14     .05       0    .987     .04       0   3.942     .05       0
Bank Sta=0.987,3.942
XS Rating Curve= 0 ,0
Exp/Cntr=0.3,0.1

Type RM Length L Ch R = 1 ,40      ,96.2,96.2,96.2
XS GIS Cut Line= 6
      3492201.92      5377903.03       3492203.1      5377900.29
      3492203.27      5377898.98      3492203.09      5377898.56
      3492203.82      5377896.59      3492206.66       5377891.5
#Sta/Elev= 14
       0  392.65   2.983  392.54   4.304  392.06   4.761  391.62   4.842  391.51
   4.883  391.51   5.608  391.32    5.95  391.31   6.277  391.33   6.949  391.53
   6.969  391.53   7.768  391.69   8.435  392.42  12.792   392.5
#Mann= 3 , 0 , 0
       0     .05       0   4.883     .04       0   6.949     .05       0
Bank Sta=4.883,6.949
XS Rating Curve= 0 ,0
Exp/Cntr=0.3,0.1

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
Type RM Length L Ch R = 1 ,39      ,67.415,67.415,67.415
XS GIS Cut Line= 6
      3492383.24       5377966.3      3492384.94      5377961.37
      3492385.08      5377960.81      3492385.31      5377960.48
      3492385.87      5377959.14      3492387.88      5377955.42
#Sta/Elev= 14
       0  389.49   4.022  389.32   5.063  388.73   5.226  388.63   5.236  388.63
   5.813  388.45    6.16  388.44    6.22  388.43   6.738  388.46   7.172  388.59
   7.182  388.59   7.212  388.69   7.682  389.23   11.91  389.39
#Mann= 3 , 0 , 0
       0     .05       0   5.226     .04       0   7.182     .05       0
Bank Sta=5.226,7.182
XS Rating Curve= 0 ,0
Exp/Cntr=0.3,0.1

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
Type RM Length L Ch R = 1 ,38      ,90.15,90.15,90.15
XS GIS Cut Line= 6
3492502.199494995378016.79473309      3492504.95      5378013.42
      3492506.62      5378012.32      3492506.82      5378011.96
      3492507.85      5378011.27      3492511.79      5378007.29
#Sta/Elev= 13
     .11  387.93   4.464   387.7    5.48  387.44   5.643  387.28   5.665  387.28
   6.488  387.15    6.91  387.14   7.786  387.13   8.102  387.27    8.12  387.28
   8.166  387.37   8.767  387.91  13.766  387.97
#Mann= 3 , 0 , 0
     .11     .05       0   5.665     .04       0   8.102     .05       0
Bank Sta=5.665,8.102
XS Rating Curve= 0 ,0
Exp/Cntr=0.3,0.1

Type RM Length L Ch R = 1 ,34      ,84.083,84.083,84.083
XS GIS Cut Line= 6
      3492585.84      5378058.65      3492584.62      5378053.86
      3492583.89      5378052.52      3492583.11      5378049.07
      3492583.27      5378048.07      3492583.18      5378042.69
#Sta/Elev= 13
       0  387.12   4.943  386.92   5.998  386.22   6.493   386.1   6.503   386.1
   7.316  385.97   8.075  385.95    8.97  385.93   9.633  386.12   9.643  386.12
  10.071  386.38  11.083  386.75  16.464  387.61
#Mann= 3 , 0 , 0
       0     .05       0   5.998     .04       0  10.071     .05       0
Bank Sta=5.998,10.071
XS Rating Curve= 0 ,0
Exp/Cntr=0.3,0.1

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
Type RM Length L Ch R = 1 ,33      ,66.225,66.225,66.225
XS GIS Cut Line= 6
       3492811.5      5378148.15      3492810.96      5378144.41
      3492811.54       5378140.5      3492811.54      5378137.77
      3492810.56      5378135.673492807.778599515378126.13519903
#Sta/Elev= 12
       0  385.99   3.779  385.62   7.556  383.84   7.731   383.7   7.741   383.7
   8.265  383.47   9.122  383.38   9.417  383.34  10.535  383.68  11.078  383.85
  12.858  384.39   22.79  385.35
#Mann= 3 , 0 , 0
       0     .05       0   7.556     .04       0  11.078     .05       0
Bank Sta=7.556,11.078
XS Rating Curve= 0 ,0
Exp/Cntr=0.3,0.1

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