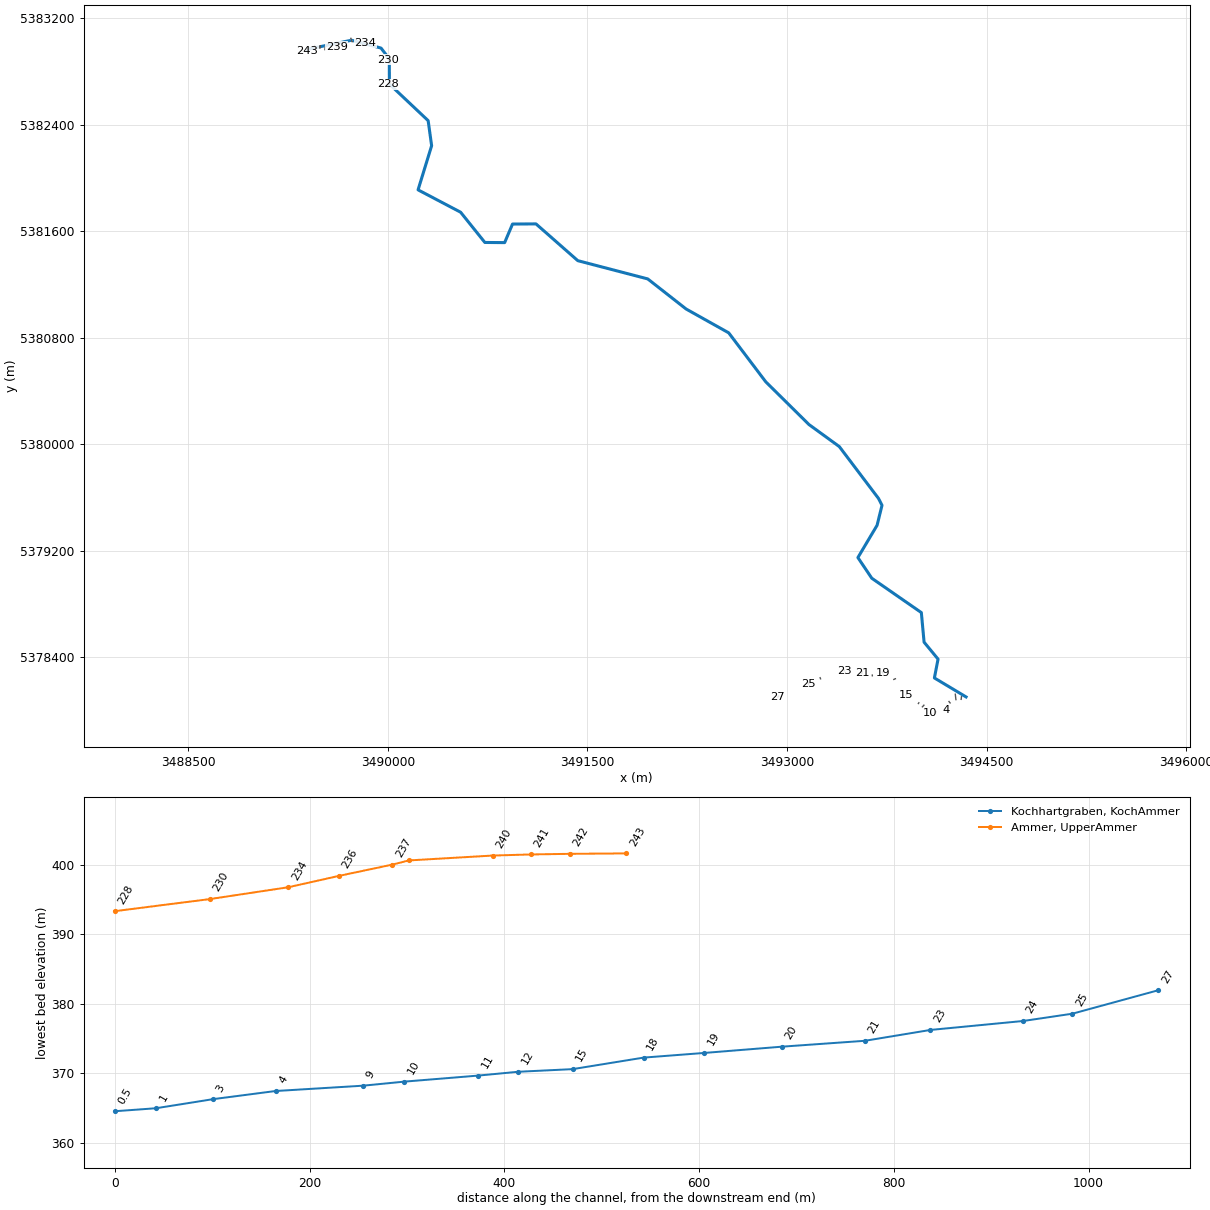
HEC-RAS study Amm_final.prj: Amm_final

--- Amm_final.g04 (geometry) --- (continued)

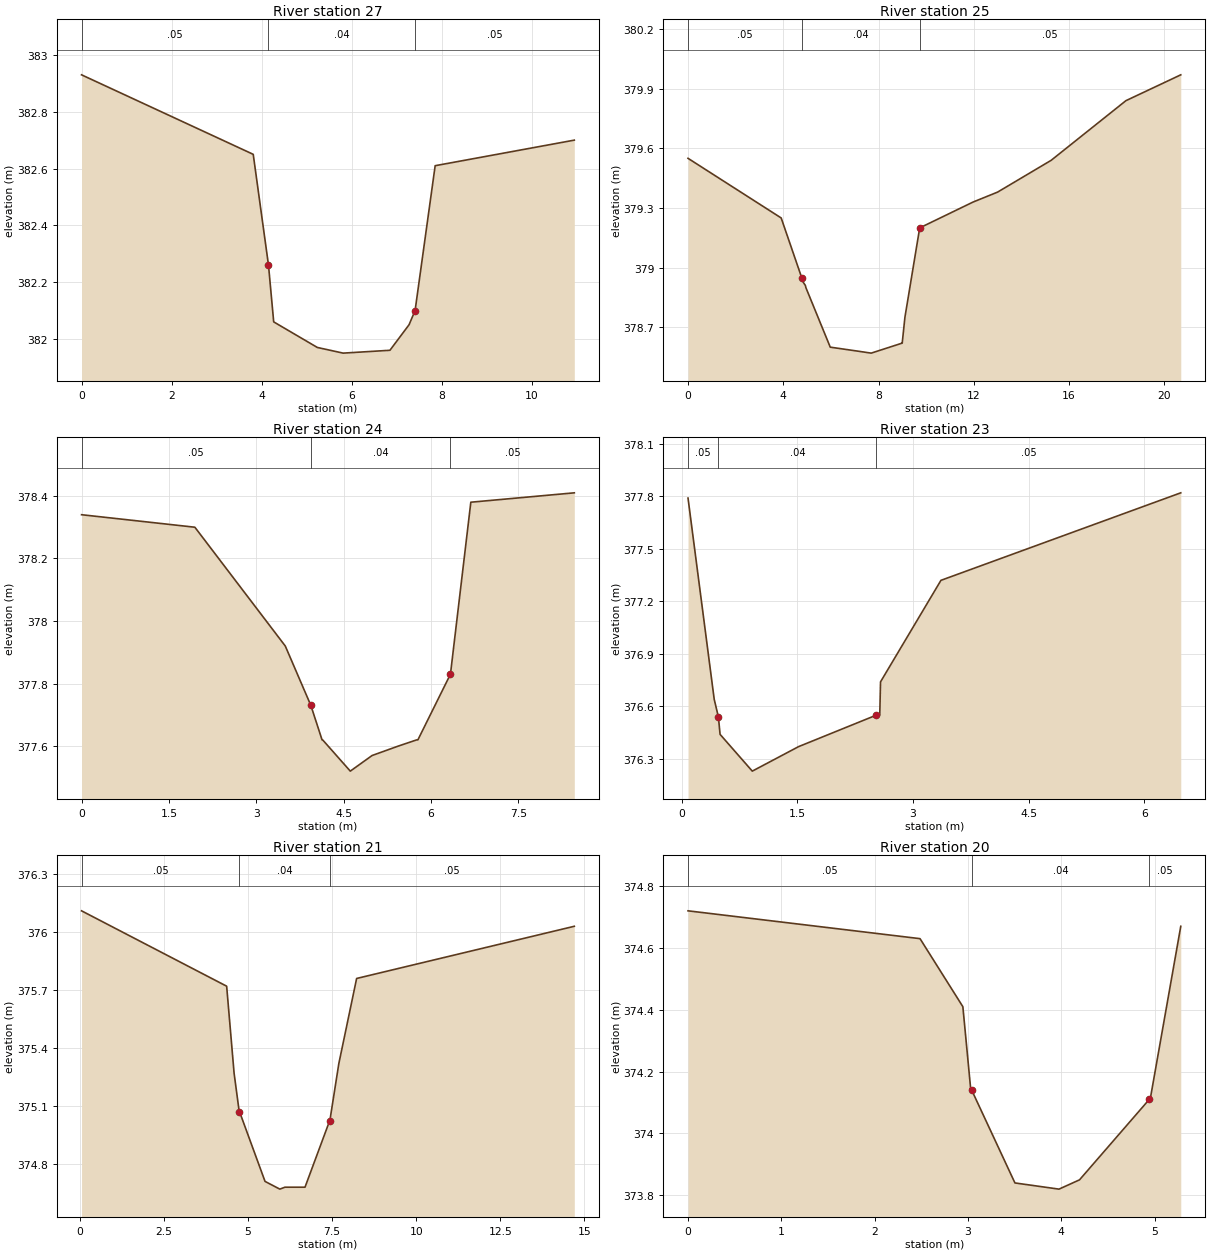
Type RM Length L Ch R = 1 ,27      ,88.3,88.3,88.3
XS GIS Cut Line= 6
      3492938.53      5378106.65      3492936.32      5378103.54
      3492935.11      5378102.81      3492934.98      5378102.25
      3492934.25      5378101.51 3492931.96335085378098.12497778
#Sta/Elev= 11
       0  382.93   3.815  382.65   4.154  382.26    4.27  382.06   5.239  381.97
   5.813  381.95   6.853  381.96   7.278  382.05   7.412   382.1   7.858  382.61
   10.95   382.7
#Mann= 3 , 0 , 0
       0     .05       0   4.154     .04       0   7.412     .05       0
Bank Sta=4.154,7.412
XS Rating Curve= 0 ,0
Exp/Cntr=0.3,0.1

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
Type RM Length L Ch R = 1 ,25      ,50.59,50.59,50.59
XS GIS Cut Line= 6
      3493155.27      5378212.24      3493157.08      5378206.58
      3493155.97      5378206.26      3493157.55       5378205.5
      3493157.96       5378204.9      3493161.57      5378194.56
#Sta/Elev= 18
       0  379.55   3.912  379.25   4.773  378.95    4.82  378.93    4.93  378.91
   4.948   378.9   5.973   378.6   7.128  378.58   7.692  378.57   8.984  378.62
   8.994  378.62   9.108  378.75   9.729   379.2   11.97  379.33      13  379.38
   15.25  379.54  18.389  379.84  20.692  379.97
#Mann= 3 , 0 , 0
       0     .05       0   4.773     .04       0   9.729     .05       0
Bank Sta=4.773,9.729
XS Rating Curve= 0 ,0
Exp/Cntr=0.3,0.1

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
Type RM Length L Ch R = 1 ,24      ,95.3,95.3,95.3
XS GIS Cut Line= 6
       3493249.5      5378244.13      3493250.41      5378242.41
      3493250.76      5378240.26      3493251.42      5378238.78
      3493252.06      5378238.12      3493252.42      5378236.38
#Sta/Elev= 14
       0  378.34   1.946   378.3   3.499  377.92   3.938  377.73    4.13  377.62
    4.14  377.62   4.615  377.52    4.99  377.57   5.438   377.6   5.756  377.62
   5.776  377.62   6.335  377.83   6.685  378.38   8.462  378.41
#Mann= 3 , 0 , 0
       0     .05       0   3.938     .04       0   6.335     .05       0
Bank Sta=3.938,6.335
XS Rating Curve= 0 ,0
Exp/Cntr=0.3,0.1

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
Type RM Length L Ch R = 1 ,23      ,67.23,67.23,67.23
XS GIS Cut Line= 6
3493430.428275415378301.73620749      3493430.68      5378301.41
      3493431.36       5378299.5       3493431.4      5378299.49
      3493431.48       5378298.7      3493432.41      5378295.73
#Sta/Elev= 11
     .08  377.79     .42  376.64    .474  376.54    .496  376.44    .914  376.23
   1.515  376.37   2.524  376.55   2.568  376.55   2.578  376.74   3.362  377.32
   6.474  377.82
#Mann= 3 , 0 , 0
     .08     .05       0    .474     .04       0   2.524     .05       0
Bank Sta=0.474,2.524
XS Rating Curve= 0 ,0
Exp/Cntr=0.3,0.1

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
Type RM Length L Ch R = 1 ,21      ,85.48,85.48,85.48
XS GIS Cut Line= 6
3493565.284799335378291.25681521      3493563.11      5378287.53
      3493563.45      5378286.01       3493563.6      5378284.58
      3493563.38      5378283.82      3493563.59      5378277.35
#Sta/Elev= 14
     .05  376.11   4.365  375.72   4.586  375.27   4.739  375.07   4.749  375.07
   5.506  374.71   5.946  374.67   6.099  374.68   6.695  374.68    7.42  375.02
    7.43  375.02   7.701  375.32    8.23  375.76  14.703  376.03
#Mann= 3 , 0 , 0
     .05     .05       0   4.739     .04       0    7.43     .05       0
Bank Sta=4.739,7.43
XS Rating Curve= 0 ,0
Exp/Cntr=0.3,0.1

Type RM Length L Ch R = 1 ,20      ,79.62,79.62,79.62
XS GIS Cut Line= 6
       3493641.3      5378264.18      3493641.72      5378261.73
      3493641.59      5378261.29      3493641.68      5378261.26
      3493641.79      5378260.143493641.76432036 5378259.0783982
#Sta/Elev= 11
       0  374.72   2.486  374.63   2.945  374.41    3.03  374.14    3.04  374.14
   3.503  373.84   3.975  373.82   4.195  373.85   4.942  374.11   4.952  374.11
    5.28  374.67
#Mann= 3 , 0 , 0
       0     .05       0    3.04     .04       0   4.942     .05       0
Bank Sta=3.04,4.942
XS Rating Curve= 0 ,0
Exp/Cntr=0.3,0.1

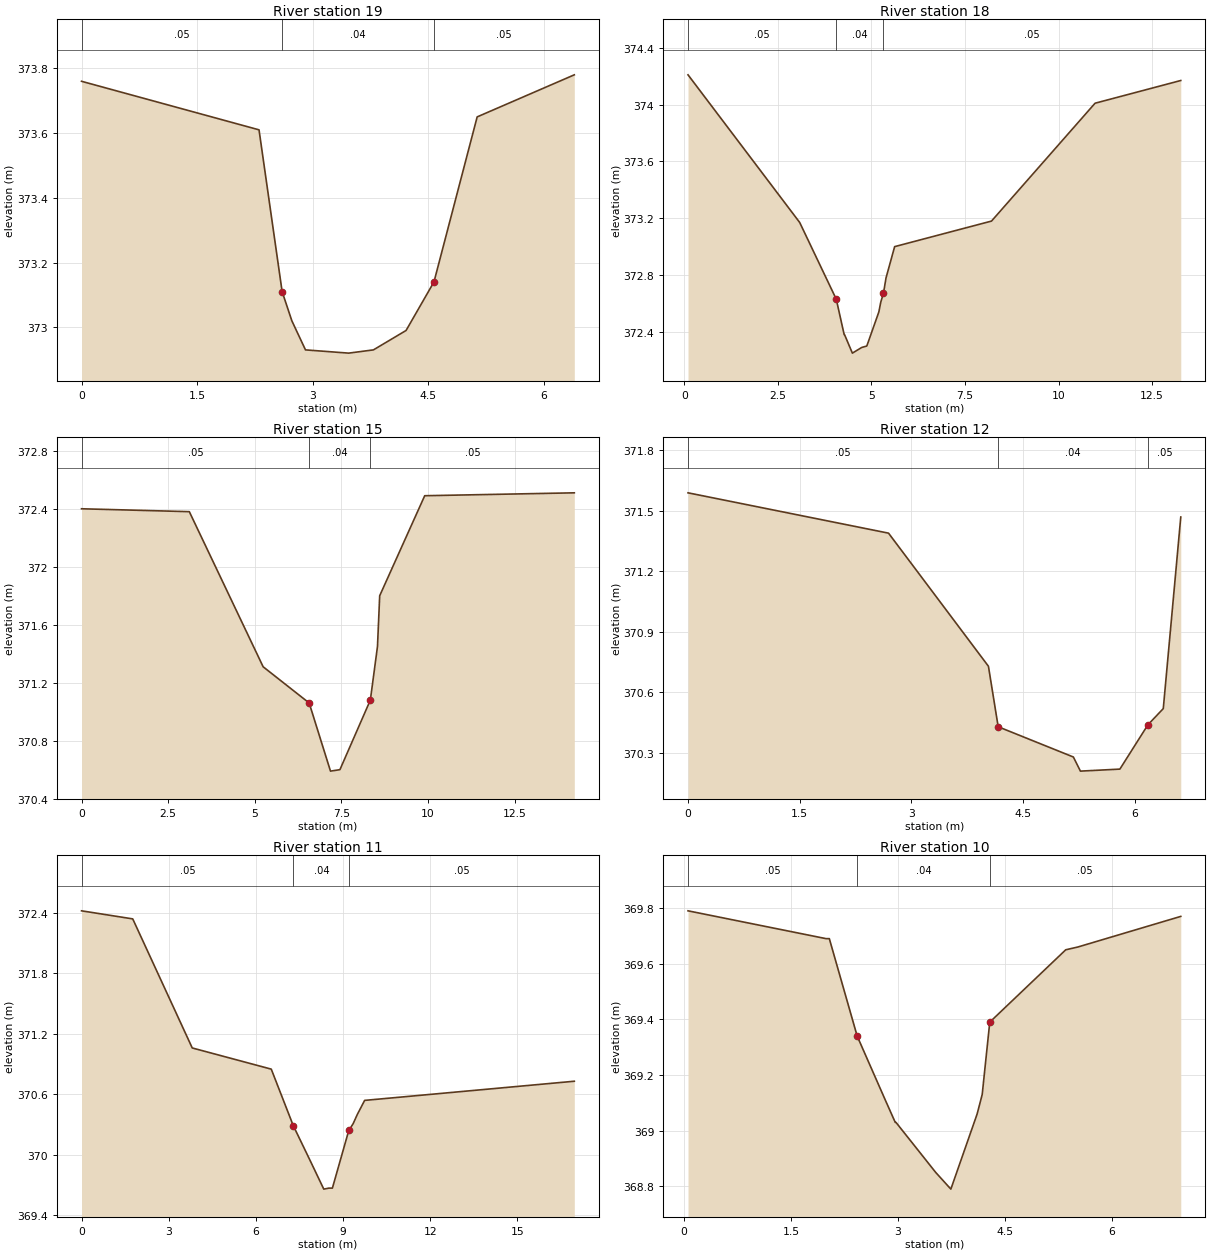
Type RM Length L Ch R = 1 ,19      ,62.16,62.16,62.16
XS GIS Cut Line= 6
      3493717.01      5378286.69      3493717.74       5378284.2
      3493717.63      5378284.14      3493717.89      5378282.32
      3493718.25      5378281.89      3493718.83      5378280.77
#Sta/Elev= 11
       0  373.76   2.304  373.61   2.604  373.11    2.73  373.02   2.907  372.93
   3.468  372.92   3.789  372.93   4.213  372.99   4.575  373.14   5.136  373.65
   6.397  373.78
#Mann= 3 , 0 , 0
       0     .05       0   2.604     .04       0   4.575     .05       0
Bank Sta=2.604,4.575
XS Rating Curve= 0 ,0
Exp/Cntr=0.3,0.1

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
Type RM Length L Ch R = 1 ,18      ,72.96,72.96,72.96
XS GIS Cut Line= 6
3493815.143690145378236.73308512      3493812.27      5378235.93
      3493810.36      5378235.08      3493807.78      5378233.74
       3493805.4      5378232.33      3493803.23       5378231.6
#Sta/Elev= 16
      .1  374.21   3.084  373.17    4.06  372.63   4.272  372.38   4.282  372.38
   4.491  372.25   4.741  372.29   4.876   372.3   5.198  372.54    5.25  372.61
    5.32  372.67    5.39  372.78    5.62     373   8.208  373.18  10.974  374.01
  13.264  374.17
#Mann= 3 , 0 , 0
      .1     .05       0    4.06     .04       0    5.32     .05       0
Bank Sta=4.06,5.32
XS Rating Curve= 0 ,0
Exp/Cntr=0.3,0.1

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
Type RM Length L Ch R = 1 ,15      ,56.02,56.02,56.02
XS GIS Cut Line= 6
      3493903.64      5378124.72      3493901.75      5378122.25
      3493900.19       5378120.8      3493899.49      5378119.67
      3493897.25      5378117.213493894.130336345378114.22639644
#Sta/Elev= 11
       0   372.4    3.11  372.38    5.24  371.31   6.569  371.06   7.184  370.59
   7.456   370.6   8.334  371.08    8.54  371.45   8.604   371.8   9.903  372.49
   14.22  372.51
#Mann= 3 , 0 , 0
       0     .05       0   6.569     .04       0   8.334     .05       0
Bank Sta=6.569,8.334
XS Rating Curve= 0 ,0
Exp/Cntr=0.3,0.1

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
Type RM Length L Ch R = 1 ,12      ,40.96,40.96,40.96
XS GIS Cut Line= 6
      3493991.06      5378056.05      3493989.45      5378053.89
      3493989.37      5378052.55      3493988.62      5378051.57
      3493988.24       5378051.23493987.744436655378050.55443666
#Sta/Elev= 10
       0  371.59   2.694  371.39   4.036  370.73   4.167  370.43   5.177  370.28
   5.272  370.21   5.802  370.22   6.179  370.44   6.385  370.52    6.62  371.47
#Mann= 3 , 0 , 0
       0     .05       0   4.167     .04       0   6.179     .05       0
Bank Sta=4.167,6.179
XS Rating Curve= 0 ,0
Exp/Cntr=0.3,0.1

Type RM Length L Ch R = 1 ,11      ,75.97,75.97,75.97
XS GIS Cut Line= 6
      3494029.32      5378037.98      3494028.29      5378036.55
      3494026.75       5378035.2      3494023.39      5378031.08
      3494022.87      5378030.91      3494017.95      5378025.63
#Sta/Elev= 15
       0  372.42   1.762  372.34    3.81  371.06    6.53  370.85   7.287  370.29
   7.857  369.95   8.338  369.66   8.513  369.67   8.634  369.67   9.157   370.2
    9.22  370.25    9.35  370.31   9.491   370.4   9.744  370.54  16.961  370.73
#Mann= 3 , 0 , 0
       0     .05       0   7.287     .04       0    9.22     .05       0
Bank Sta=7.287,9.22
XS Rating Curve= 0 ,0
Exp/Cntr=0.3,0.1

Type RM Length L Ch R = 1 ,10      ,41.99,41.99,41.99
XS GIS Cut Line= 6
3494079.416157025377983.00161874      3494078.94      5377980.69
      3494078.74      5377980.35      3494078.76      5377979.47
      3494078.19      5377977.86      3494077.85      5377976.46
#Sta/Elev= 15
     .06  369.79   1.994  369.69   2.039  369.69   2.429  369.34   2.823  369.11
   2.962  369.03   2.972  369.03   3.529  368.85   3.741  368.79   4.109  369.06
    4.18  369.13   4.286  369.39    5.35  369.65    5.52  369.66   6.961  369.77
#Mann= 3 , 0 , 0
     .06     .05       0   2.429     .04       0   4.286     .05       0
Bank Sta=2.429,4.286
XS Rating Curve= 0 ,0
Exp/Cntr=0.3,0.1

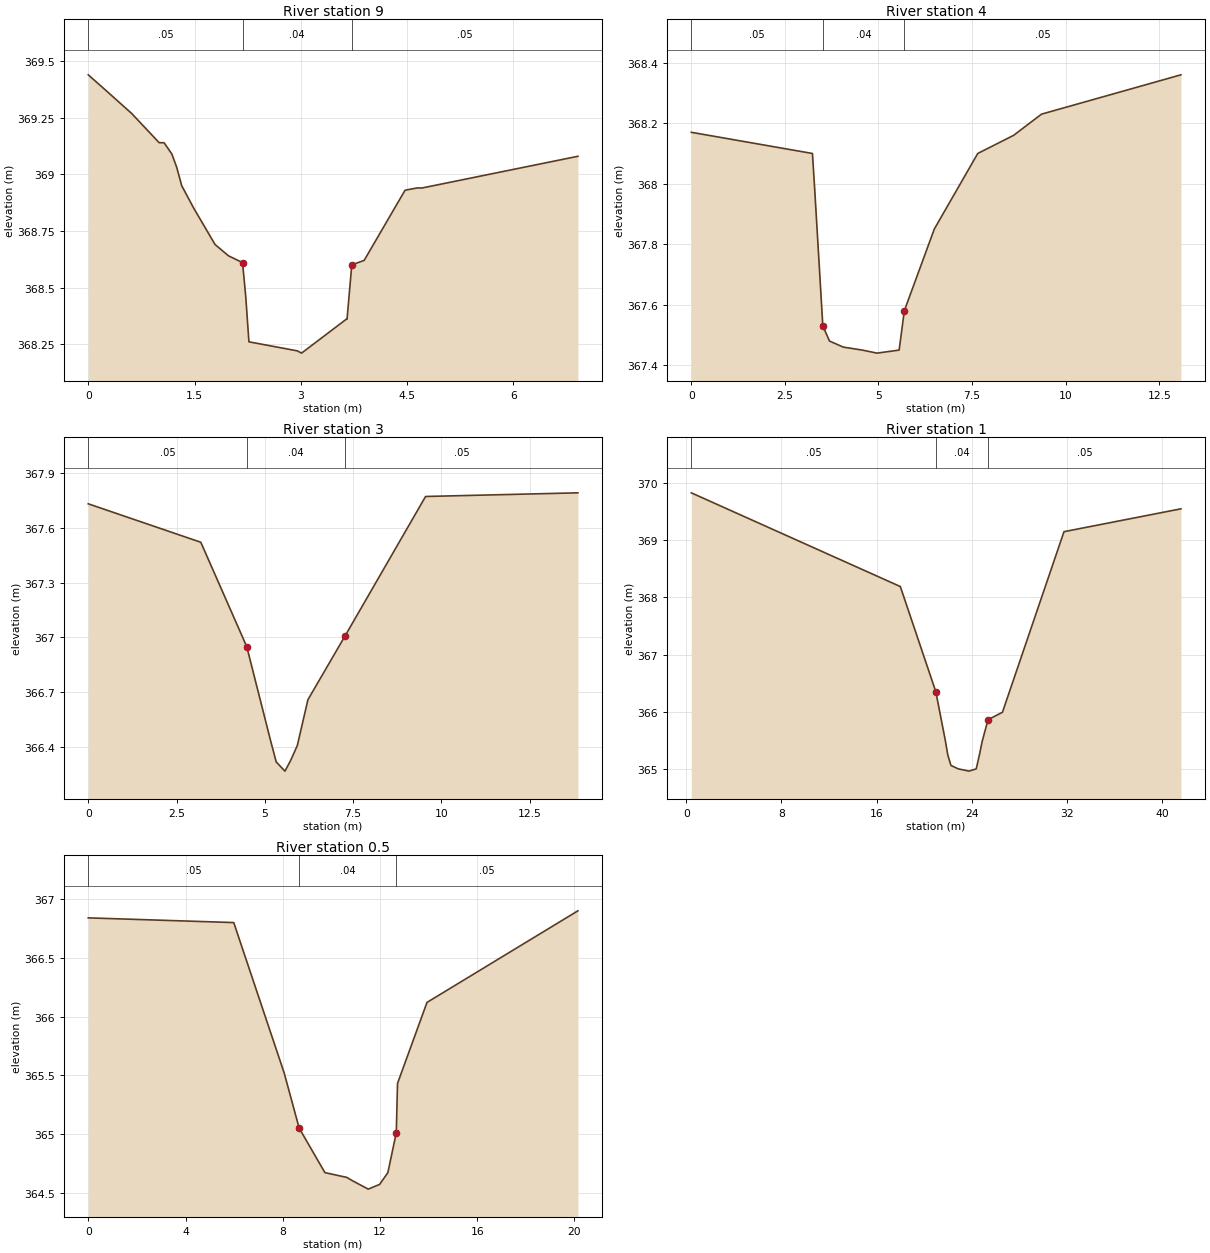
Type RM Length L Ch R = 1 ,9       ,90.17,90.17,90.17
XS GIS Cut Line= 6
      3494120.24      5377989.57      3494119.86      5377988.32
      3494119.71       5377988.1      3494118.61      5377985.46
      3494118.73      5377985.34      3494117.97       5377983.2
#Sta/Elev= 25
       0  369.44    .253  369.37     .61  369.27   1.001  369.14    1.07  369.14
    1.18  369.09    1.25  369.03   1.319  368.95    1.49  368.85   1.621  368.78
    1.79  368.69    1.98  368.64   2.178  368.61   2.223  368.46   2.268  368.26
   2.951  368.22   3.011  368.21   3.643  368.36   3.653  368.36    3.72   368.6
   3.895  368.62   4.472  368.93   4.641  368.94   4.714  368.94   6.912  369.08
#Mann= 3 , 0 , 0
       0     .05       0   2.178     .04       0    3.72     .05       0
Bank Sta=2.178,3.72
XS Rating Curve= 0 ,0
Exp/Cntr=0.3,0.1

Type RM Length L Ch R = 1 ,4       ,64.09,64.09,64.09
XS GIS Cut Line= 6
       3494187.8       5378014.9      3494190.21      5378012.74
      3494190.73      5378011.21      3494193.16      5378008.51
      3494193.78      5378008.12        3494196.      5378005.13
#Sta/Elev= 15
       0  368.17   3.236   368.1   3.297  367.98   3.513  367.53   3.691  367.48
   4.058  367.46    4.57  367.45    4.96  367.44   5.551  367.45    5.69  367.58
    6.49  367.85   7.651   368.1    8.61  368.16   9.354  368.23  13.078  368.36
#Mann= 3 , 0 , 0
       0     .05       0   3.513     .04       0    5.69     .05       0
Bank Sta=3.513,5.69
XS Rating Curve= 0 ,0
Exp/Cntr=0.3,0.1

Type RM Length L Ch R = 1 ,3       ,58.75,58.75,58.75
XS GIS Cut Line= 6
      3494217.82      5378065.67      3494219.93      5378063.28
      3494220.29      5378062.03      3494220.91      5378060.82
       3494223.1      5378057.943494226.244697925378054.98438202
#Sta/Elev= 13
       0  367.73   3.188  367.52   4.489  366.95    5.16  366.44   5.324  366.32
   5.521  366.28   5.572  366.27   5.737  366.33   5.922  366.41   6.222  366.66
   7.279  367.01   9.555  367.77   13.87  367.79
#Mann= 3 , 0 , 0
       0     .05       0   4.489     .04       0   7.279     .05       0
Bank Sta=4.489,7.279
XS Rating Curve= 0 ,0
Exp/Cntr=0.3,0.1

Type RM Length L Ch R = 1 ,1       ,42.09,42.09,42.09
XS GIS Cut Line= 6
3494265.361329165378120.44203841      3494267.09      5378102.96
      3494267.19      5378099.98      3494268.07      5378096.26
      3494268.56      5378089.39      3494270.08      5378079.68
#Sta/Elev= 16
     .42  369.83  17.987  368.19  20.969  366.35  21.765   365.5   21.98  365.24
  22.242  365.06   22.85     365  23.321  364.98  23.761  364.96  24.367     365
   24.65  365.26  24.852  365.47  25.357  365.86  26.569  365.99  31.741  369.15
  41.569  369.55
#Mann= 3 , 0 , 0
     .42     .05       0  20.969     .04       0  25.357     .05       0
Bank Sta=20.969,25.357
XS Rating Curve= 0 ,0
Exp/Cntr=0.3,0.1

Type RM Length L Ch R = 1 ,0.5     ,36.66,36.66,36.66
XS GIS Cut Line= 6
      3494311.76      5378101.84      3494310.71      5378093.85
      3494310.17      5378091.35      3494310.09      5378090.02
      3494310.19      5378089.29       3494309.1      5378081.95
#Sta/Elev= 15
       0  366.84   5.985   366.8   8.059  365.52   8.676  365.05   9.737  364.67
   9.747  364.67  10.634  364.63  10.884   364.6  11.519  364.53  11.985  364.57
  12.325  364.67  12.672  365.01  12.723  365.43  13.935  366.12  20.144   366.9
#Mann= 3 , 0 , 0
       0     .05       0   8.676     .04       0  12.672     .05       0
Bank Sta=8.676,12.672
XS Rating Curve= 0 ,0
Exp/Cntr=0.3,0.1

River Reach=Ammer           ,UpperAmmer
Reach XY= 30
3489395.577161735382966.873258153489728.130000475383035.28999901
3489949.252154955382976.396554043490011.635307365382895.62996058
3490012.228701545382705.840253223490303.522937835382431.00053655
3490329.722935435382242.568766483490227.81477579 5381910.8177954
3490547.535725175381742.744515983490729.83681592 5381515.4465235
3490878.245628745381514.28979226 3490937.7016948 5381653.8496084
3491113.987769545381654.948504653491428.209999815381378.66999974
3491953.91000006      5381241.453492242.217109485381015.38207341
3492562.323781985380836.233840693492840.570352775380468.36669055
 3493165.50000015380147.140000153493393.439650225379981.47003134
      3493688.515379591.06999933 3493714.38259925379540.10379218
3493677.39000024 5379389.96999983493533.190140825379147.42721543
 3493637.57999975378992.039999773494010.032162125378733.89918159
3494030.622597635378511.666864363494135.529999595378384.25000003
3494108.145483825378242.626141913494346.195783445378100.06183718

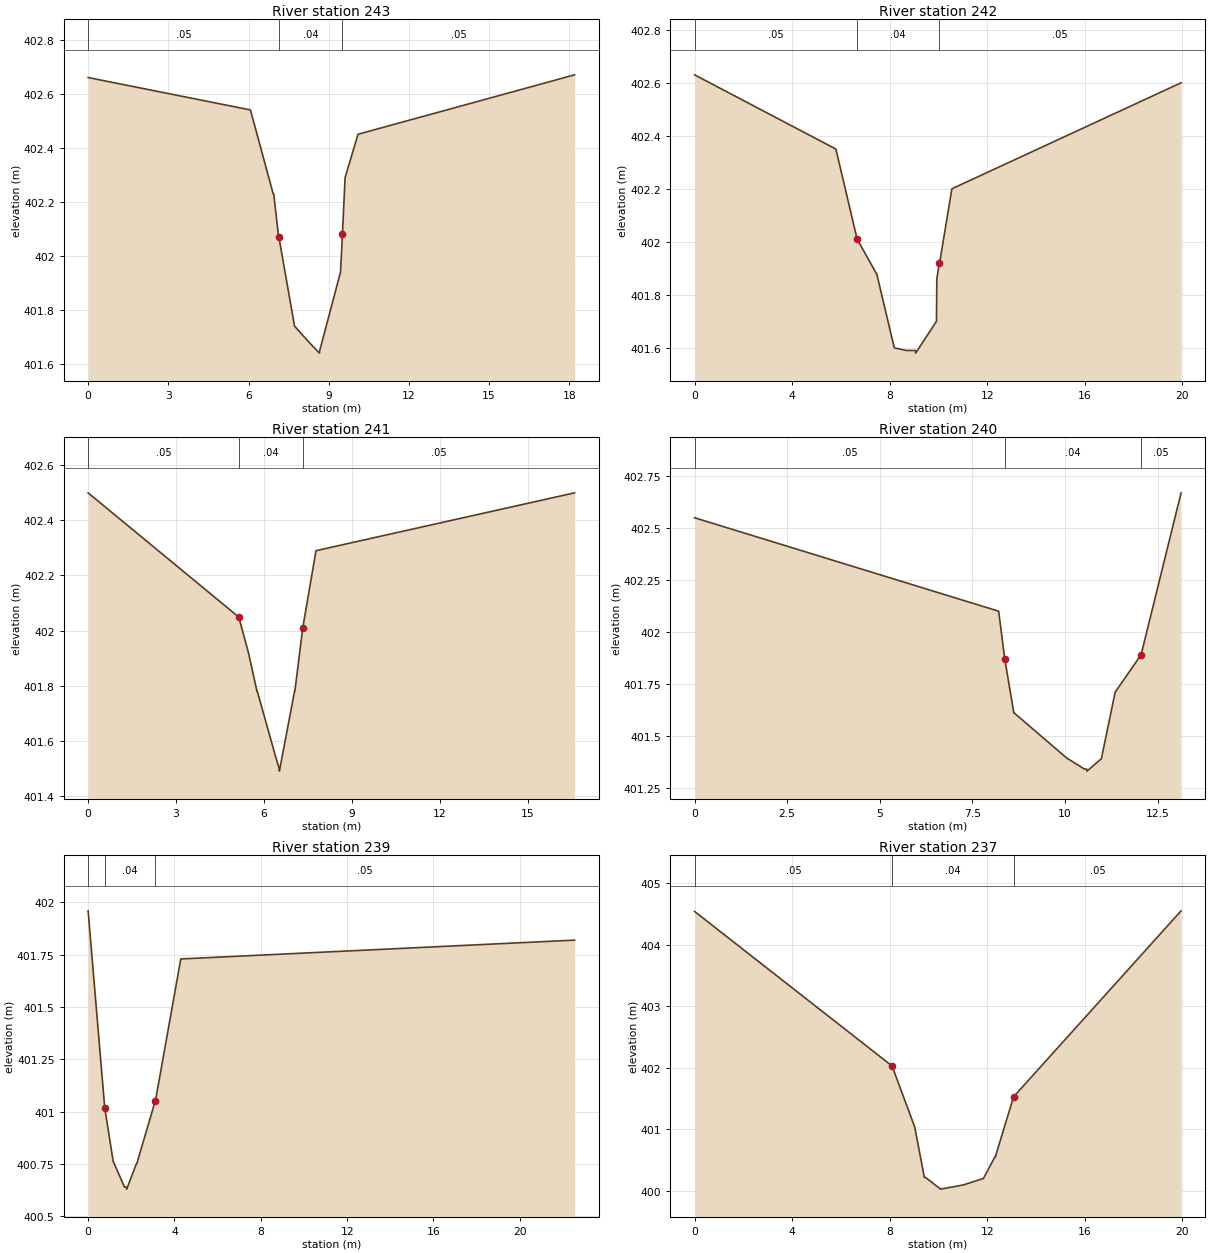
Type RM Length L Ch R = 1 ,243     ,57.83,57.83,57.83
XS GIS Cut Line= 6
      3489395.64      5382975.05      3489395.46       5382967.4
      3489395.58      5382966.87      3489395.39      5382966.53
      3489395.64      5382965.18       3489395.8      5382957.08
#Sta/Elev= 15
       0  402.66   6.072  402.54   6.922  402.23   6.942  402.23   7.125  402.07
   7.135  402.07   7.722  401.74   8.266  401.68   8.655  401.64   8.665  401.65
   9.442  401.94   9.513  402.08   9.613  402.29  10.097  402.45  18.198  402.67
#Mann= 3 , 0 , 0
       0     .05       0   7.125     .04       0   9.513     .05       0
Bank Sta=7.125,9.513
XS Rating Curve= 0 ,0
Exp/Cntr=0.3,0.1

Type RM Length L Ch R = 1 ,242     ,40.43,40.43,40.43
XS GIS Cut Line= 6
      3489449.79      5382994.43      3489450.37      5382987.79
      3489450.45      5382986.28      3489450.37      5382985.42
      3489450.57      5382983.96      3489451.51      5382974.61
#Sta/Elev= 15
       0  402.63   5.793  402.35   6.665  402.01   7.456  401.88   7.466  401.88
   8.187   401.6   8.688  401.59   9.053  401.59   9.063  401.58   9.917   401.7
   9.931  401.86  10.035  401.92  10.045  401.92  10.549   402.2  19.946   402.6
#Mann= 3 , 0 , 0
       0     .05       0   6.665     .04       0  10.035     .05       0
Bank Sta=6.665,10.035
XS Rating Curve= 0 ,0
Exp/Cntr=0.3,0.1

Type RM Length L Ch R = 1 ,241     ,39.14,39.14,39.14
XS GIS Cut Line= 6
      3489491.29      5382993.35      3489490.85      5382986.98
      3489490.88      5382986.87      3489490.79      5382986.36
      3489490.78      5382985.64      3489490.21      5382976.83
#Sta/Elev= 14
       0   402.5   5.131  402.05   5.141  402.05   5.472  401.92   5.764  401.78
   5.774  401.78   6.407  401.54   6.519   401.5   6.529  401.49   7.047  401.78
   7.057  401.78   7.327  402.01   7.778  402.29  16.606   402.5
#Mann= 3 , 0 , 0
       0     .05       0   5.141     .04       0   7.327     .05       0
Bank Sta=5.141,7.327
XS Rating Curve= 0 ,0
Exp/Cntr=0.3,0.1

Type RM Length L Ch R = 1 ,240     ,86,86,86
XS GIS Cut Line= 6
      3489529.82      5382988.26      3489529.13      5382980.08
       3489529.1      5382978.25      3489528.79      5382977.04
      3489528.79      5382975.26      3489527.59      5382964.38
#Sta/Elev= 14
       0  402.55   8.209   402.1   8.374  401.87   8.619  401.61   8.629  401.61
  10.066  401.39  10.076  401.39  10.523  401.34  10.584  401.34  10.594  401.33
  10.982  401.39  11.354  401.71  12.054  401.89  13.134  402.67
#Mann= 3 , 0 , 0
       0     .05       0   8.374     .04       0  12.054     .05       0
Bank Sta=8.374,12.054
XS Rating Curve= 0 ,0
Exp/Cntr=0.3,0.1

Type RM Length L Ch R = 1 ,239     ,16.94,16.94,16.94
XS GIS Cut Line= 6
      3489607.48      5383004.57      3489607.14      5383003.88
      3489607.42      5383003.59      3489607.64      5383003.06
      3489609.01      5383000.97      3489617.09      5382984.61
#Sta/Elev= 13
       0  401.96    .769  401.02   1.165  400.76   1.175  400.76   1.685  400.64
   1.768  400.64   1.788  400.63   2.232  400.75   2.252  400.75   3.106  401.05
   3.116  401.05   4.294  401.73   22.54  401.82
#Mann= 3 , 0 , 0
       0     .05       0    .769     .04       0   3.106     .05       0
Bank Sta=0.769,3.106
XS Rating Curve= 0 ,0
Exp/Cntr=0.3,0.1

Type RM Length L Ch R = 1 ,237     ,55.005,55.005,55.005
XS GIS Cut Line= 6
      3489614.05      5383016.07      3489620.27      5383009.53
      3489620.65      5383009.76      3489621.02      5383009.31
      3489622.33      5383008.11      3489627.87       5383002.2
#Sta/Elev= 15
       0  404.54   8.098  402.03   9.027  401.04   9.422  400.22   9.472  400.22
  10.054  400.04  10.074  400.03  10.648  400.07  11.037   400.1  11.822   400.2
  11.842   400.2   12.31  400.55   12.33  400.55  13.083  401.53  19.951  404.55
#Mann= 3 , 0 , 0
       0     .05       0   8.098     .04       0  13.083     .05       0
Bank Sta=8.098,13.083
XS Rating Curve= 0 ,0
Exp/Cntr=0.3,0.1

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
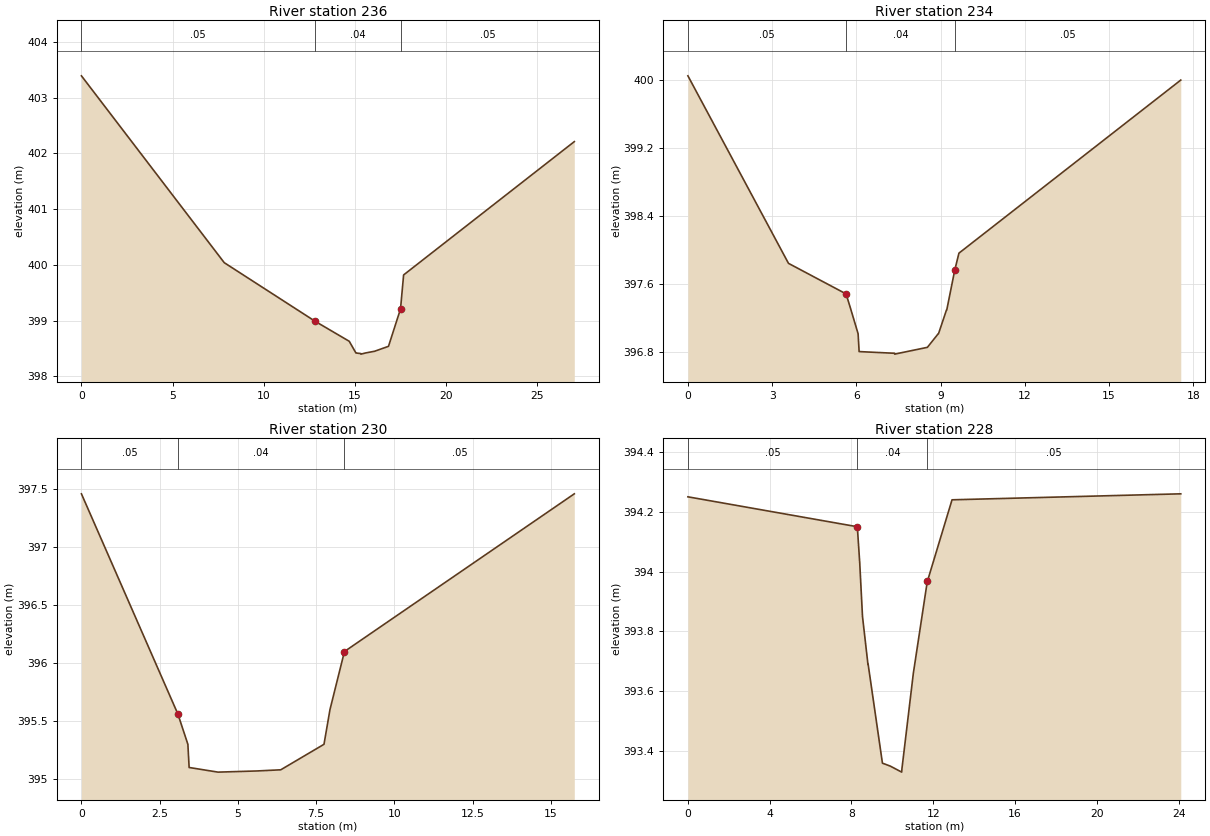
Type RM Length L Ch R = 1 ,236     ,51.87,51.87,51.87
XS GIS Cut Line= 6
      3489722.55      5383049.51      3489725.27      5383042.17
       3489727.4      5383037.67      3489727.81      5383035.84
      3489729.22      5383033.24      3489732.69      5383024.55
#Sta/Elev= 15
       0  403.39   7.828  400.04  12.806  398.99  14.682  398.63  15.049  398.42
  15.059  398.42  15.318  398.41  15.328   398.4  15.561  398.42  16.049  398.45
  16.059  398.45  16.833  398.54  17.492  399.21  17.662  399.82  27.019  402.21
#Mann= 3 , 0 , 0
       0     .05       0  12.806     .04       0  17.492     .05       0
Bank Sta=12.806,17.492
XS Rating Curve= 0 ,0
Exp/Cntr=0.3,0.1

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
Type RM Length L Ch R = 1 ,234     ,80.95,80.95,80.95
XS GIS Cut Line= 6
      3489831.52      5383032.89      3489831.22      5383029.32
      3489830.81      5383027.31      3489830.77      5383024.43
      3489830.53      5383023.36      3489829.61      5383015.51
#Sta/Elev= 17
       0  400.05   3.583  397.84   5.634  397.48   5.784  397.32   6.064  397.01
     6.1   396.8   7.361  396.78   7.371  396.77   7.511  396.78   8.532  396.85
   8.918  397.01   8.928  397.01   9.212  397.29   9.222  397.29   9.507  397.76
   9.656  397.96  17.559     400
#Mann= 3 , 0 , 0
       0     .05       0   5.634     .04       0   9.507     .05       0
Bank Sta=5.634,9.507
XS Rating Curve= 0 ,0
Exp/Cntr=0.3,0.1

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
Type RM Length L Ch R = 1 ,230     ,97.11,97.11,97.11
XS GIS Cut Line= 6
      3490016.51      5382899.16      3490014.05       5382897.3
      3490013.82      5382897.08      3490011.37      5382895.42
      3490009.72      5382894.23      3490003.47      5382890.37
#Sta/Elev= 11
       0  397.46   3.084  395.56   3.402   395.3   3.442   395.1   4.364  395.06
   5.604  395.07    6.37  395.08   7.752   395.3   7.944   395.6   8.406   396.1
  15.752  397.46
#Mann= 3 , 0 , 0
       0     .05       0   3.084     .04       0   8.406     .05       0
Bank Sta=3.084,8.406
XS Rating Curve= 0 ,0
Exp/Cntr=0.3,0.1

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
Type RM Length L Ch R = 1 ,228     ,91.437,91.437,91.437
XS GIS Cut Line= 6
      3490020.02      5382714.27      3490012.61      5382710.56
      3490010.63      5382709.76      3490009.68      5382708.95
      3490008.61      5382708.43       3489998.2      5382704.33
#Sta/Elev= 15
       0  394.25   8.287  394.15   8.404  394.03    8.54  393.85   8.807  393.69
   8.817  393.69   9.515  393.36   9.903  393.35  10.457  393.33  10.467  393.34
  11.026  393.66  11.715  393.97  11.725  393.97  12.919  394.24  24.107  394.26
#Mann= 3 , 0 , 0
       0     .05       0   8.287     .04       0  11.715     .05       0
Bank Sta=8.287,11.715
XS Rating Curve= 0 ,0
Exp/Cntr=0.3,0.1