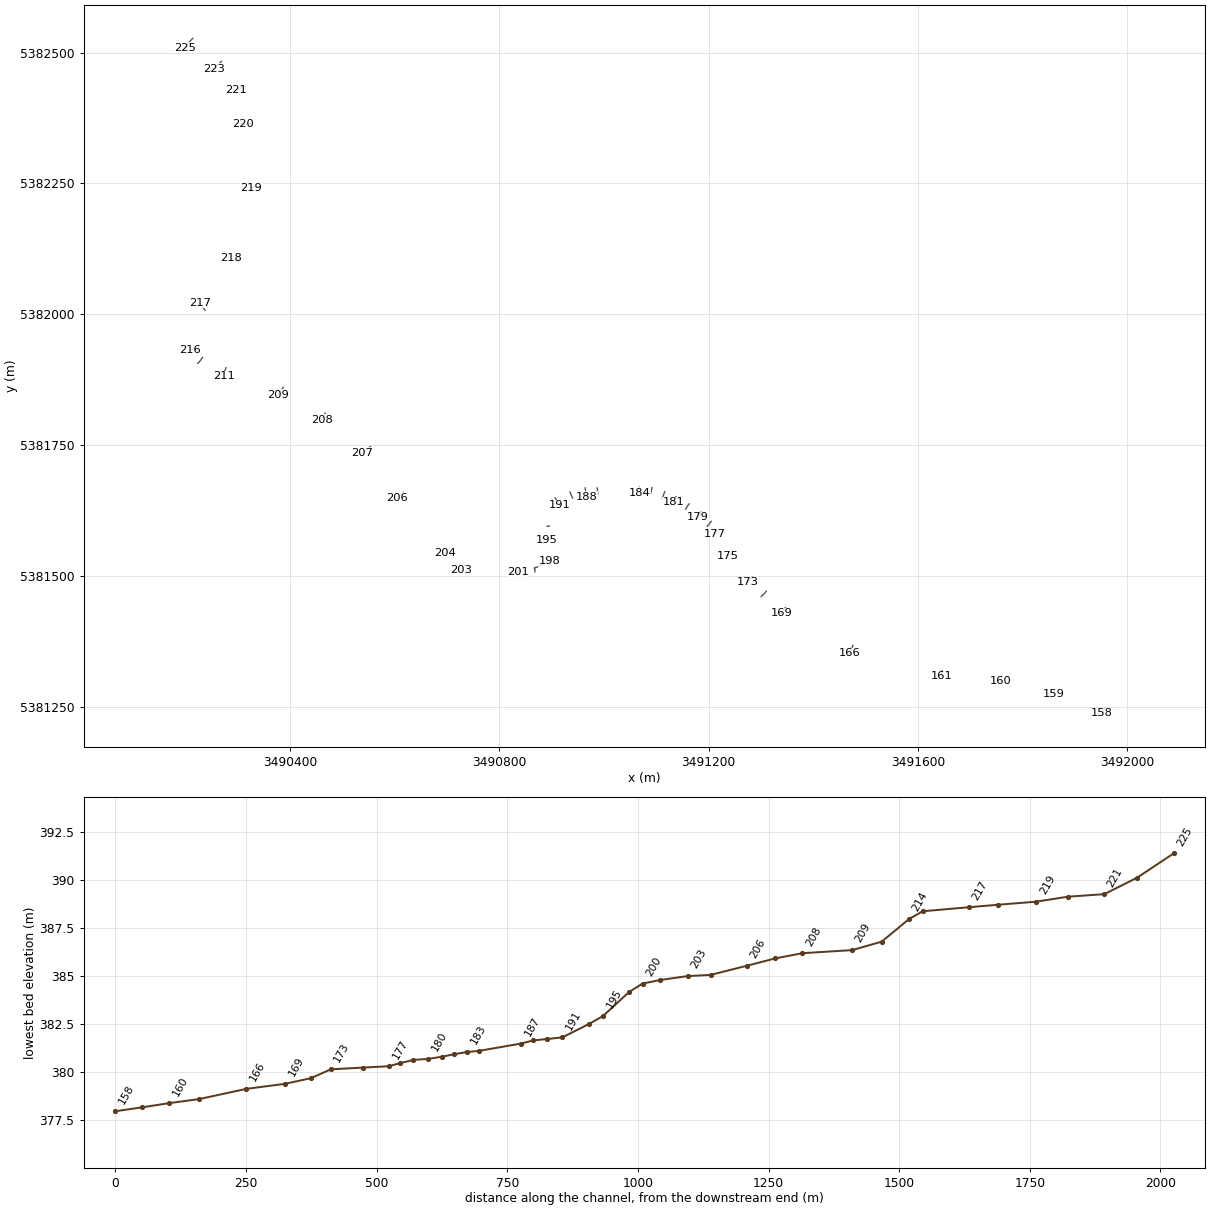
HEC-RAS study Amm_final.prj: Amm_final

--- Amm_final.g04 (geometry) --- (continued)

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
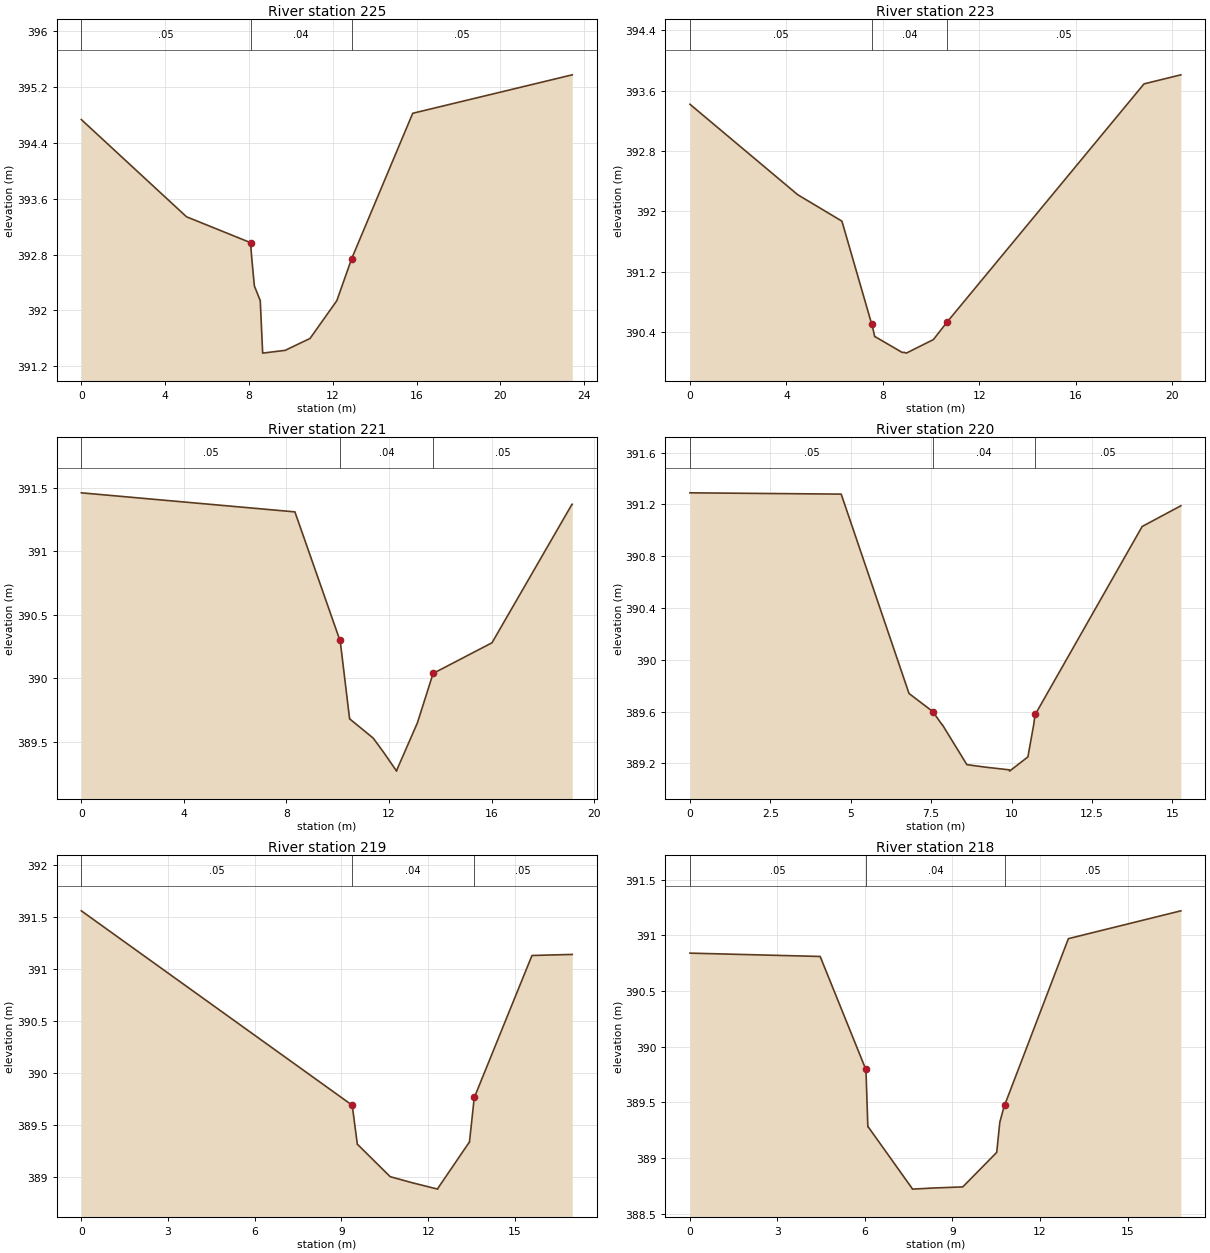
Type RM Length L Ch R = 1 ,225     ,70.35,70.35,70.35
XS GIS Cut Line= 6
      3490213.94      5382527.34      3490210.65      5382523.55
      3490208.45      5382521.43      3490208.23      5382521.02
      3490205.36      5382517.74      3490198.66      5382509.62
#Sta/Elev= 14
       0  394.73   5.019  393.34   8.074  392.97   8.141  392.72   8.258  392.35
   8.539  392.14   8.653  391.39   9.729  391.43  10.425  391.53  10.914   391.6
  12.192  392.14  12.899  392.74  15.814  394.82  23.427  395.37
#Mann= 3 , 0 , 0
       0     .05       0   8.074     .04       0  12.899     .05       0
Bank Sta=8.074,12.899
XS Rating Curve= 0 ,0
Exp/Cntr=0.3,0.1

Type RM Length L Ch R = 1 ,223     ,62.5,62.5,62.5
XS GIS Cut Line= 6
      3490268.82      5382483.41      3490264.87       5382478.5
      3490263.08      5382476.83       3490263.2       5382476.7
      3490255.67      5382470.36       3490254.9      5382469.04
#Sta/Elev= 14
       0  393.42   4.471  392.22   6.302  391.87   7.541   390.5   7.551   390.5
   7.659  390.34   7.669  390.34   8.796  390.13   8.888  390.13   8.973  390.12
  10.096   390.3  10.658  390.53  18.829  393.69  20.357  393.81
#Mann= 3 , 0 , 0
       0     .05       0   7.551     .04       0  10.658     .05       0
Bank Sta=7.551,10.658
XS Rating Curve= 0 ,0
Exp/Cntr=0.3,0.1

Type RM Length L Ch R = 1 ,221     ,69.3,69.3,69.3
XS GIS Cut Line= 6
      3490314.19      5382436.29      3490306.64      5382432.77
      3490305.18       5382431.8      3490302.41       5382430.7
      3490299.87      5382429.32      3490297.02      5382428.06
#Sta/Elev= 16
       0  391.46    8.33  391.31  10.083   390.3  10.093   390.3  10.463  389.68
  10.473  389.68  11.382  389.53  11.783  389.42  12.296  389.27  12.306  389.28
  13.107  389.65   13.72  390.04   13.73  390.04  16.016  390.28  19.136  391.37
  19.146  391.37
#Mann= 3 , 0 , 0
       0     .05       0  10.093     .04       0   13.73     .05       0
Bank Sta=10.093,13.73
XS Rating Curve= 0 ,0
Exp/Cntr=0.3,0.1

Type RM Length L Ch R = 1 ,220     ,60.75,60.75,60.75
XS GIS Cut Line= 6
      3490324.62      5382364.02      3490319.92       5382363.9
      3490316.12      5382363.23      3490314.07      5382363.36
      3490310.79      5382362.85      3490309.59      5382362.94
#Sta/Elev= 16
       0  391.29   4.702  391.28    6.81  389.74    7.55   389.6   7.833   389.5
   7.843   389.5   8.609  389.19   9.208  389.17   9.926  389.15   9.936  389.14
  10.506  389.25  10.687   389.5  10.729  389.58  10.739  389.58  14.058  391.03
  15.261  391.19
#Mann= 3 , 0 , 0
       0     .05       0    7.55     .04       0  10.729     .05       0
Bank Sta=7.55,10.729
XS Rating Curve= 0 ,0
Exp/Cntr=0.3,0.1

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
Type RM Length L Ch R = 1 ,219     ,73.23,73.23,73.23
XS GIS Cut Line= 6
      3490341.25      5382243.84      3490329.89      5382242.57
      3490329.07       5382242.3      3490327.83      5382242.45
      3490325.92      5382241.91      3490324.53      5382241.83
#Sta/Elev= 15
       0  391.56    9.36  389.69    9.37  389.69   9.549  389.31   9.559  389.31
  10.684     389  11.466  388.94  12.329  388.88  12.339  388.89  13.416  389.33
  13.426  389.33  13.596  389.77  13.606  389.77   15.59  391.13  16.983  391.14
#Mann= 3 , 0 , 0
       0     .05       0    9.37     .04       0  13.596     .05       0
Bank Sta=9.37,13.596
XS Rating Curve= 0 ,0
Exp/Cntr=0.3,0.1

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
Type RM Length L Ch R = 1 ,218     ,56.28,56.28,56.28
XS GIS Cut Line= 6
      3490301.43      5382099.79      3490297.54      5382101.98
      3490295.96       5382102.3      3490294.57      5382102.87
      3490293.25      5382103.99      3490286.74      5382107.45
#Sta/Elev= 16
       0  390.84   4.464  390.81   6.022   389.8   6.032   389.8   6.099  389.28
   6.109  389.28   7.607  388.73   7.627  388.72   8.335  388.73   9.353  388.74
  10.516  389.05  10.622  389.32  10.786  389.48  10.796  389.48  12.973  390.97
  16.829  391.22
#Mann= 3 , 0 , 0
       0     .05       0   6.032     .04       0  10.796     .05       0
Bank Sta=6.032,10.796
XS Rating Curve= 0 ,0
Exp/Cntr=0.3,0.1

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
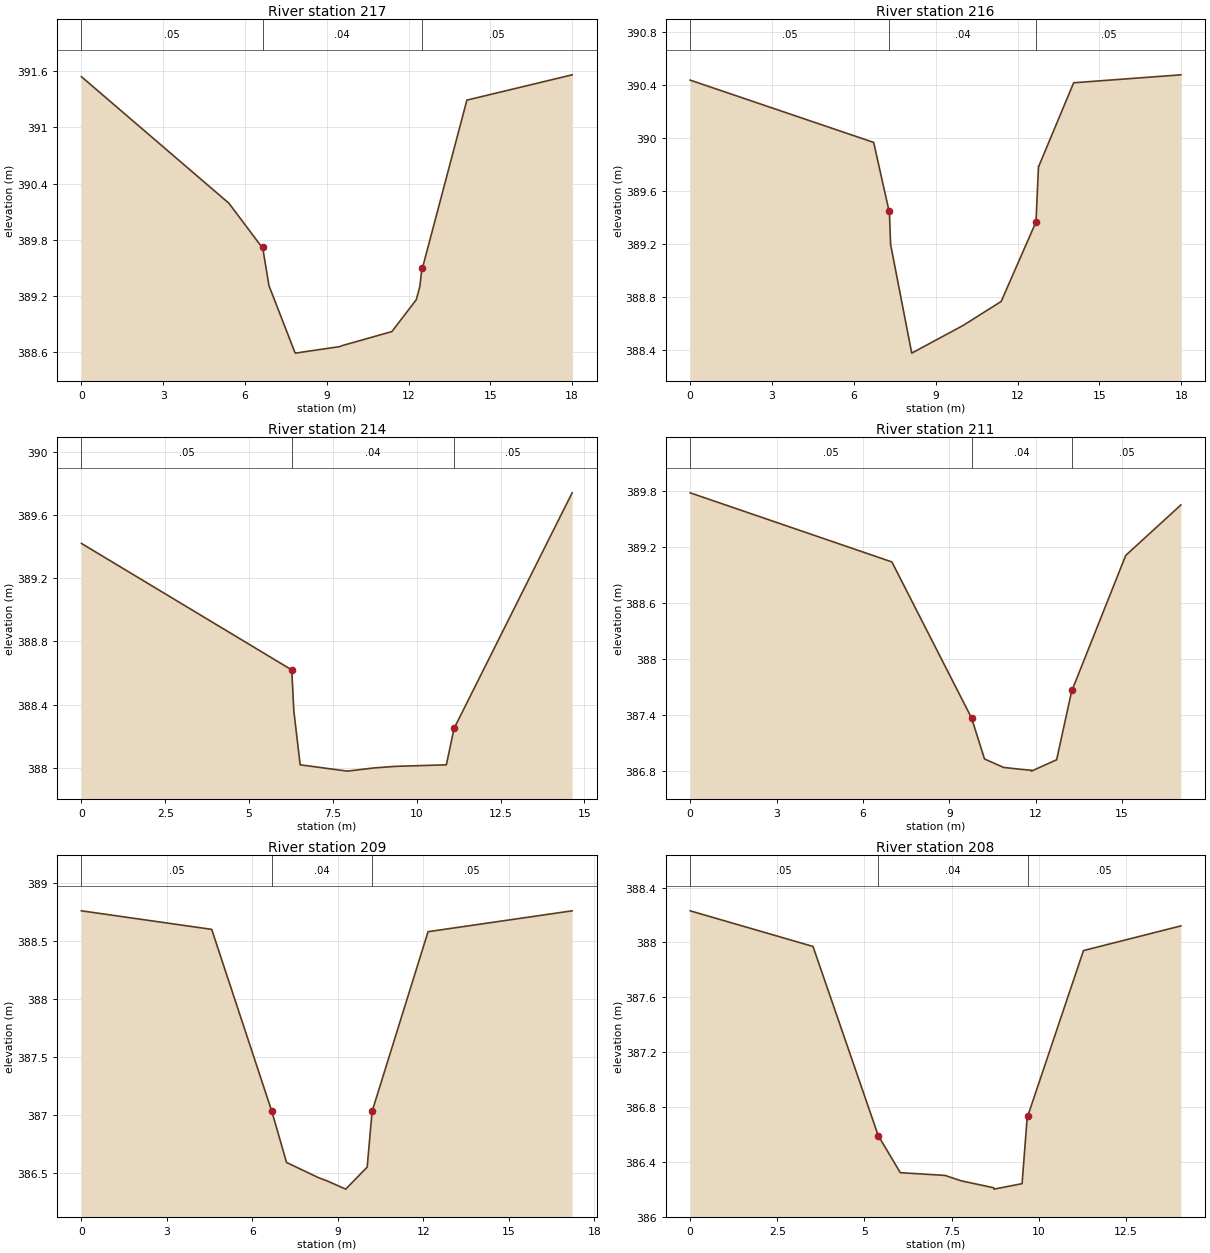
Type RM Length L Ch R = 1 ,217     ,87.91,87.91,87.91
XS GIS Cut Line= 6
      3490237.72      5382007.34      3490233.94      5382012.78
      3490233.43      5382013.88      3490231.37      5382016.76
      3490230.95      5382017.55      3490227.74      5382022.26
#Sta/Elev= 16
       0  391.54   5.409  390.19   6.624  389.72   6.647  389.72    6.88  389.31
   7.828   388.6   7.848  388.59   9.484  388.66   9.564  388.67   11.39  388.82
  12.284  389.16  12.415   389.3  12.493   389.5  12.513   389.5  14.142  391.29
  18.003  391.56
#Mann= 3 , 0 , 0
       0     .05       0   6.647     .04       0  12.493     .05       0
Bank Sta=6.647,12.493
XS Rating Curve= 0 ,0
Exp/Cntr=0.3,0.1

Type RM Length L Ch R = 1 ,216     ,25.96,25.96,25.96
XS GIS Cut Line= 6
      3490225.56      5381937.15      3490217.89      5381934.68
      3490216.27       5381933.7      3490214.95      5381933.28
       3490212.7      5381931.91      3490208.78      5381931.64
#Sta/Elev= 13
       0  390.44   6.726  389.97   7.292  389.45   7.302  389.45   7.347   389.2
   8.121  388.38  10.015  388.59    11.4  388.77  12.676  389.37  12.768  389.79
  12.778  389.79  14.057  390.42  17.987  390.48
#Mann= 3 , 0 , 0
       0     .05       0   7.302     .04       0  12.676     .05       0
Bank Sta=7.302,12.676
XS Rating Curve= 0 ,0
Exp/Cntr=0.3,0.1

Type RM Length L Ch R = 1 ,214     ,52.51,52.51,52.51
XS GIS Cut Line= 6
      3490232.91      5381917.51      3490229.21      5381912.37
      3490229.04      5381912.29      3490228.27      5381911.11
       3490226.3      5381908.62      3490223.51      5381906.47
#Sta/Elev= 10
       0  389.42   6.273  388.62   6.336  388.36   6.524  388.02   7.933  387.98
   8.718     388   9.356  388.01  10.885  388.02  11.115  388.25  14.637  389.74
#Mann= 3 , 0 , 0
       0     .05       0   6.273     .04       0  11.115     .05       0
Bank Sta=6.273,11.115
XS Rating Curve= 0 ,0
Exp/Cntr=0.3,0.1

Type RM Length L Ch R = 1 ,211     ,56.53,56.53,56.53
XS GIS Cut Line= 6
      3490277.52      5381897.94      3490275.38      5381891.27
      3490274.38      5381886.98      3490274.48      5381886.61
      3490273.46      5381883.53      3490273.15      5381881.64
#Sta/Elev= 14
       0  389.78   7.005  389.04    9.77  387.37  10.222  386.93  10.882  386.84
  11.459  386.82   11.84  386.81   11.85   386.8  12.715  386.92  12.725  386.92
  13.257  387.67  13.267  387.67  15.126  389.11  17.041  389.65
#Mann= 3 , 0 , 0
       0     .05       0    9.77     .04       0  13.267     .05       0
Bank Sta=9.77,13.267
XS Rating Curve= 0 ,0
Exp/Cntr=0.3,0.1

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
Type RM Length L Ch R = 1 ,209     ,95.28,95.28,95.28
XS GIS Cut Line= 6
      3490387.09      5381860.47      3490383.43      5381854.88
      3490382.38      5381853.64      3490382.27      5381853.34
      3490381.32      5381852.09      3490377.74      5381846.05
#Sta/Elev= 11
       0  388.76   4.571   388.6   6.682  387.03   7.198  386.59   8.309  386.46
   8.629  386.43   9.275  386.36  10.028  386.55    10.2  387.03  12.164  388.58
  17.221  388.76
#Mann= 3 , 0 , 0
       0     .05       0   6.682     .04       0    10.2     .05       0
Bank Sta=6.682,10.2
XS Rating Curve= 0 ,0
Exp/Cntr=0.3,0.1

Type RM Length L Ch R = 1 ,208     ,51.775,51.775,51.775
XS GIS Cut Line= 6
      3490467.35      5381811.18      3490465.71      5381808.06
      3490464.14      5381804.62      3490463.86      5381804.24
      3490462.23      5381801.18      3490460.78      5381798.79
#Sta/Elev= 13
       0  388.23   3.525  387.97   5.397  386.59    6.03  386.32   7.312   386.3
   7.784  386.26   8.709  386.21   8.719   386.2   9.524  386.24   9.673  386.73
   9.683  386.73  11.286  387.94  14.081  388.12
#Mann= 3 , 0 , 0
       0     .05       0   5.397     .04       0   9.683     .05       0
Bank Sta=5.397,9.683
XS Rating Curve= 0 ,0
Exp/Cntr=0.3,0.1

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
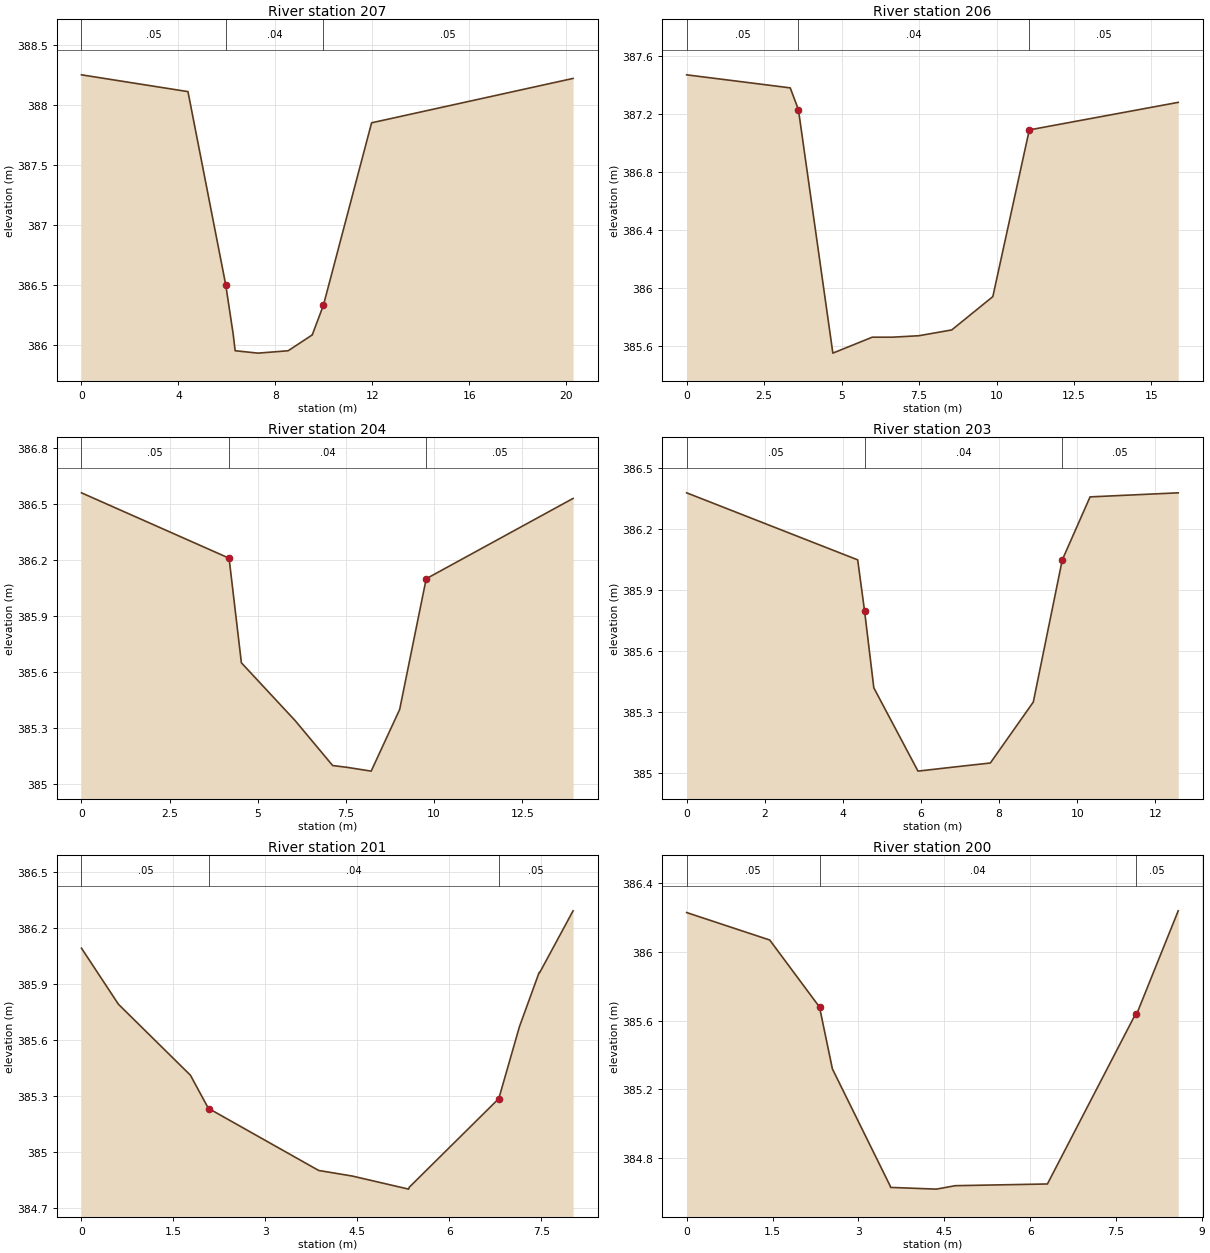
Type RM Length L Ch R = 1 ,207     ,54.055,54.055,54.055
XS GIS Cut Line= 6
      3490553.66      5381747.38      3490548.92      5381743.78
      3490548.82      5381743.49      3490545.71      5381741.51
      3490544.28      5381740.13      3490537.73      5381735.01
#Sta/Elev= 13
       0  388.25   4.394  388.11   5.952   386.5   6.259  386.09   6.341  385.95
    7.28  385.93   7.922  385.94    8.53  385.95   9.509  386.08   9.519  386.08
   9.985  386.33  11.972  387.85  20.286  388.22
#Mann= 3 , 0 , 0
       0     .05       0   5.952     .04       0   9.985     .05       0
Bank Sta=5.952,9.985
XS Rating Curve= 0 ,0
Exp/Cntr=0.3,0.1

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
Type RM Length L Ch R = 1 ,206     ,69.875,69.875,69.875
XS GIS Cut Line= 6
      3490616.25      5381659.95      3490613.76      5381657.72
      3490613.53      5381657.59      3490611.82      5381655.93
      3490609.91      5381654.22       3490604.4      5381649.42
#Sta/Elev= 11
       0  387.47   3.343  387.38   3.607  387.23   4.718  385.55    5.99  385.66
   6.645  385.66   7.493  385.67   8.555  385.71   9.881  385.94  11.057  387.09
  15.863  387.28
#Mann= 3 , 0 , 0
       0     .05       0   3.607     .04       0  11.057     .05       0
Bank Sta=3.607,11.057
XS Rating Curve= 0 ,0
Exp/Cntr=0.3,0.1

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
Type RM Length L Ch R = 1 ,204     ,43.65,43.65,43.65
XS GIS Cut Line= 6
      3490706.68      5381553.21      3490703.18      5381550.34
      3490700.45      5381547.88      3490699.92      5381547.27
      3490699.27      5381546.89      3490696.29      5381543.98
#Sta/Elev= 10
       0  386.56   4.186  386.21   4.535  385.65   6.062  385.34   7.123   385.1
   7.542  385.09   8.216  385.07   9.024   385.4   9.777   386.1  13.942  386.53
#Mann= 3 , 0 , 0
       0     .05       0   4.186     .04       0   9.777     .05       0
Bank Sta=4.186,9.777
XS Rating Curve= 0 ,0
Exp/Cntr=0.3,0.1

Type RM Length L Ch R = 1 ,203     ,54.03,54.03,54.03
XS GIS Cut Line= 6
      3490734.69      5381520.53      3490731.33      5381517.13
       3490728.6       5381514.1      3490728.01      5381513.65
      3490727.63      5381513.05      3490726.09       5381511.4
#Sta/Elev= 11
       0  386.38   4.379  386.05   4.554   385.8   4.792  385.42   5.923  385.01
   6.835  385.03   7.775  385.05   8.875  385.35   9.617  386.05  10.328  386.36
  12.585  386.38
#Mann= 3 , 0 , 0
       0     .05       0   4.554     .04       0   9.617     .05       0
Bank Sta=4.554,9.617
XS Rating Curve= 0 ,0
Exp/Cntr=0.3,0.1

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
Type RM Length L Ch R = 1 ,201     ,32.46,32.46,32.46
XS GIS Cut Line= 6
      3490836.24      5381515.64      3490836.02      5381515.08
      3490836.12      5381513.91      3490835.84      5381511.33
      3490835.52      5381510.47      3490835.67      5381507.83
#Sta/Elev= 15
       0  386.09    .602  385.79   1.776  385.41   2.073  385.23   2.083  385.23
   3.867   384.9   4.416  384.87   5.334   384.8   5.344  384.81    6.79  385.28
     6.8  385.28   7.141  385.67   7.462  385.96   7.472  385.96   8.015  386.29
#Mann= 3 , 0 , 0
       0     .05       0   2.083     .04       0     6.8     .05       0
Bank Sta=2.083,6.8
XS Rating Curve= 0 ,0
Exp/Cntr=0.3,0.1

Type RM Length L Ch R = 1 ,200     ,25.85,25.85,25.85
XS GIS Cut Line= 6
      3490867.44      5381515.91       3490867.4      5381514.46
      3490867.93      5381512.45      3490867.76      5381511.67
      3490868.03      5381511.48      3490867.78      5381507.63
#Sta/Elev= 12
       0  386.23   1.451  386.07    2.32  385.68   2.545  385.32   3.552  384.64
   3.562  384.63   4.361  384.62   4.691  384.64     6.3  384.65    7.84  385.64
    7.86  385.64   8.584  386.24
#Mann= 3 , 0 , 0
       0     .05       0    2.32     .04       0    7.84     .05       0
Bank Sta=2.32,7.84
XS Rating Curve= 0 ,0
Exp/Cntr=0.3,0.1

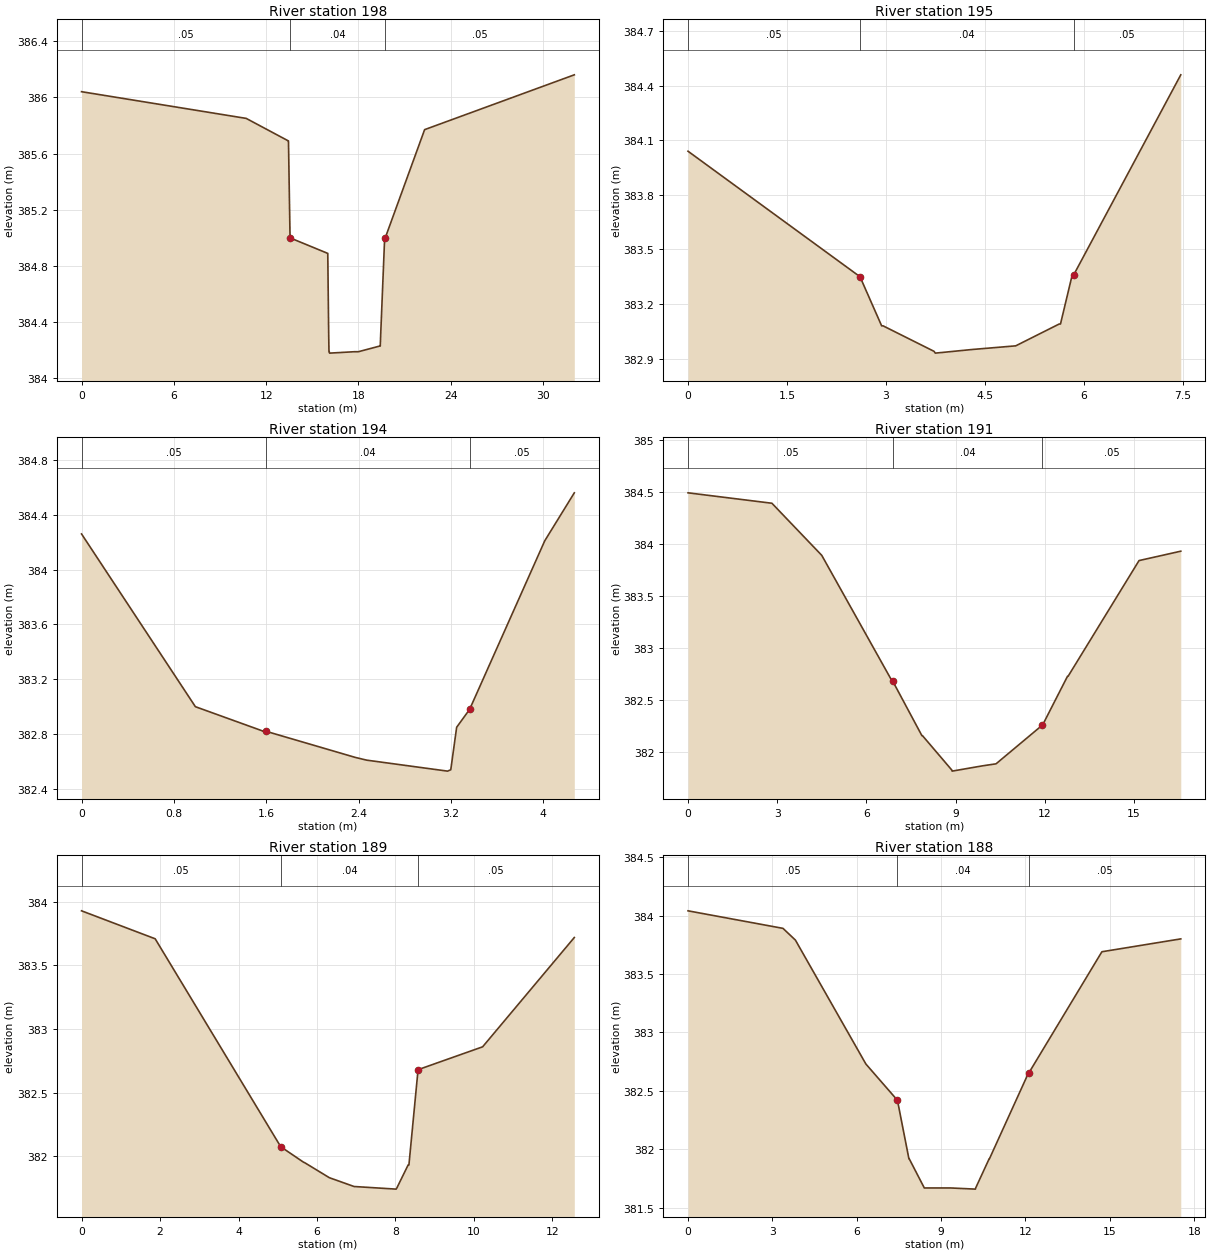
Type RM Length L Ch R = 1 ,198     ,49.94,49.94,49.94
XS GIS Cut Line= 6
      3490866.89      5381514.68       3490879.3      5381519.83
      3490881.78      5381520.74      3490884.75      5381522.24
      3490884.87      5381522.49      3490895.84      5381528.05
#Sta/Elev= 20
       0  386.04  10.703  385.85  13.441  385.69  13.451  385.69  13.553     385
  15.995  384.89  16.005  384.89  16.063  384.33  16.083  384.19  16.103  384.19
  16.125  384.18  17.736  384.19  17.994  384.19  19.371  384.23  19.416  384.23
  19.452  384.33  19.703     385  19.741     385    22.3  385.77  32.031  386.16
#Mann= 3 , 0 , 0
       0     .05       0  13.553     .04       0  19.741     .05       0
Bank Sta=13.553,19.741
XS Rating Curve= 0 ,0
Exp/Cntr=0.3,0.1

Type RM Length L Ch R = 1 ,195     ,25.87,25.87,25.87
XS GIS Cut Line= 6
      3490883.24      5381572.44      3490886.65      5381570.92
      3490886.97      5381570.46      3490887.58      5381570.21
      3490888.23      5381569.66      3490889.72      5381568.98
#Sta/Elev= 13
       0  384.04   2.608  383.35   2.936  383.08   2.958  383.08    3.73  382.94
    3.75  382.93    4.31  382.95   4.969  382.97   5.628  383.09   5.648  383.09
   5.826  383.36   5.848  383.36   7.472  384.46
#Mann= 3 , 0 , 0
       0     .05       0   2.608     .04       0   5.848     .05       0
Bank Sta=2.608,5.848
XS Rating Curve= 0 ,0
Exp/Cntr=0.3,0.1

Type RM Length L Ch R = 1 ,194     ,51.82,51.82,51.82
XS GIS Cut Line= 6
       3490891.3        5381595.      3490892.28      5381594.89
      3490892.81       5381595.2      3490894.37      5381595.14
      3490894.42      5381594.96      3490895.23       5381595.2
#Sta/Elev= 12
       0  384.26    .986     383   1.578  382.82     1.6  382.82   2.371  382.63
    2.47  382.61    3.17  382.53   3.198  382.54   3.249  382.85   3.361  382.98
   4.012  384.21   4.268  384.56
#Mann= 3 , 0 , 0
       0     .05       0     1.6     .04       0   3.361     .05       0
Bank Sta=1.6,3.361
XS Rating Curve= 0 ,0
Exp/Cntr=0.3,0.1

Type RM Length L Ch R = 1 ,191     ,28.45,28.45,28.45
XS GIS Cut Line= 6
      3490906.71      5381649.13      3490908.02      5381646.63
      3490911.57       5381641.8      3490912.97      5381639.12
      3490913.11      5381638.29      3490915.41      5381635.27
#Sta/Elev= 17
       0  384.49   2.822  384.39   4.499  383.89   6.872  382.68   6.892  382.68
   7.868  382.16   7.888  382.16   8.874  381.83   8.884  381.82   9.891  381.87
  10.361  381.89  11.913  382.26  11.923  382.26  12.765  382.73  12.785  382.73
  15.171  383.84  16.575  383.93
#Mann= 3 , 0 , 0
       0     .05       0   6.892     .04       0  11.923     .05       0
Bank Sta=6.892,11.923
XS Rating Curve= 0 ,0
Exp/Cntr=0.3,0.1

Type RM Length L Ch R = 1 ,189     ,27.85,27.85,27.85
XS GIS Cut Line= 6
      3490934.96      5381660.17      3490937.33      5381655.03
      3490937.95       5381652.8      3490938.22      5381652.63
      3490939.08      5381650.96      3490939.92      5381648.78
#Sta/Elev= 16
       0  383.93   1.876  383.71   5.083  382.07   5.093  382.07   5.666  381.95
   5.676  381.95   6.315  381.83   6.951  381.76   6.979  381.76   8.017  381.74
   8.037  381.75   8.323  381.93   8.343  381.93   8.576  382.68  10.222  382.86
  12.558  383.72
#Mann= 3 , 0 , 0
       0     .05       0   5.083     .04       0   8.576     .05       0
Bank Sta=5.083,8.576
XS Rating Curve= 0 ,0
Exp/Cntr=0.3,0.1

Type RM Length L Ch R = 1 ,188     ,22.82,22.82,22.82
XS GIS Cut Line= 6
      3490963.97      5381668.15      3490965.14       5381660.4
      3490964.97      5381659.89      3490965.06       5381659.2
      3490965.24      5381659.04      3490966.12      5381650.93
#Sta/Elev= 17
       0  384.04   3.377  383.89   3.818  383.79   6.325  382.73   7.447  382.42
   7.855  381.92   7.865  381.92   8.403  381.67    9.34  381.67   10.22  381.66
   10.23  381.67   10.71  381.92   10.72  381.92  12.101  382.65  12.111  382.65
  14.718  383.69  17.523   383.8
#Mann= 3 , 0 , 0
       0     .05       0   7.447     .04       0  12.111     .05       0
Bank Sta=7.447,12.111
XS Rating Curve= 0 ,0
Exp/Cntr=0.3,0.1

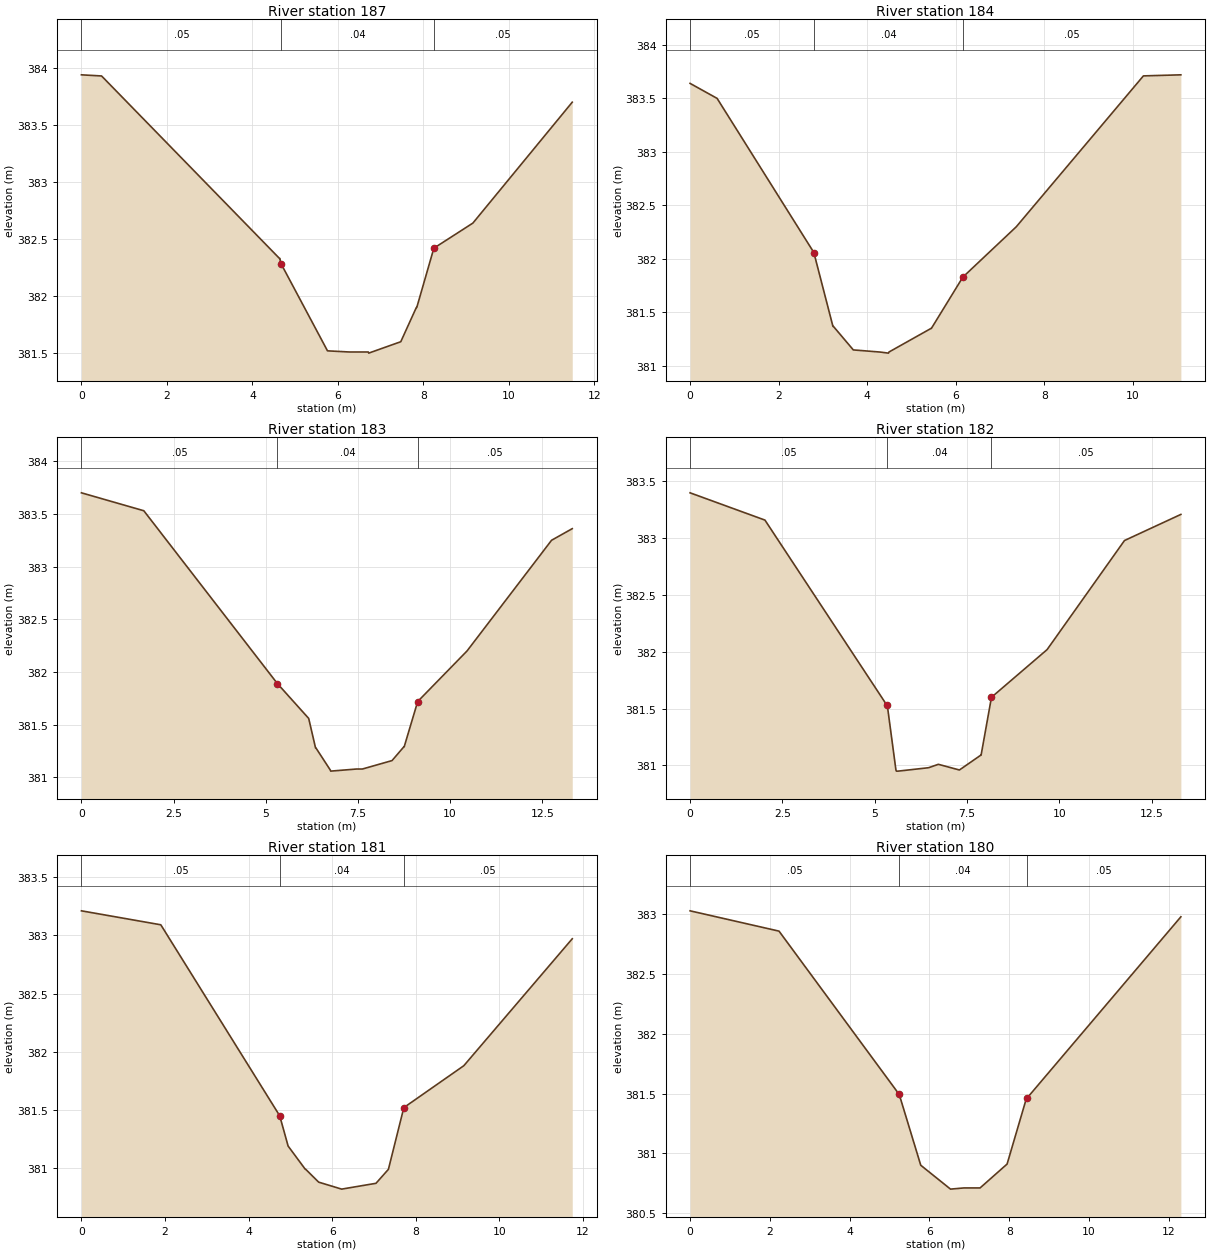
Type RM Length L Ch R = 1 ,187     ,80.32,80.32,80.32
XS GIS Cut Line= 6
      3490987.13      5381668.12      3490987.56      5381663.51
      3490987.51      5381662.41      3490987.71      5381661.94
      3490987.97        5381660.       3490988.2      5381656.77
#Sta/Elev= 16
       0  383.94    .471  383.93   4.634  382.33   4.644  382.33   4.666  382.28
   4.676  382.28   5.757  381.52   6.268  381.51   6.711  381.51   6.721   381.5
   7.472   381.6   7.836   381.9   7.846   381.9   8.246  382.42   9.159  382.64
  11.484   383.7
#Mann= 3 , 0 , 0
       0     .05       0   4.676     .04       0   8.246     .05       0
Bank Sta=4.676,8.246
XS Rating Curve= 0 ,0
Exp/Cntr=0.3,0.1

Type RM Length L Ch R = 1 ,184     ,22.32,22.32,22.32
XS GIS Cut Line= 6
      3491067.84       5381669.6      3491068.13      5381665.25
      3491068.01      5381664.31      3491068.26      5381663.64
      3491067.97      5381662.47      3491067.92      5381658.76
#Sta/Elev= 15
       0  383.64     .61   383.5   2.794  382.06   3.225  381.37   3.235  381.37
   3.685  381.15    4.29  381.13   4.479  381.12   4.489  381.13   5.436  381.35
   5.446  381.35   6.158  381.83   7.363   382.3  10.234  383.71   11.08  383.72
#Mann= 3 , 0 , 0
       0     .05       0   2.794     .04       0   6.158     .05       0
Bank Sta=2.794,6.158
XS Rating Curve= 0 ,0
Exp/Cntr=0.3,0.1

Type RM Length L Ch R = 1 ,183     ,24.85,24.85,24.85
XS GIS Cut Line= 6
      3491091.77      5381668.86      3491090.05      5381661.66
       3491090.2      5381661.61      3491090.05      5381660.82
      3491089.66      5381660.28      3491088.86      5381656.17
#Sta/Elev= 17
       0   383.7   1.692  383.53   5.317  381.89   6.165  381.56   6.351  381.28
   6.361  381.28   6.752  381.07   6.762  381.06   7.464  381.08   7.622  381.08
   8.426  381.16   8.745  381.29   8.755  381.29   9.122  381.72  10.461   382.2
  12.754  383.25  13.315  383.36
#Mann= 3 , 0 , 0
       0     .05       0   5.317     .04       0   9.122     .05       0
Bank Sta=5.317,9.122
XS Rating Curve= 0 ,0
Exp/Cntr=0.3,0.1

Type RM Length L Ch R = 1 ,182     ,22.84,22.84,22.84
XS GIS Cut Line= 6
        3491116.      5381661.05      3491113.59      5381654.19
      3491113.32      5381653.68      3491113.35       5381653.4
      3491112.64      5381652.07      3491111.34      5381648.69
#Sta/Elev= 16
       0   383.4   2.027  383.16    5.33  381.53    5.34  381.53   5.574  380.96
   5.588  380.95   5.633  380.95   6.458  380.98   6.723  381.01   7.293  380.96
    7.87  381.09    7.88  381.09   8.161   381.6   9.668  382.02  11.763  382.98
   13.29  383.21
#Mann= 3 , 0 , 0
       0     .05       0    5.34     .04       0   8.161     .05       0
Bank Sta=5.34,8.161
XS Rating Curve= 0 ,0
Exp/Cntr=0.3,0.1

Type RM Length L Ch R = 1 ,181     ,27.65,27.65,27.65
XS GIS Cut Line= 6
       3491137.5      5381651.68      3491135.11      5381646.55
        3491135.      5381646.01       3491134.2      5381644.81
      3491133.61       5381643.5      3491132.73      5381641.06
#Sta/Elev= 14
       0  383.21   1.899  383.09   4.744  381.45   4.945  381.19   5.357  380.99
   5.367  380.99   5.676  380.88   6.227  380.82   6.389  380.83   7.048  380.87
   7.345  380.99   7.714  381.52    9.15  381.88  11.744  382.97
#Mann= 3 , 0 , 0
       0     .05       0   4.744     .04       0   7.714     .05       0
Bank Sta=4.744,7.714
XS Rating Curve= 0 ,0
Exp/Cntr=0.3,0.1

Type RM Length L Ch R = 1 ,180     ,27.98,27.98,27.98
XS GIS Cut Line= 6
      3491162.75      5381637.67      3491161.32      5381635.96
      3491159.61       5381633.5      3491159.37        5381633.
      3491158.17       5381631.2      3491156.02      5381627.43
#Sta/Elev= 12
       0  383.03   2.229  382.86   5.225   381.5   5.235   381.5   5.781   380.9
   6.527   380.7   6.863  380.71   7.268  380.71   7.945  380.91   8.429  381.46
   8.439  381.46    12.3  382.98
#Mann= 3 , 0 , 0
       0     .05       0   5.235     .04       0   8.439     .05       0
Bank Sta=5.235,8.439
XS Rating Curve= 0 ,0
Exp/Cntr=0.3,0.1

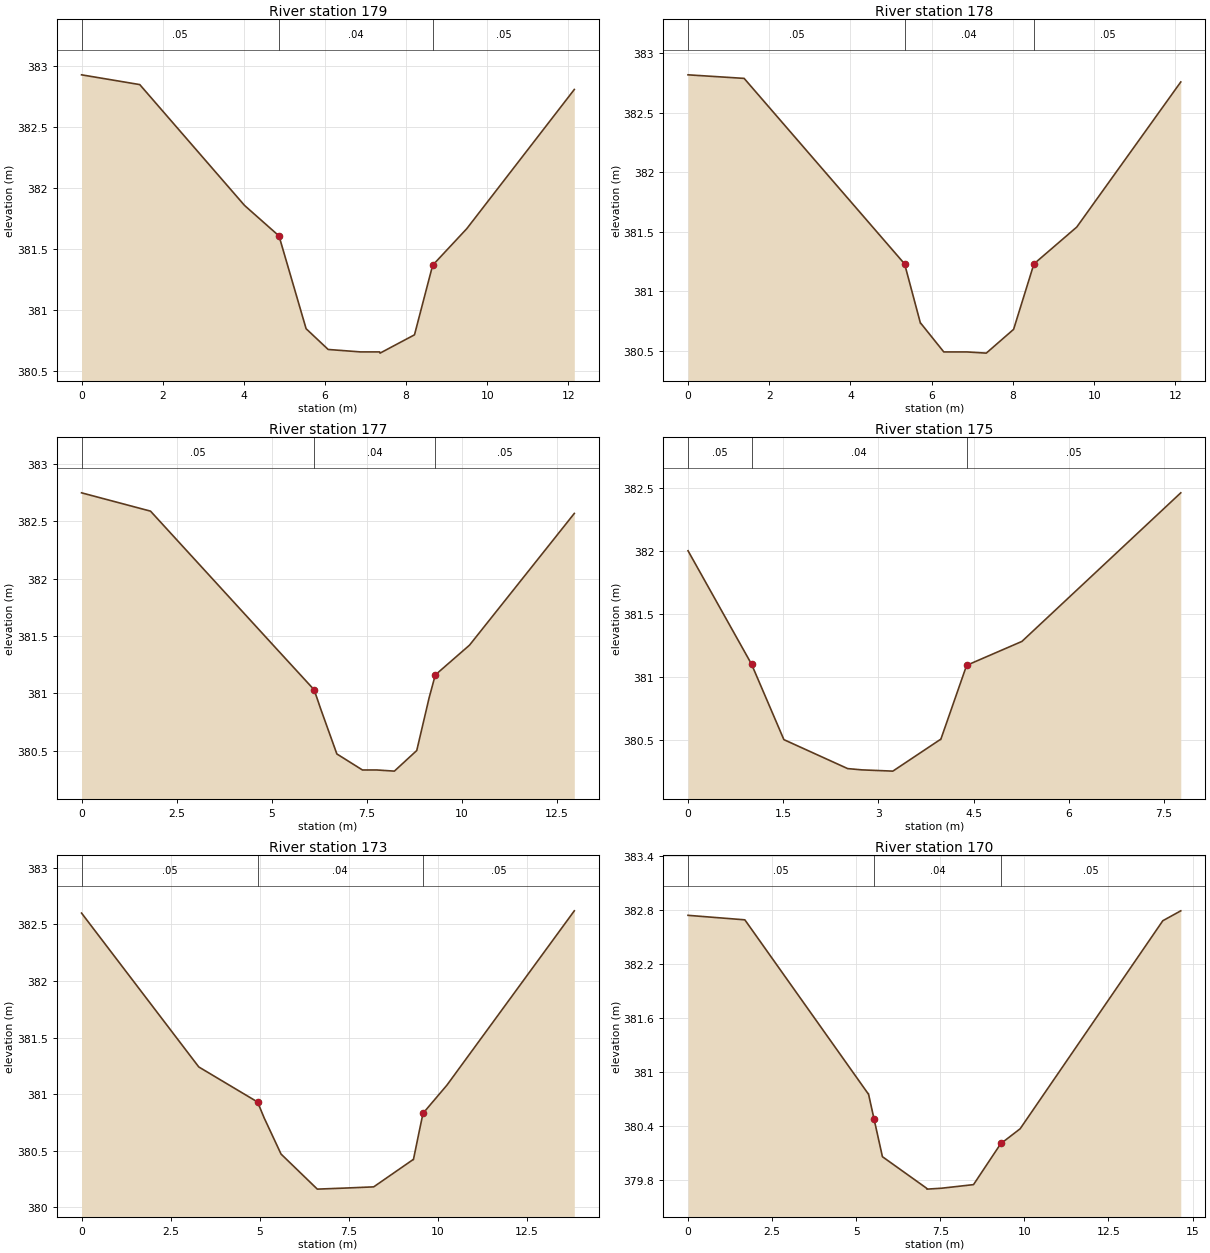
Type RM Length L Ch R = 1 ,179     ,25.85,25.85,25.85
XS GIS Cut Line= 6
      3491185.09      5381621.98      3491184.35      5381620.75
      3491182.94      5381617.62      3491182.43      5381617.19
      3491181.24      5381615.82      3491178.41      5381611.98
#Sta/Elev= 13
       0  382.93   1.435  382.85   4.018  381.86   4.868  381.61   5.536  380.85
    6.08  380.68   6.875  380.66   7.349  380.66   7.359  380.65   8.208   380.8
   8.656  381.37   9.498  381.67  12.148  382.81
#Mann= 3 , 0 , 0
       0     .05       0   4.868     .04       0   8.656     .05       0
Bank Sta=4.868,8.656
XS Rating Curve= 0 ,0
Exp/Cntr=0.3,0.1

Type RM Length L Ch R = 1 ,178     ,21.14,21.14,21.14
XS GIS Cut Line= 6
      3491204.98      5381604.35      3491201.42      5381599.88
      3491200.78      5381598.97      3491200.64      5381598.51
      3491199.74      5381597.76      3491197.37      5381595.03
#Sta/Elev= 12
       0  382.82   1.382  382.79   5.333  381.23   5.724  380.73   5.734  380.73
   6.298  380.49   6.863  380.49   7.344  380.48   8.017  380.68   8.517  381.23
   9.572  381.54  12.133  382.76
#Mann= 3 , 0 , 0
       0     .05       0   5.333     .04       0   8.517     .05       0
Bank Sta=5.333,8.517
XS Rating Curve= 0 ,0
Exp/Cntr=0.3,0.1

Type RM Length L Ch R = 1 ,177     ,50.08,50.08,50.08
XS GIS Cut Line= 6
      3491221.16      5381588.42      3491217.18      5381585.15
      3491215.88      5381584.28      3491214.35      5381582.85
      3491213.43      5381581.81      3491211.15      5381580.26
#Sta/Elev= 14
       0  382.75   1.815  382.59   5.152  381.38    6.12  381.03   6.295  380.86
   6.717  380.47    7.39  380.33    7.77  380.33    8.23  380.32   8.819   380.5
   9.144  380.96   9.307  381.16  10.207  381.42  12.964  382.57
#Mann= 3 , 0 , 0
       0     .05       0    6.12     .04       0   9.307     .05       0
Bank Sta=6.12,9.307
XS Rating Curve= 0 ,0
Exp/Cntr=0.3,0.1

Type RM Length L Ch R = 1 ,175     ,61.05,61.05,61.05
XS GIS Cut Line= 6
        3491244.      5381542.95      3491242.79      5381542.04
      3491242.16      5381541.71       3491241.6      5381541.22
      3491240.35      5381540.973491237.43856518 5381539.0243777
#Sta/Elev= 11
       0     382       1   381.1    1.51   380.5   2.515  380.27   2.738  380.26
   3.226  380.25    3.97   380.5    3.98   380.5   4.388  381.09   5.259  381.28
   7.761  382.46
#Mann= 3 , 0 , 0
       0     .05       0       1     .04       0   4.388     .05       0
Bank Sta=1,4.388
XS Rating Curve= 0 ,0
Exp/Cntr=0.3,0.1

Type RM Length L Ch R = 1 ,173     ,37.95,37.95,37.95
XS GIS Cut Line= 6
      3491283.27      5381497.42      3491279.52       5381494.2
      3491279.77      5381493.59      3491276.93      5381491.22
      3491276.94      5381490.94      3491274.12      5381487.77
#Sta/Elev= 14
       0   382.6   3.293  381.24   4.945  380.93   5.129  380.79   5.604  380.47
   6.623  380.16   7.455  380.17   8.207  380.18   9.308  380.42   9.322  380.42
   9.492  380.68   9.592  380.83  10.266  381.08  13.842  382.62
#Mann= 3 , 0 , 0
       0     .05       0   4.945     .04       0   9.592     .05       0
Bank Sta=4.945,9.592
XS Rating Curve= 0 ,0
Exp/Cntr=0.3,0.1

Type RM Length L Ch R = 1 ,170     ,49,49,49
XS GIS Cut Line= 6
      3491310.07      5381470.94      3491306.98      5381466.57
      3491304.51      5381464.93      3491304.18      5381464.18
      3491303.63       5381464.1      3491300.42       5381460.6
#Sta/Elev= 15
       0  382.74    1.69  382.69   5.354  380.76   5.364  380.76    5.53  380.48
    5.78  380.06   7.093  379.71   7.103   379.7   7.537  379.71   8.488  379.75
   9.307  380.21   9.317  380.21   9.874  380.37  14.116  382.68   14.65  382.79
#Mann= 3 , 0 , 0
       0     .05       0    5.53     .04       0   9.307     .05       0
Bank Sta=5.53,9.307
XS Rating Curve= 0 ,0
Exp/Cntr=0.3,0.1

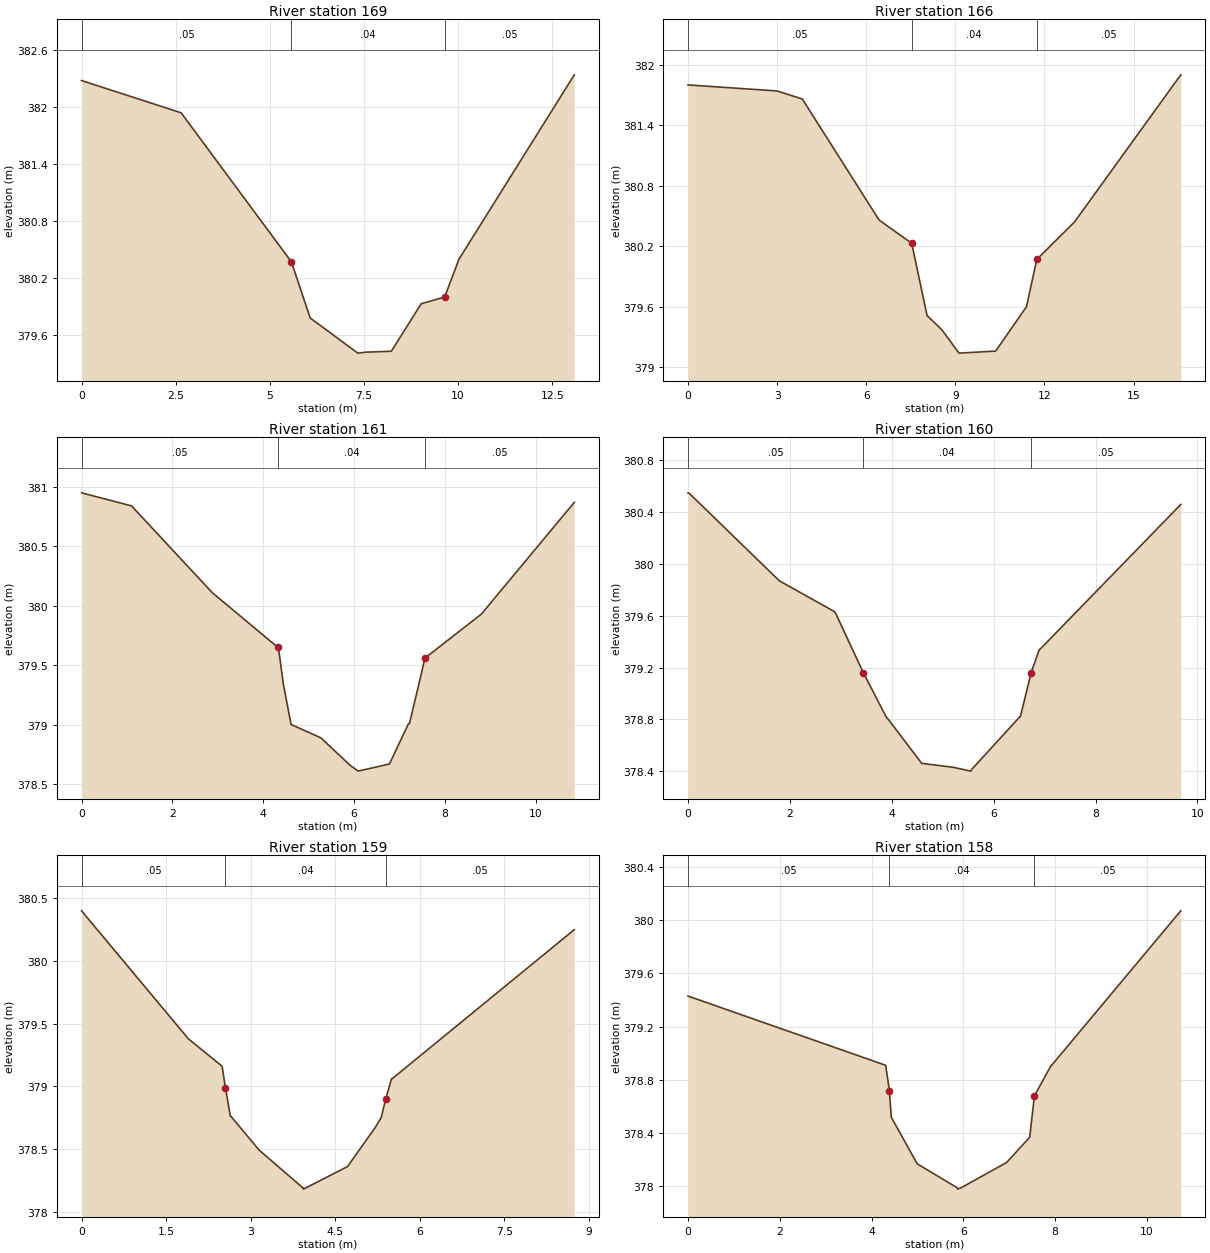
Type RM Length L Ch R = 1 ,169     ,75.26,75.26,75.26
XS GIS Cut Line= 6
      3491346.54      5381439.33      3491344.82      5381437.32
      3491343.38      5381434.77        3491343.      5381434.45
      3491340.76      5381431.21      3491338.86      5381428.81
#Sta/Elev= 11
       0  382.28   2.645  381.94   5.574  380.37   6.071  379.78   7.336  379.41
    7.55  379.42   8.228  379.43   9.019  379.93   9.641     380  10.024   380.4
  13.085  382.34
#Mann= 3 , 0 , 0
       0     .05       0   5.574     .04       0   9.641     .05       0
Bank Sta=5.574,9.641
XS Rating Curve= 0 ,0
Exp/Cntr=0.3,0.1

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
Type RM Length L Ch R = 1 ,166     ,90.085,90.085,90.085
XS GIS Cut Line= 6
      3491475.87      5381367.38      3491474.61      5381364.66
      3491474.56      5381363.81      3491473.16       5381359.9
       3491471.6       5381356.6      3491469.97      5381352.04
#Sta/Elev= 15
       0   381.8   2.998  381.74   3.849  381.66   6.432  380.46    7.53  380.23
    8.05  379.51    8.06  379.51   8.551  379.37   9.123  379.14   9.737  379.15
  10.357  379.16  11.395   379.6  11.743  380.07   13.01  380.44   16.59   381.9
#Mann= 3 , 0 , 0
       0     .05       0    7.53     .04       0  11.743     .05       0
Bank Sta=7.53,11.743
XS Rating Curve= 0 ,0
Exp/Cntr=0.3,0.1

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
Type RM Length L Ch R = 1 ,161     ,57.55,57.55,57.55
XS GIS Cut Line= 6
      3491646.12      5381318.73      3491646.45      5381317.68
      3491645.89      5381314.25      3491645.28      5381312.28
      3491645.53      5381310.31      3491645.37      5381308.27
#Sta/Elev= 18
       0  380.95   1.101  380.84   2.879  380.11   4.323  379.65   4.333  379.65
   4.443  379.34   4.613     379   4.623     379   5.268  378.89   5.909  378.66
   6.089  378.61   6.778  378.67   7.198  379.01   7.218  379.01   7.406  379.31
   7.558  379.56   8.801  379.93  10.847  380.87
#Mann= 3 , 0 , 0
       0     .05       0   4.333     .04       0   7.558     .05       0
Bank Sta=4.333,7.558
XS Rating Curve= 0 ,0
Exp/Cntr=0.3,0.1

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
Type RM Length L Ch R = 1 ,160     ,51.935,51.935,51.935
XS GIS Cut Line= 6
      3491759.88      5381307.51      3491759.82      5381304.63
      3491760.16      5381304.19      3491759.82      5381303.88
      3491759.08      5381301.46      3491758.87      5381298.33
#Sta/Elev= 17
       0  380.55    .014  380.55   1.794  379.87   2.886  379.63   3.442  379.16
   3.902  378.81   3.912  378.81   4.588  378.46   5.201  378.43   5.552   378.4
   5.562  378.41   6.515  378.82   6.525  378.82   6.736  379.16   6.897  379.34
   6.907  379.34   9.674  380.46
#Mann= 3 , 0 , 0
       0     .05       0   3.442     .04       0   6.736     .05       0
Bank Sta=3.442,6.736
XS Rating Curve= 0 ,0
Exp/Cntr=0.3,0.1

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
Type RM Length L Ch R = 1 ,159     ,50.38,50.38,50.38
XS GIS Cut Line= 6
      3491861.88      5381283.29      3491861.36      5381281.47
      3491860.96      5381280.29      3491860.54      5381278.28
      3491860.44      5381278.24      3491859.65      5381274.92
#Sta/Elev= 17
       0   380.4   1.893  379.38   2.494  379.16   2.552  378.99   2.641  378.76
   2.651  378.76   3.154  378.49   3.927  378.19   3.937  378.19   3.937  378.18
   4.718  378.36   5.208  378.67   5.316  378.75   5.397   378.9   5.499  379.06
   5.509  379.06   8.742  380.25
#Mann= 3 , 0 , 0
       0     .05       0   2.552     .04       0   5.397     .05       0
Bank Sta=2.552,5.397
XS Rating Curve= 0 ,0
Exp/Cntr=0.3,0.1

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
Type RM Length L Ch R = 1 ,158     ,59.74,59.74,59.74
XS GIS Cut Line= 6
      3491956.28      5381246.82      3491953.92      5381241.45
      3491953.21      5381240.09      3491953.11      5381240.11
      3491953.32       5381239.8      3491951.97      5381237.33
#Sta/Elev= 14
       0  379.43   4.309  378.91    4.39  378.72   4.431  378.52   4.996  378.17
    5.87  377.99    5.88  377.98   5.953  377.99   6.945  378.18   7.449  378.37
   7.551  378.68   7.917  378.91   7.927  378.91  10.742  380.07
#Mann= 3 , 0 , 0
       0     .05       0    4.39     .04       0   7.551     .05       0
Bank Sta=4.39,7.551
XS Rating Curve= 0 ,0
Exp/Cntr=0.3,0.1