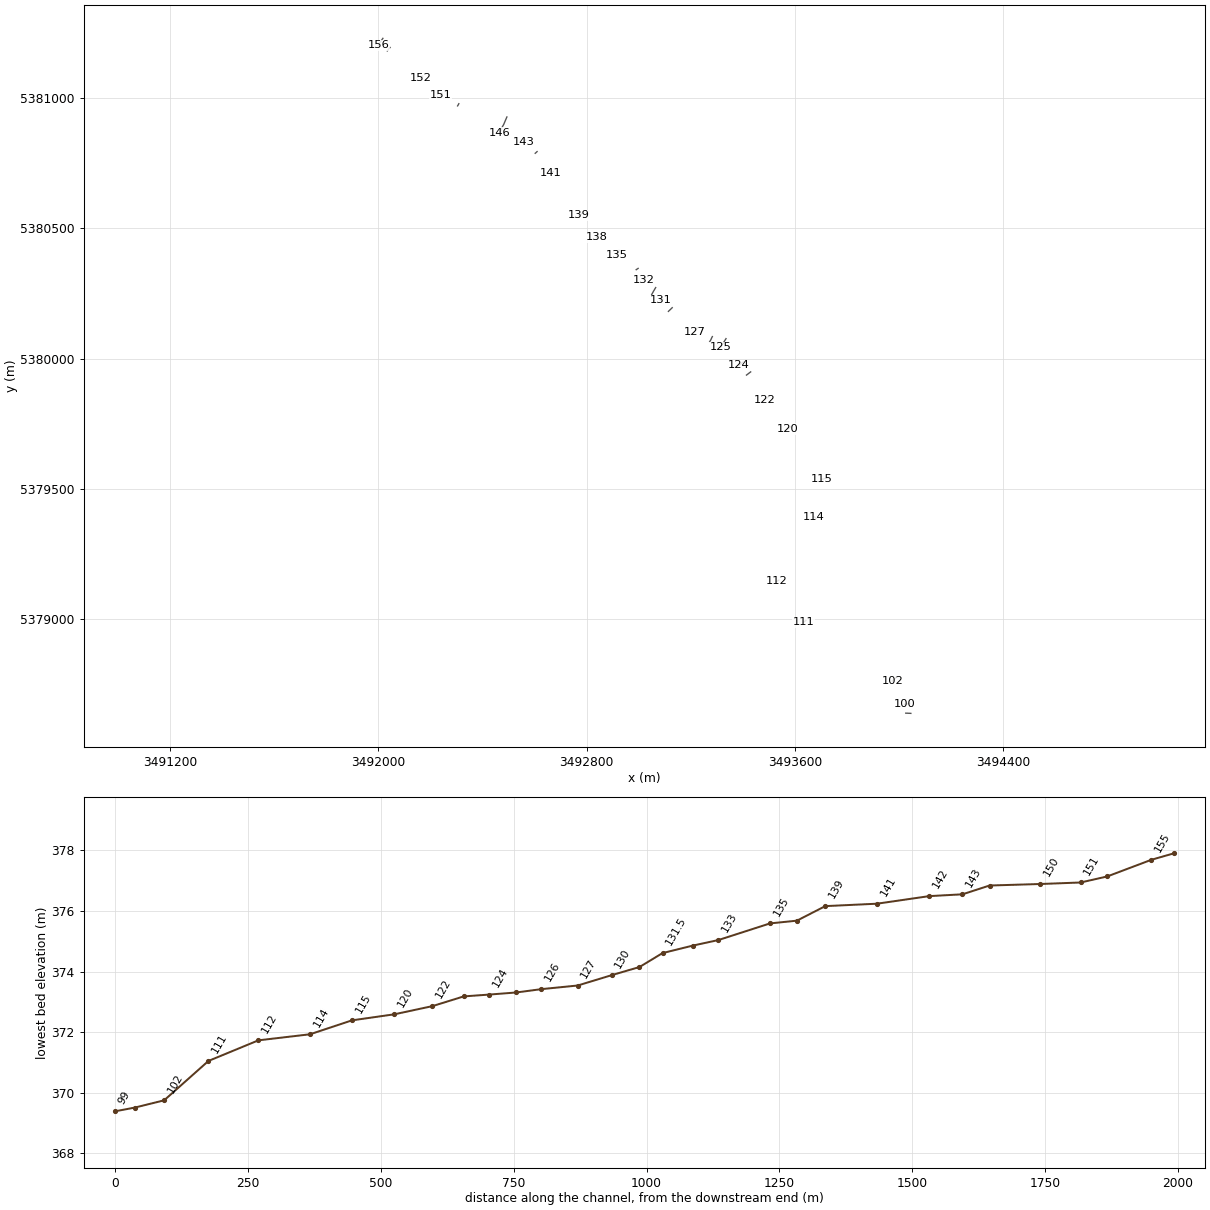
HEC-RAS study Amm_final.prj: Amm_final

--- Amm_final.g04 (geometry) --- (continued)

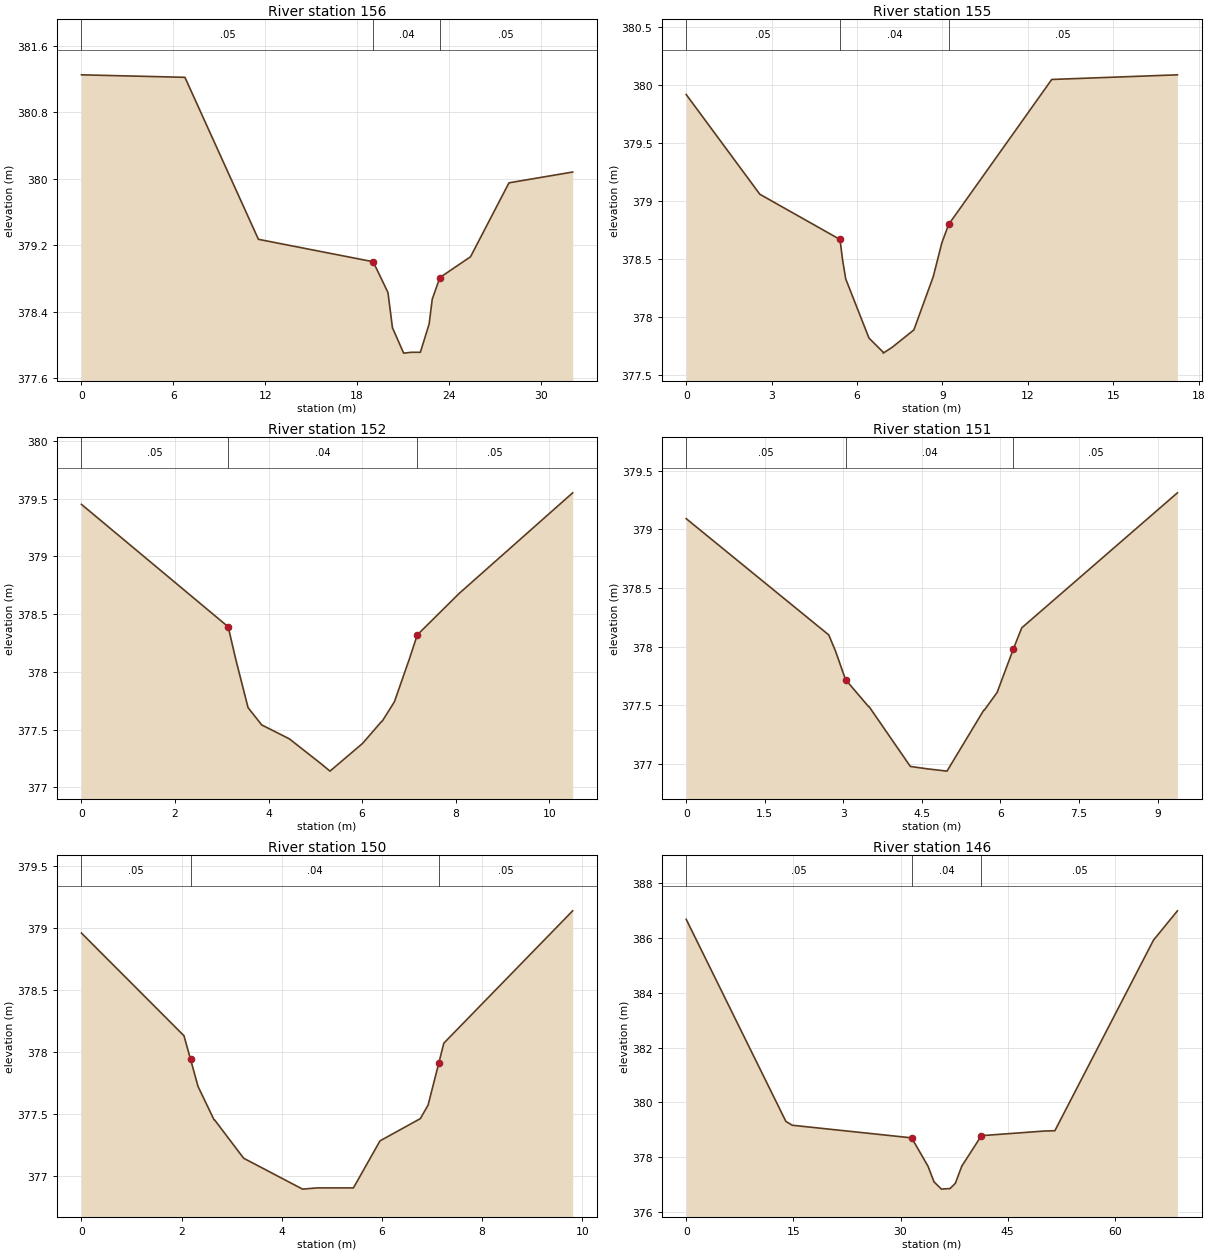
Type RM Length L Ch R = 1 ,156     ,41.87,41.87,41.87
XS GIS Cut Line= 6
      3492018.04      5381229.73      3492007.21      5381214.06
      3492006.18      5381213.34      3492006.09      5381212.63
      3492004.97      5381210.61      3492000.04      5381203.48
#Sta/Elev= 16
       0  381.25   6.756  381.22  11.555  379.27  19.049     379  20.015  378.63
  20.312   378.2  20.322   378.2  21.039   377.9  21.534  377.91   22.13  377.91
  22.702  378.25  22.907  378.55  23.407  378.81  25.407  379.06  27.918  379.95
  32.077  380.08
#Mann= 3 , 0 , 0
       0     .05       0  19.049     .04       0  23.407     .05       0
Bank Sta=19.049,23.407
XS Rating Curve= 0 ,0
Exp/Cntr=0.3,0.1

Type RM Length L Ch R = 1 ,155     ,83.095,83.095,83.095
XS GIS Cut Line= 6
       3492045.6      5381194.66      3492041.56      5381189.69
      3492040.05      5381188.07      3492039.53      5381187.92
      3492037.61      5381184.85      3492034.93      5381181.34
#Sta/Elev= 15
       0  379.92   2.587  379.06   5.404  378.67    5.49   378.5   5.604  378.33
   6.421  377.82   6.912   377.7   6.922  377.69   7.235  377.74   7.998  377.89
    8.68  378.35    8.98  378.64   9.221   378.8  12.842  380.05  17.258  380.09
#Mann= 3 , 0 , 0
       0     .05       0   5.404     .04       0   9.221     .05       0
Bank Sta=5.404,9.221
XS Rating Curve= 0 ,0
Exp/Cntr=0.3,0.1

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
Type RM Length L Ch R = 1 ,152     ,50.17,50.17,50.17
XS GIS Cut Line= 6
       3492170.8      5381085.12      3492168.48      5381083.01
      3492168.16      5381082.37      3492166.56      5381080.37
      3492165.37       5381079.3      3492163.96      5381077.33
#Sta/Elev= 16
       0  379.45   3.136  378.39   3.297  378.11   3.561  377.69   3.853  377.54
   4.442  377.42   5.134   377.2   5.312  377.14   6.009  377.38   6.415  377.57
   6.425  377.57   6.689  377.74   7.008  378.11   7.179  378.32   8.077  378.68
    10.5  379.55
#Mann= 3 , 0 , 0
       0     .05       0   3.136     .04       0   7.179     .05       0
Bank Sta=3.136,7.179
XS Rating Curve= 0 ,0
Exp/Cntr=0.3,0.1

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
Type RM Length L Ch R = 1 ,151     ,76.46,76.46,76.46
XS GIS Cut Line= 6
       3492245.3       5381018.8      3492243.52      5381016.74
      3492242.87      5381016.35      3492241.67      5381014.33
      3492241.66      5381013.86      3492239.92      5381011.45
#Sta/Elev= 15
       0  379.09   2.722   378.1   2.853  377.96   3.042  377.72   3.481  377.49
   3.491  377.49    4.28  376.98   4.594  376.96    4.98  376.94   5.683  377.46
   5.693  377.46   5.937  377.61   6.247  377.98   6.407  378.16    9.38  379.31
#Mann= 3 , 0 , 0
       0     .05       0   3.042     .04       0   6.247     .05       0
Bank Sta=3.042,6.247
XS Rating Curve= 0 ,0
Exp/Cntr=0.3,0.1

Type RM Length L Ch R = 1 ,150     ,95.03,95.03,95.03
XS GIS Cut Line= 6
      3492309.55      5380978.72      3492308.26      5380977.13
      3492308.24      5380976.53      3492307.17      5380974.04
      3492306.01      5380972.67       3492304.8       5380970.4
#Sta/Elev= 16
       0  378.96   2.047  378.13   2.178  377.94   2.328  377.72   2.648  377.45
   2.658  377.45   3.238  377.14   4.415  376.89   4.709   376.9   5.431   376.9
   5.961  377.28   6.767  377.46   6.922  377.57   7.136  377.91   7.236  378.07
   9.809  379.14
#Mann= 3 , 0 , 0
       0     .05       0   2.178     .04       0   7.136     .05       0
Bank Sta=2.178,7.136
XS Rating Curve= 0 ,0
Exp/Cntr=0.3,0.1

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
Type RM Length L Ch R = 1 ,146     ,51,51,51
XS GIS Cut Line= 6
      3492494.03      5380927.93      3492481.88      5380899.47
      3492472.86      5380883.42      3492473.92      5380882.48
      3492468.04      5380869.99      3492465.46      5380867.85
#Sta/Elev= 19
       0  386.68  13.951  379.31  14.843  379.17  31.558  378.71  33.842  377.68
  34.698   377.1  34.708   377.1  35.732  376.84  36.199  376.85  36.934  376.86
  37.664  377.05  37.674  377.05  38.595  377.69  38.604  377.69  41.329  378.79
  50.191  378.96  51.608  378.97  65.412  385.92  68.764  386.99
#Mann= 3 , 0 , 0
       0     .05       0  31.558     .04       0  41.329     .05       0
Bank Sta=31.558,41.329
XS Rating Curve= 0 ,0
Exp/Cntr=0.3,0.1

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
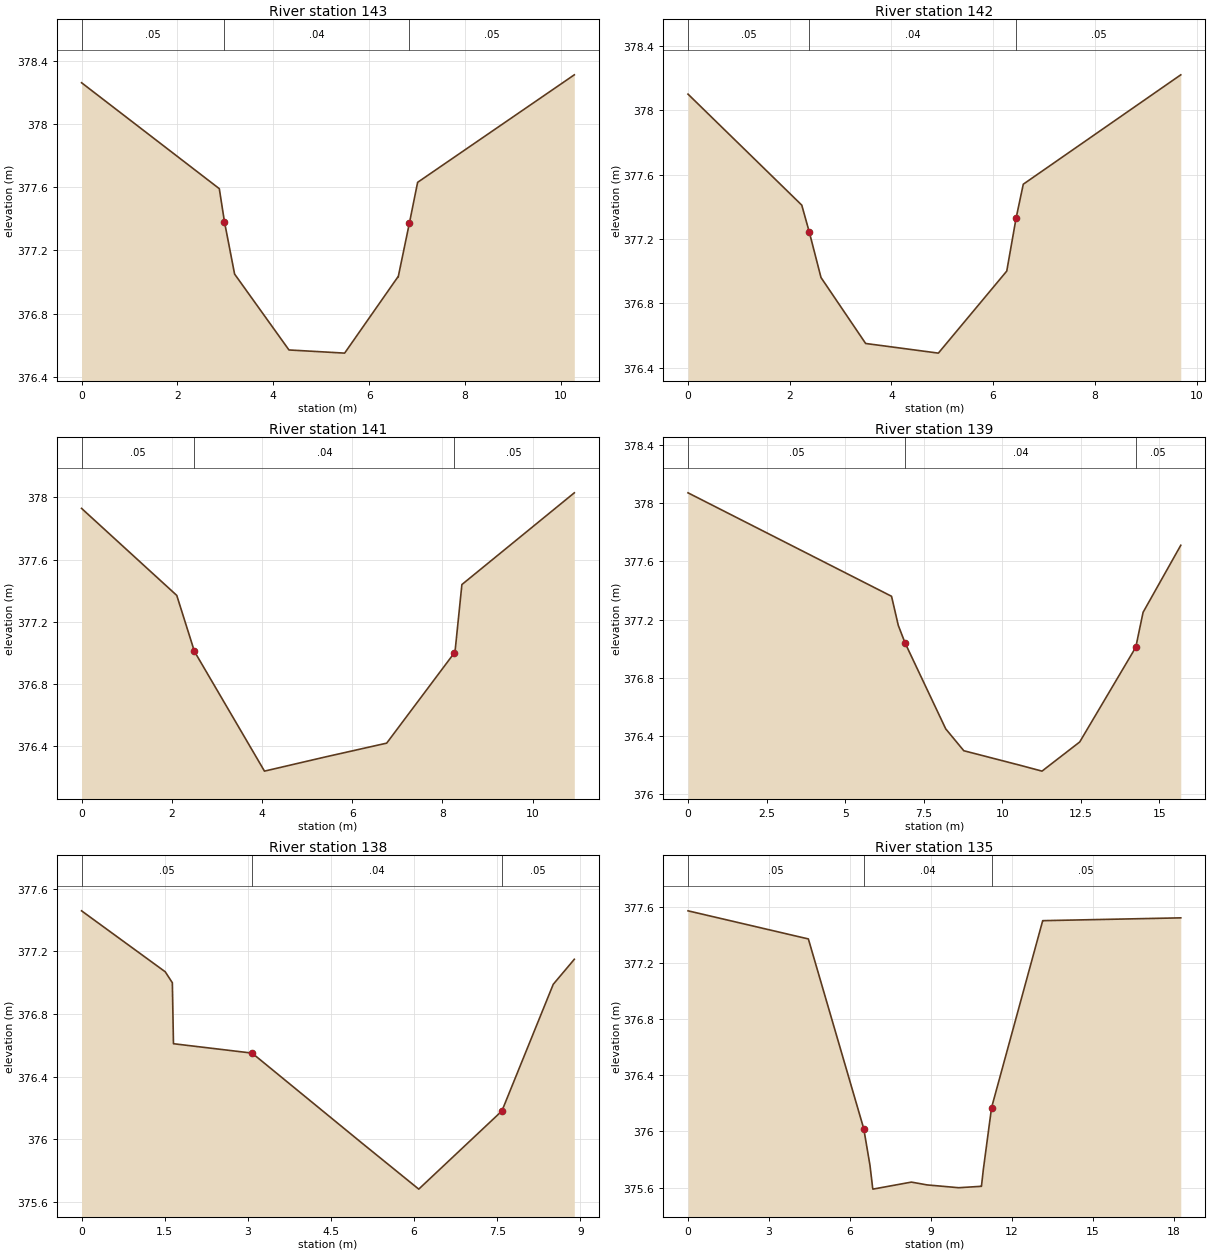
Type RM Length L Ch R = 1 ,143     ,62.75,62.75,62.75
XS GIS Cut Line= 6
      3492565.34      5380839.95      3492563.48      5380837.76
      3492562.74      5380836.51      3492561.23      5380834.84
      3492560.83      5380834.78      3492558.57      5380832.42
#Sta/Elev= 12
       0  378.26   2.873  377.59   2.981  377.38   3.192  377.05   4.326  376.57
   4.912  376.56   5.487  376.55   6.593  377.03   6.603  377.03   6.836  377.37
   7.009  377.63  10.277  378.31
#Mann= 3 , 0 , 0
       0     .05       0   2.981     .04       0   6.836     .05       0
Bank Sta=2.981,6.836
XS Rating Curve= 0 ,0
Exp/Cntr=0.3,0.1

Type RM Length L Ch R = 1 ,142     ,98.1,98.1,98.1
XS GIS Cut Line= 6
      3492609.95      5380794.93       3492608.3      5380793.42
      3492608.07      5380793.12      3492607.37      5380792.59
      3492605.14      5380790.44      3492602.75      5380788.47
#Sta/Elev= 11
       0   378.1   2.237  377.41   2.387  377.24   2.615  376.96   3.493  376.55
   4.448  376.51   4.923  376.49   6.268     377   6.452  377.33   6.593  377.54
    9.69  378.22
#Mann= 3 , 0 , 0
       0     .05       0   2.387     .04       0   6.452     .05       0
Bank Sta=2.387,6.452
XS Rating Curve= 0 ,0
Exp/Cntr=0.3,0.1

Type RM Length L Ch R = 1 ,141     ,97.49,97.49,97.49
XS GIS Cut Line= 6
      3492672.18      5380718.01      3492670.03      5380716.73
      3492668.86      5380715.71      3492665.39      5380713.34
      3492665.23      5380713.39      3492663.39      5380711.71
#Sta/Elev= 10
       0  377.93   2.111  377.37   2.502  377.01   4.055  376.24   5.386  376.33
   6.764  376.42   8.262     377   8.276     377   8.431  377.44  10.923  378.03
#Mann= 3 , 0 , 0
       0     .05       0   2.502     .04       0   8.262     .05       0
Bank Sta=2.502,8.262
XS Rating Curve= 0 ,0
Exp/Cntr=0.3,0.1

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
Type RM Length L Ch R = 1 ,139     ,53.405,53.405,53.405
XS GIS Cut Line= 6
      3492784.32       5380558.6      3492778.55      5380554.81
      3492777.54        5380554.      3492775.58      5380552.67
      3492774.95      5380552.38      3492771.43      5380549.72
#Sta/Elev= 13
       0  378.07   6.476  377.36   6.691  377.16   6.906  377.04     8.2  376.45
   8.775   376.3   10.57   376.2  11.263  376.16  12.463  376.36  14.247  377.01
  14.363  377.13   14.48  377.25  15.679  377.71
#Mann= 3 , 0 , 0
       0     .05       0   6.906     .04       0  14.247     .05       0
Bank Sta=6.906,14.247
XS Rating Curve= 0 ,0
Exp/Cntr=0.3,0.1

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
Type RM Length L Ch R = 1 ,138     ,50.525,50.525,50.525
XS GIS Cut Line= 6
      3492844.81      5380471.24       3492843.4      5380470.41
      3492840.82      5380468.15      3492838.88      5380466.56
      3492838.23       5380465.9      3492838.01      5380465.59
#Sta/Elev= 10
       0  377.46    1.51  377.07   1.638     377   1.658  376.61   3.076  376.55
   5.074  375.97   6.083  375.68   7.583  376.18   8.509  376.99   8.889  377.15
#Mann= 3 , 0 , 0
       0     .05       0   3.076     .04       0   7.583     .05       0
Bank Sta=3.076,7.583
XS Rating Curve= 0 ,0
Exp/Cntr=0.3,0.1

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
Type RM Length L Ch R = 1 ,135     ,97.31,97.31,97.31
XS GIS Cut Line= 6
       3492924.7      5380415.67      3492921.79      5380409.59
      3492920.48      5380406.59      3492920.17      5380405.75
      3492919.08      5380403.84        3492917.      5380399.18
#Sta/Elev= 16
       0  377.57    4.46  377.37   6.513  376.02   6.743  375.76   6.842   375.6
   6.852  375.59    8.28  375.64   8.859  375.62  10.032   375.6  10.865  375.61
  10.875  375.61  10.945  375.73   11.25  376.17  13.145   377.5  13.155   377.5
  18.262  377.52
#Mann= 3 , 0 , 0
       0     .05       0   6.513     .04       0   11.25     .05       0
Bank Sta=6.513,11.25
XS Rating Curve= 0 ,0
Exp/Cntr=0.3,0.1

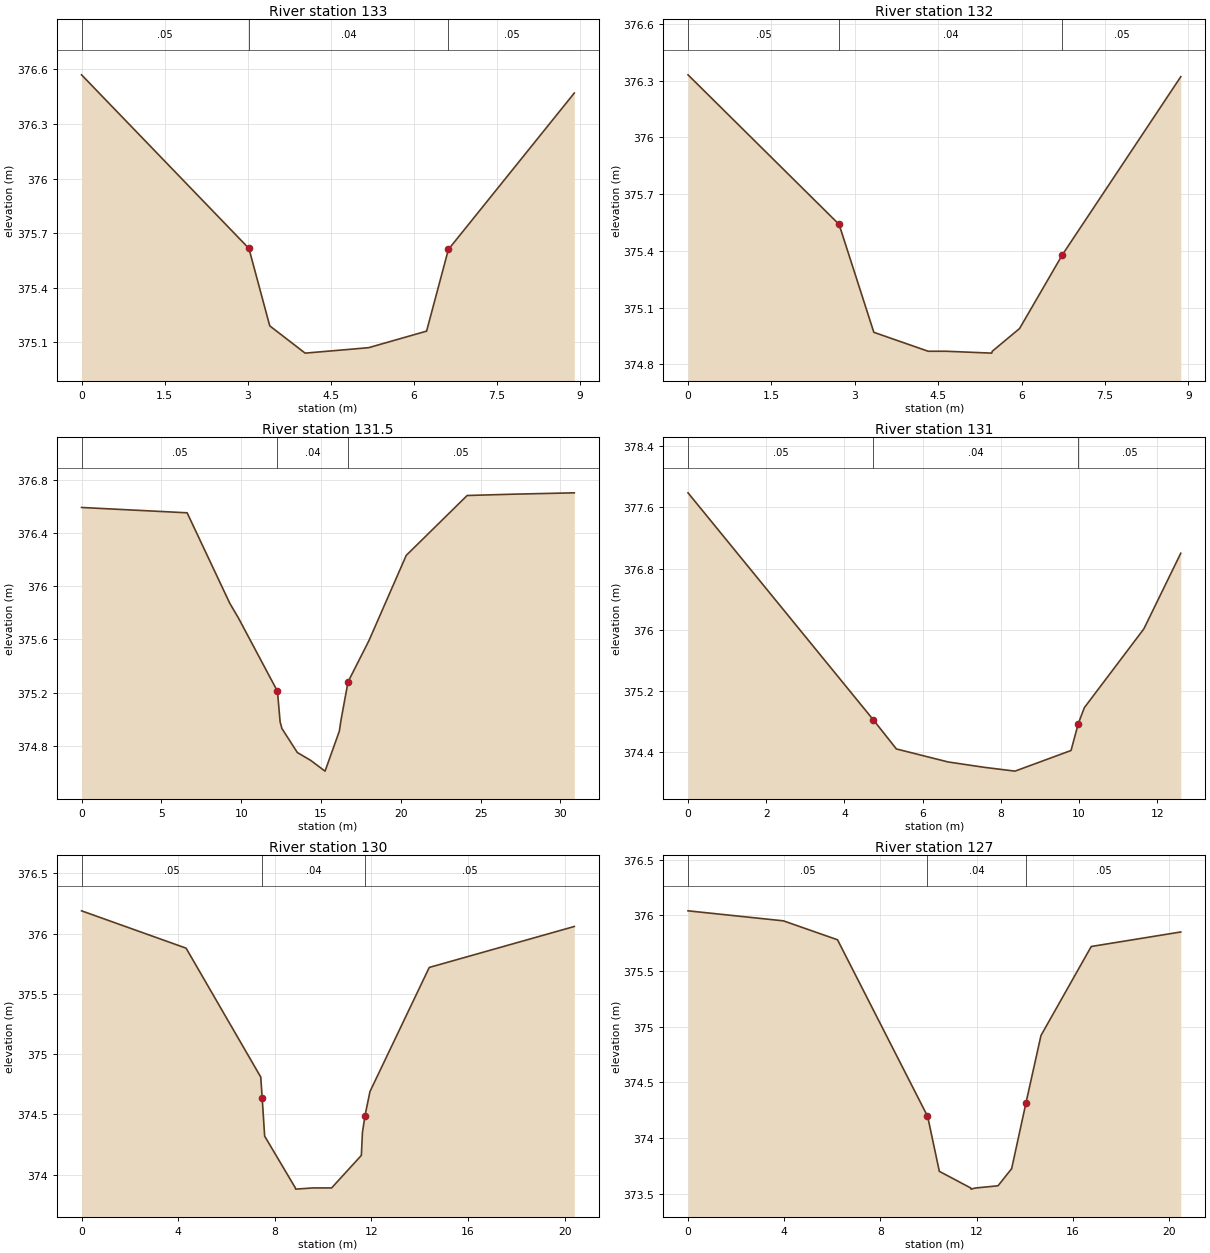
Type RM Length L Ch R = 1 ,133     ,47.46,47.46,47.46
XS GIS Cut Line= 6
      3492997.74       5380346.6      3492995.25      5380344.91
      3492994.37      5380344.41      3492992.65      5380343.07
      3492992.26      5380343.02      3492990.43      5380341.67
#Sta/Elev= 11
       0  376.57   3.009  375.62   3.019  375.62   3.399  375.19   4.038  375.04
   4.811  375.06   5.186  375.07   6.221  375.16   6.231  375.16   6.626  375.61
     8.9  376.47
#Mann= 3 , 0 , 0
       0     .05       0   3.019     .04       0   6.626     .05       0
Bank Sta=3.019,6.626
XS Rating Curve= 0 ,0
Exp/Cntr=0.3,0.1

Type RM Length L Ch R = 1 ,132     ,57.66,57.66,57.66
XS GIS Cut Line= 6
        3493026.      5380308.85      3493022.56      5380306.24
      3493022.27      5380306.11      3493021.69      5380305.52
      3493021.22      5380305.39      3493019.11       5380303.4
#Sta/Elev= 10
       0  376.33   2.718  375.54   3.343  374.97   4.319  374.87   4.637  374.87
   5.464  374.86   5.474  374.87   5.965  374.99   6.736  375.38   8.865  376.32
#Mann= 3 , 0 , 0
       0     .05       0   2.718     .04       0   6.736     .05       0
Bank Sta=2.718,6.736
XS Rating Curve= 0 ,0
Exp/Cntr=0.3,0.1

Type RM Length L Ch R = 1 ,131.5   ,43.42,43.42,43.42
XS GIS Cut Line= 6
      3493065.14      5380272.93      3493060.36      5380264.98
      3493060.33      5380264.44      3493056.55       5380258.8
      3493055.05      5380255.48      3493049.84      5380246.34
#Sta/Elev= 18
       0  376.59   6.614  376.55   9.288  375.87   9.829  375.76  12.272  375.21
  12.439  374.98  12.553  374.93  13.516  374.75  14.364  374.69  15.254  374.61
  16.149  374.91  16.249  374.99  16.693  375.28  18.004  375.59  20.339  376.23
  24.157  376.68  27.117  376.69  30.869   376.7
#Mann= 3 , 0 , 0
       0     .05       0  12.272     .04       0  16.693     .05       0
Bank Sta=12.272,16.693
XS Rating Curve= 0 ,0
Exp/Cntr=0.3,0.1

Type RM Length L Ch R = 1 ,131     ,52.58,52.58,52.58
XS GIS Cut Line= 6
      3493092.28      5380228.36      3493087.63      5380229.28
      3493086.36      5380227.88      3493085.54      5380227.46
      3493085.09      5380226.81      3493082.57       5380224.7
#Sta/Elev= 11
       0  377.79    4.74  374.82   5.328  374.44    6.65  374.27   7.572   374.2
   8.362  374.15   9.794  374.42   9.978  374.77  10.134  374.98  11.655  376.01
    12.6     377
#Mann= 3 , 0 , 0
       0     .05       0    4.74     .04       0   9.978     .05       0
Bank Sta=4.74,9.978
XS Rating Curve= 0 ,0
Exp/Cntr=0.3,0.1

Type RM Length L Ch R = 1 ,130     ,63.71,63.71,63.71
XS GIS Cut Line= 6
      3493128.67      5380195.75      3493123.32      5380190.61
      3493122.43      5380189.49      3493121.37      5380188.46
      3493120.15      5380187.45      3493114.07      5380181.57
#Sta/Elev= 15
       0  376.19   4.328  375.88   7.419  374.81   7.477  374.64    7.58  374.32
   8.852  373.89   8.862  373.88   9.594  373.89  10.352  373.89  11.583  374.16
  11.628  374.35  11.734  374.49   11.94  374.69  14.394  375.72  20.399  376.06
#Mann= 3 , 0 , 0
       0     .05       0   7.477     .04       0  11.734     .05       0
Bank Sta=7.477,11.734
XS Rating Curve= 0 ,0
Exp/Cntr=0.3,0.1

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
Type RM Length L Ch R = 1 ,127     ,68.42,68.42,68.42
XS GIS Cut Line= 6
      3493224.76      5380118.61      3493219.14      5380109.83
      3493217.66      5380107.99      3493217.38      5380106.88
      3493215.75      5380104.74      3493213.97      5380101.49
#Sta/Elev= 17
       0  376.04   3.966  375.95   6.215  375.78   9.945   374.2   9.955   374.2
  10.448   373.7  11.755  373.55  11.765  373.54  11.946  373.55  12.887  373.57
   13.44  373.72   13.45  373.72  14.045  374.31  14.673  374.92  16.764  375.72
  16.774  375.72  20.485  375.85
#Mann= 3 , 0 , 0
       0     .05       0   9.955     .04       0  14.045     .05       0
Bank Sta=9.955,14.045
XS Rating Curve= 0 ,0
Exp/Cntr=0.3,0.1

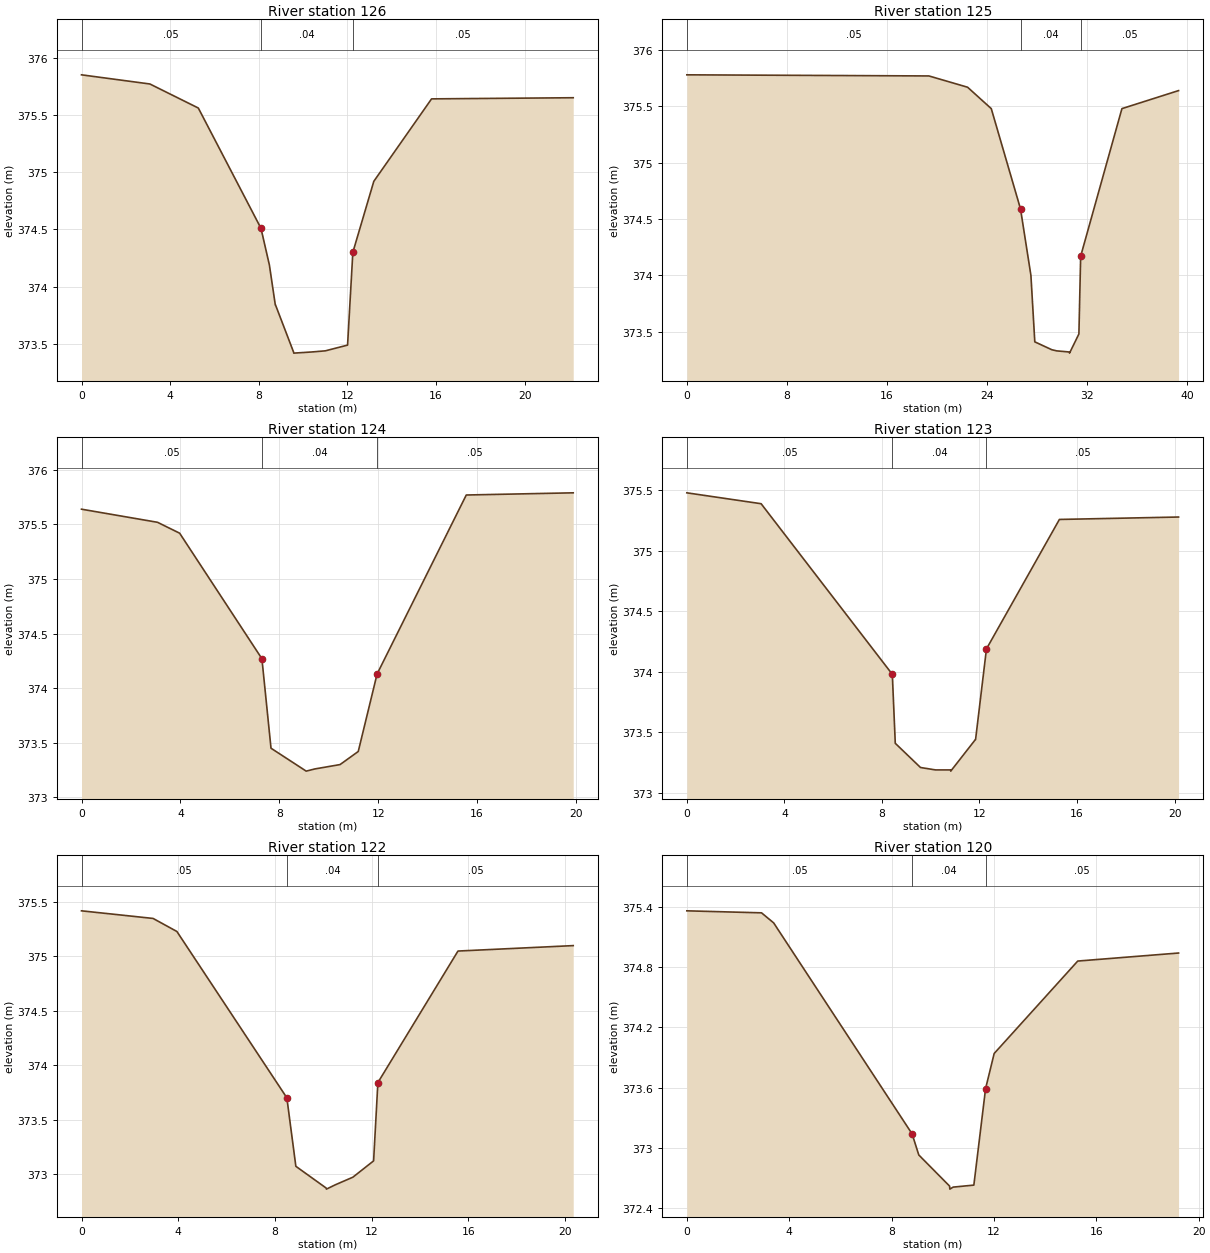
Type RM Length L Ch R = 1 ,126     ,47.33,47.33,47.33
XS GIS Cut Line= 6
      3493282.72      5380084.84      3493279.07      5380077.61
      3493278.95      5380077.25      3493279.08      5380077.01
      3493277.71      5380074.09      3493272.62      5380065.27
#Sta/Elev= 16
       0  375.85   3.087  375.77   5.273  375.56     8.1  374.51    8.48  374.19
   8.748  373.84   8.758  373.84    9.57  373.43    9.58  373.42   10.39  373.43
  11.006  373.44  12.009  373.49  12.247   374.3  13.193  374.92    15.8  375.64
  22.194  375.65
#Mann= 3 , 0 , 0
       0     .05       0     8.1     .04       0  12.247     .05       0
Bank Sta=8.1,12.247
XS Rating Curve= 0 ,0
Exp/Cntr=0.3,0.1

Type RM Length L Ch R = 1 ,125     ,51.385,51.385,51.385
XS GIS Cut Line= 6
       3493335.2        5380077.      3493320.59      5380053.68
      3493320.33      5380053.51      3493318.87      5380051.17
      3493318.61      5380050.47      3493314.27      5380043.79
#Sta/Elev= 15
       0  375.78  19.367  375.77  22.458  375.67  24.353  375.48  26.692  374.59
  27.524     374  27.835  373.41    29.2  373.34  29.586  373.33  30.603  373.32
  30.613  373.31  31.363  373.48  31.504  374.17  34.805  375.48  39.335  375.64
#Mann= 3 , 0 , 0
       0     .05       0  26.692     .04       0  31.504     .05       0
Bank Sta=26.692,31.504
XS Rating Curve= 0 ,0
Exp/Cntr=0.3,0.1

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
Type RM Length L Ch R = 1 ,124     ,47.5,47.5,47.5
XS GIS Cut Line= 6
      3493401.14      5379987.12      3493395.01      5379982.52
      3493393.84      5379981.71      3493392.75      5379980.88
      3493392.12       5379980.5      3493385.29      5379975.12
#Sta/Elev= 12
       0  375.64   3.074  375.52    3.97  375.42   7.297  374.27   7.665  373.45
   9.088  373.24   9.438  373.26  10.458   373.3  11.194  373.42  11.956  374.13
  15.563  375.77  19.889  375.79
#Mann= 3 , 0 , 0
       0     .05       0   7.297     .04       0  11.956     .05       0
Bank Sta=7.297,11.956
XS Rating Curve= 0 ,0
Exp/Cntr=0.3,0.1

Type RM Length L Ch R = 1 ,123     ,58.825,58.825,58.825
XS GIS Cut Line= 6
      3493429.76      5379949.33      3493423.06      5379944.22
      3493421.23      5379942.68      3493420.42      5379942.08
      3493420.02      5379941.89      3493413.79      5379937.07
#Sta/Elev= 13
       0  375.48   3.046  375.39   8.426  373.98   8.547  373.41   9.581  373.21
  10.198  373.19  10.821  373.19  10.821  373.18  11.829  373.44  11.839  373.44
  12.286  374.19  15.277  375.26  20.163  375.28
#Mann= 3 , 0 , 0
       0     .05       0   8.426     .04       0  12.286     .05       0
Bank Sta=8.426,12.286
XS Rating Curve= 0 ,0
Exp/Cntr=0.3,0.1

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
Type RM Length L Ch R = 1 ,122     ,71.53,71.53,71.53
XS GIS Cut Line= 6
      3493500.79      5379855.95      3493494.08      5379850.75
      3493493.89      5379850.43      3493492.97      5379849.58
      3493492.06      5379848.99      3493484.98      5379843.26
#Sta/Elev= 13
       0  375.42   2.959  375.35   3.944  375.23   8.491   373.7   8.863  373.07
  10.116  372.87  10.126  372.86  10.497   372.9  11.223  372.97  12.078  373.12
  12.255  373.84  15.567  375.05  20.332   375.1
#Mann= 3 , 0 , 0
       0     .05       0   8.491     .04       0  12.255     .05       0
Bank Sta=8.491,12.255
XS Rating Curve= 0 ,0
Exp/Cntr=0.3,0.1

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
Type RM Length L Ch R = 1 ,120     ,80.01,80.01,80.01
XS GIS Cut Line= 6
      3493587.44      5379741.46      3493584.71      5379739.45
      3493580.29      5379736.33      3493578.43       5379734.8
      3493578.04      5379734.56      3493572.08      5379729.94
#Sta/Elev= 13
       0  375.36   2.919  375.34   3.393  375.24   8.803  373.14   9.065  372.93
  10.269  372.62  10.279  372.59  10.407  372.61  11.217  372.63  11.675  373.59
  12.011  373.94  15.277  374.86  19.217  374.94
#Mann= 3 , 0 , 0
       0     .05       0   8.803     .04       0  11.675     .05       0
Bank Sta=8.803,11.675
XS Rating Curve= 0 ,0
Exp/Cntr=0.3,0.1

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
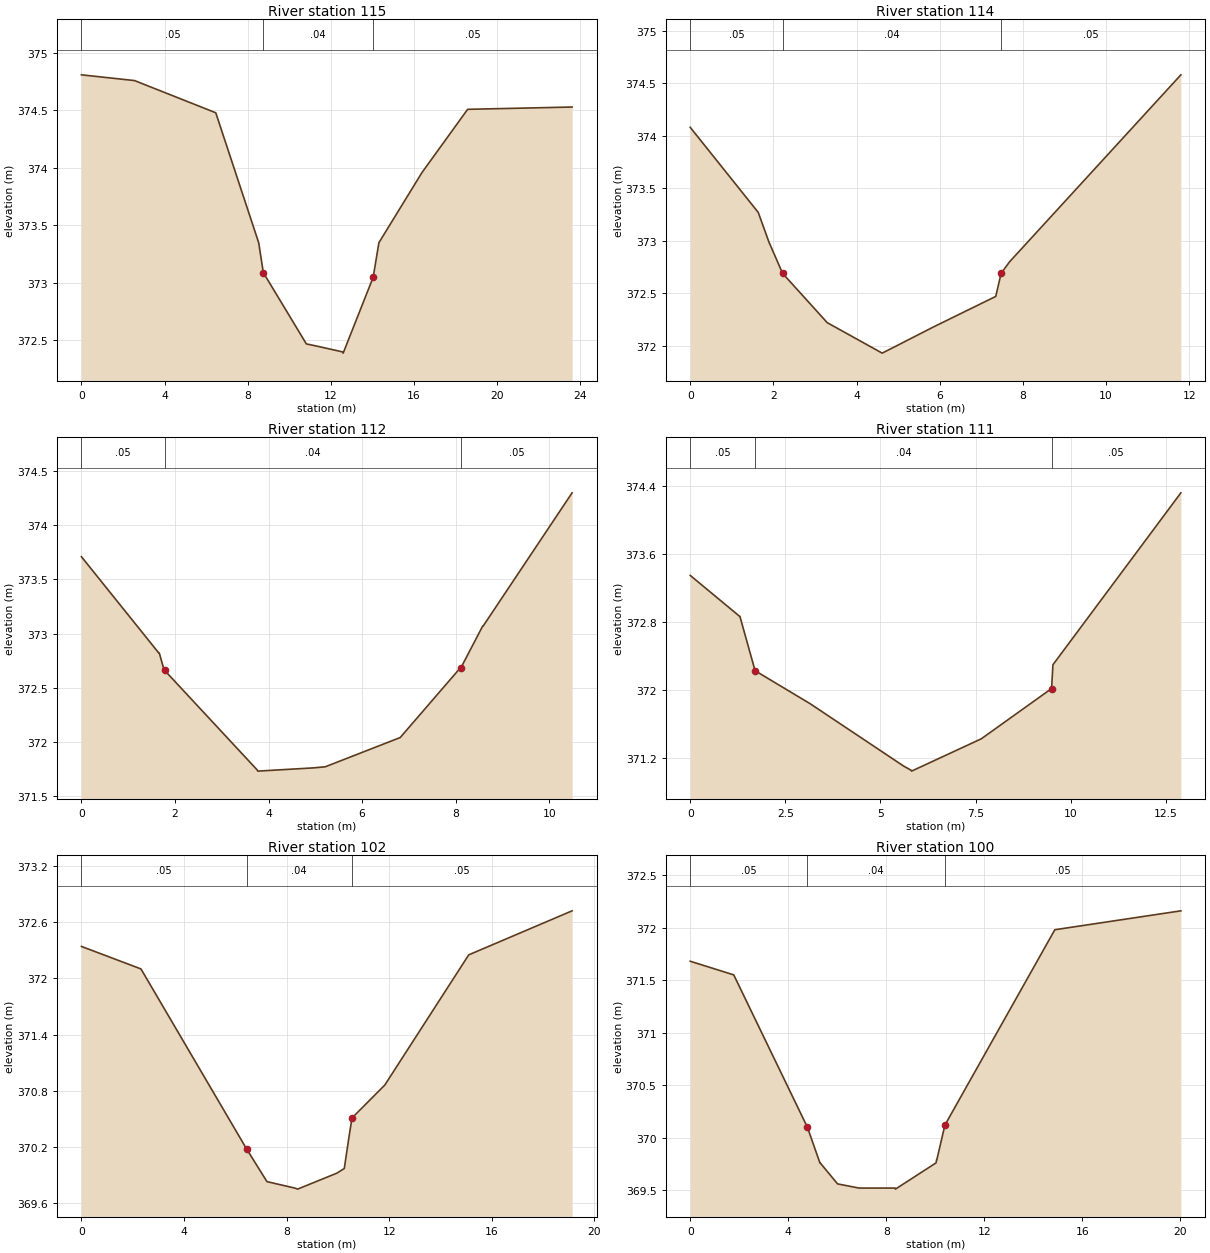
Type RM Length L Ch R = 1 ,115     ,79.09,79.09,79.09
XS GIS Cut Line= 6
      3493725.77      5379543.14       3493717.5      5379540.53
      3493714.92      5379539.89      3493713.69      5379539.85
      3493710.28      5379538.25      3493703.13      5379537.25
#Sta/Elev= 14
       0  374.81   2.555  374.76   6.463  374.48   8.528  373.35   8.751  373.09
  10.822  372.47  11.351  372.45  12.582   372.4  12.592  372.39  14.037  373.05
  14.311  373.35  16.383  373.96  18.581  374.51  23.607  374.53
#Mann= 3 , 0 , 0
       0     .05       0   8.751     .04       0  14.037     .05       0
Bank Sta=8.751,14.037
XS Rating Curve= 0 ,0
Exp/Cntr=0.3,0.1

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
Type RM Length L Ch R = 1 ,114     ,97.16,97.16,97.16
XS GIS Cut Line= 6
      3493681.04      5379387.24      3493679.82      5379388.33
      3493679.25      5379388.46      3493677.39      5379389.97
      3493677.19      5379389.97      3493671.48      5379393.98
#Sta/Elev= 12
       0  374.08   1.636  373.27   1.891  372.99   2.221  372.69   3.295  372.22
   4.617  371.93   4.817  371.97   5.854  372.18   7.349  372.47   7.477  372.69
   7.682   372.8  11.801  374.58
#Mann= 3 , 0 , 0
       0     .05       0   2.221     .04       0   7.477     .05       0
Bank Sta=2.221,7.477
XS Rating Curve= 0 ,0
Exp/Cntr=0.3,0.1

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
Type RM Length L Ch R = 1 ,112     ,93.995,93.995,93.995
XS GIS Cut Line= 6
      3493537.63      5379149.57      3493536.05      5379148.82
      3493534.39      5379147.74      3493530.52      5379145.84
      3493530.51      5379145.36      3493528.69      5379144.82
#Sta/Elev= 15
       0  373.71   1.655  372.82   1.665  372.82   1.769  372.66   1.779  372.66
   3.759  371.74   3.769  371.73    4.96  371.76   5.212  371.77   6.814  372.04
   8.093  372.68   8.107  372.68   8.578  373.07   8.588  373.07  10.489   374.3
#Mann= 3 , 0 , 0
       0     .05       0   1.779     .04       0   8.107     .05       0
Bank Sta=1.779,8.107
XS Rating Curve= 0 ,0
Exp/Cntr=0.3,0.1

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
Type RM Length L Ch R = 1 ,111     ,83.474,83.474,83.474
XS GIS Cut Line= 6
      3493641.79      5378995.77      3493640.91      5378994.82
      3493640.51      5378994.81      3493639.66      5378993.63
      3493634.81      5378989.63      3493631.89      5378987.89
#Sta/Elev= 12
       0  373.35   1.295  372.87   1.305  372.87   1.705  372.23    3.16  371.84
   5.607  371.11   5.808  371.06   5.818  371.05   7.652  371.43   9.498  372.02
   9.534   372.3  12.897  374.32
#Mann= 3 , 0 , 0
       0     .05       0   1.705     .04       0   9.498     .05       0
Bank Sta=1.705,9.498
XS Rating Curve= 0 ,0
Exp/Cntr=0.3,0.1

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
Type RM Length L Ch R = 1 ,102     ,55.265,55.265,55.265
XS GIS Cut Line= 6
      3493987.18      5378775.84      3493982.73      5378771.19
      3493980.13      5378768.85      3493979.65       5378768.5
      3493976.53      5378765.19      3493973.46      5378762.58
#Sta/Elev= 13
       0  372.34    2.32   372.1   6.436  370.18   7.233  369.83   8.337  369.76
   8.427  369.75   9.955  369.92  10.247  369.97  10.449  370.34  10.549  370.51
  11.825  370.86  15.099  372.25  19.129  372.72
#Mann= 3 , 0 , 0
       0     .05       0   6.436     .04       0  10.549     .05       0
Bank Sta=6.436,10.549
XS Rating Curve= 0 ,0
Exp/Cntr=0.3,0.1

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
Type RM Length L Ch R = 1 ,100     ,36.47,36.47,36.47
XS GIS Cut Line= 6
      3494040.19      5378676.42      3494038.42      5378676.27
      3494034.26      5378675.56      3494030.01      5378674.65
      3494025.58      5378673.96      3494020.53      5378672.99
#Sta/Elev= 15
       0  371.68   1.776  371.55   4.779   370.1   5.291  369.76   5.301  369.76
   6.011  369.56   6.889  369.52   8.362  369.52   8.372  369.51  10.029  369.76
  10.051  369.79  10.061  369.79  10.391  370.12  14.875  371.98  20.017  372.16
#Mann= 3 , 0 , 0
       0     .05       0   4.779     .04       0  10.391     .05       0
Bank Sta=4.779,10.391
XS Rating Curve= 0 ,0
Exp/Cntr=0.3,0.1

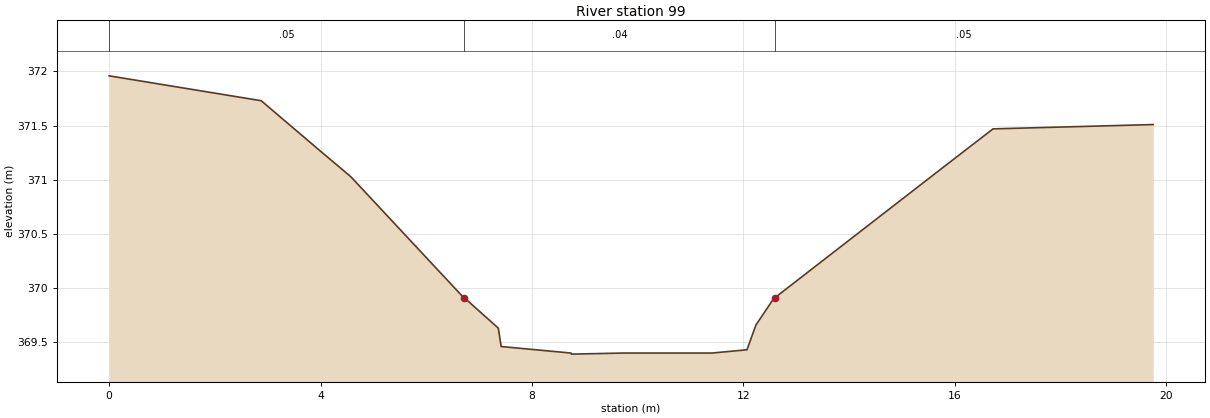
Type RM Length L Ch R = 1 ,99      ,76.83,76.83,76.83
XS GIS Cut Line= 6
      3494044.77      5378638.45      3494038.09      5378638.87
      3494035.01      5378638.87       3494032.3      5378639.14
       3494029.1      5378639.13      3494025.15       5378639.3
#Sta/Elev= 19
       0  371.96   2.878  371.73    4.01  371.26    4.57  371.03   6.712  369.91
   6.722  369.91   7.364  369.63   7.418  369.46   8.738   369.4   8.748  369.39
   9.731   369.4  11.406   369.4  12.069  369.43   12.24  369.66  12.585  369.91
  12.595  369.91  15.795  371.12  16.725  371.47  19.756  371.51
#Mann= 3 , 0 , 0
       0     .05       0   6.722     .04       0  12.595     .05       0
Bank Sta=6.722,12.595
XS Rating Curve= 0 ,0
Exp/Cntr=0.3,0.1