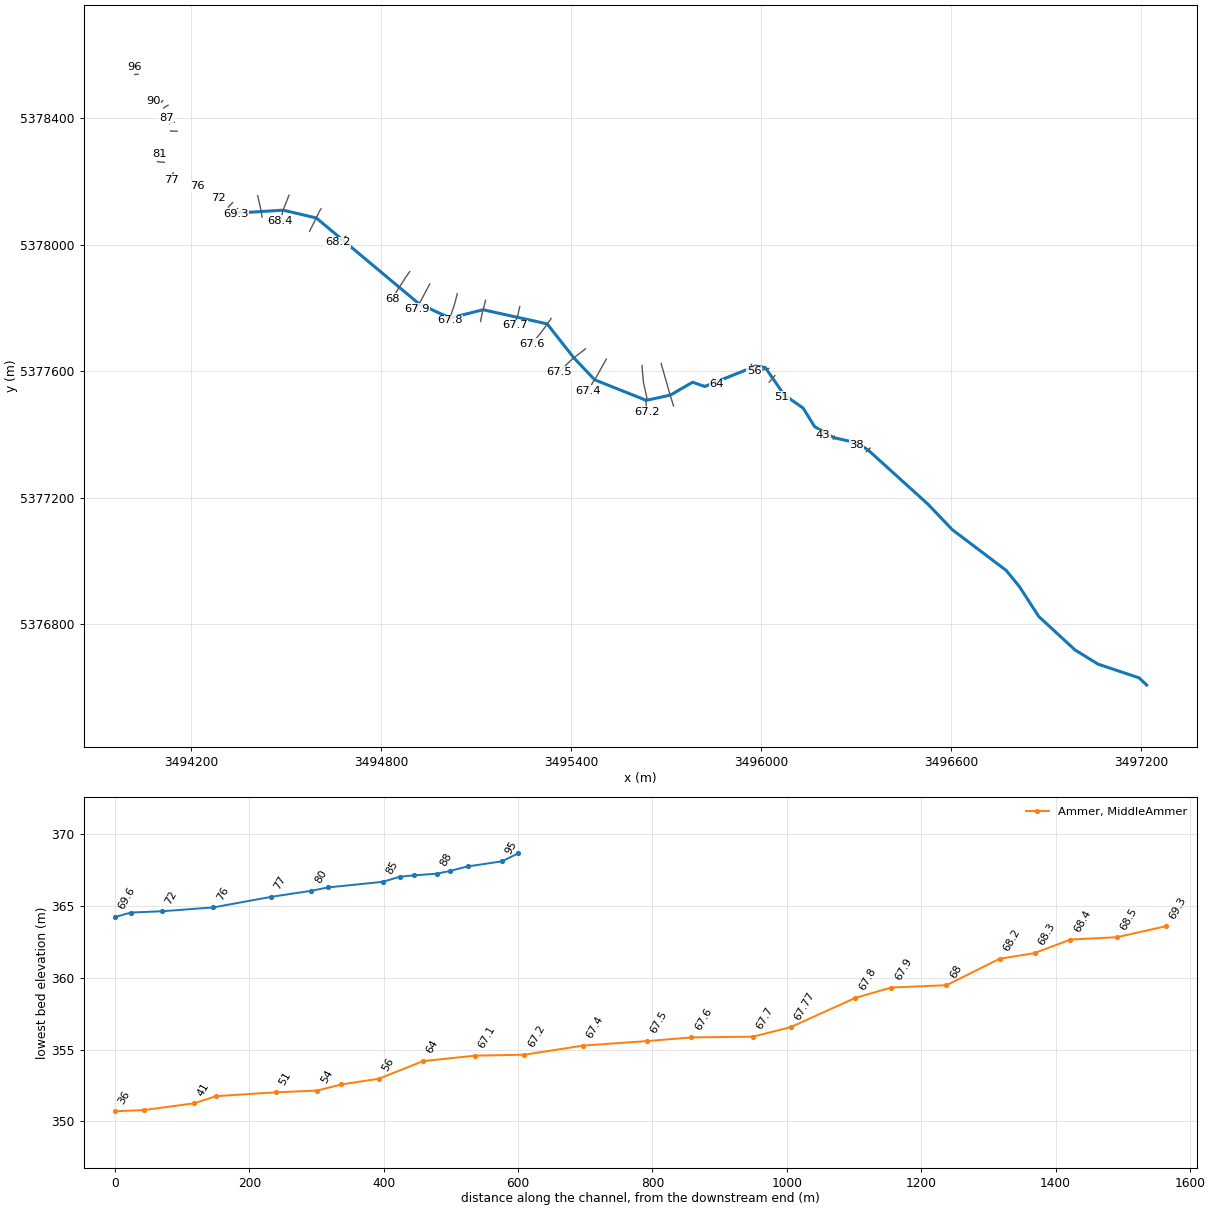
HEC-RAS study Amm_final.prj: Amm_final

--- Amm_final.g04 (geometry) --- (continued)

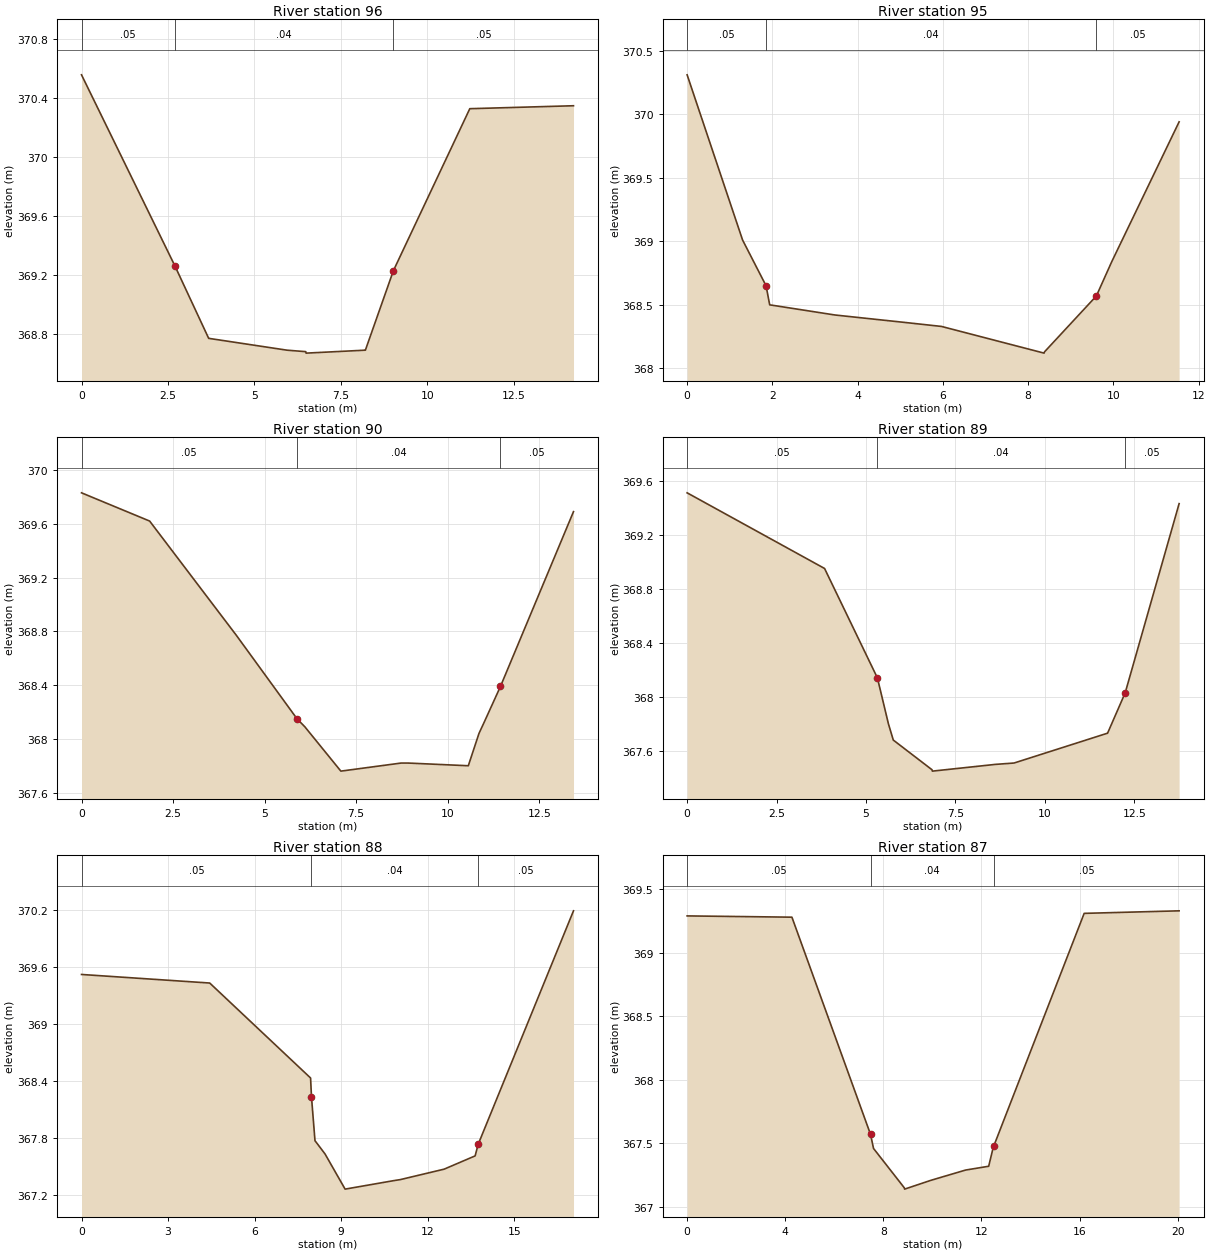
Type RM Length L Ch R = 1 ,96      ,23.8,23.8,23.8
XS GIS Cut Line= 6
      3494032.94      5378561.93      3494030.24      5378562.09
      3494024.78      5378562.48      3494023.97      5378562.48
      3494021.83      5378563.03      3494018.92      5378562.31
#Sta/Elev= 12
       0  370.56   2.705  369.26   3.677  368.77   3.687  368.77   5.942  368.69
   6.483  368.68   6.493  368.67   8.197  368.69   8.207  368.69   9.017  369.23
  11.226  370.33  14.224  370.35
#Mann= 3 , 0 , 0
       0     .05       0   2.705     .04       0   9.017     .05       0
Bank Sta=2.705,9.017
XS Rating Curve= 0 ,0
Exp/Cntr=0.3,0.1

Type RM Length L Ch R = 1 ,95      ,51.165,51.165,51.165
XS GIS Cut Line= 6
      3494031.38      5378539.28      3494030.37      5378538.46
      3494028.23      5378538.39      3494023.44      5378539.09
      3494022.26      5378538.79      3494020.84      5378537.47
#Sta/Elev= 12
       0  370.31   1.301  369.01   1.852  368.65   1.937   368.5    3.47  368.42
   5.148  368.36   5.968  368.33   8.375  368.12   8.385  368.13   9.602  368.57
   9.963  368.84  11.543  369.94
#Mann= 3 , 0 , 0
       0     .05       0   1.852     .04       0   9.602     .05       0
Bank Sta=1.852,9.602
XS Rating Curve= 0 ,0
Exp/Cntr=0.3,0.1

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
Type RM Length L Ch R = 1 ,90      ,26.24,26.24,26.24
XS GIS Cut Line= 6
      3494083.94      5378466.86      3494082.64      5378465.53
      3494081.14      5378461.57      3494079.13      5378457.81
      3494078.82      5378456.99      3494079.32      5378455.06
#Sta/Elev= 13
       0  369.83    1.86  369.62   4.228  368.77   5.882  368.15   6.097  368.09
   7.081  367.76   8.726  367.82   8.923  367.82  10.561   367.8  10.852  368.04
  11.005  368.13  11.439  368.39  13.433  369.69
#Mann= 3 , 0 , 0
       0     .05       0   5.882     .04       0  11.439     .05       0
Bank Sta=5.882,11.439
XS Rating Curve= 0 ,0
Exp/Cntr=0.3,0.1

Type RM Length L Ch R = 1 ,89      ,19.43,19.43,19.43
XS GIS Cut Line= 6
      3494109.26      5378455.85      3494106.64      5378453.04
      3494104.82      5378450.68      3494103.19      5378450.01
      3494103.27       5378449.5      3494098.98      5378447.84
#Sta/Elev= 13
       0  369.51   3.842  368.95   5.319  368.14   5.627   367.8   5.763  367.68
   6.846  367.46   6.856  367.45   8.623   367.5   9.139  367.51  11.742  367.73
  11.752  367.73  12.246  368.03  13.753  369.43
#Mann= 3 , 0 , 0
       0     .05       0   5.319     .04       0  12.246     .05       0
Bank Sta=5.319,12.246
XS Rating Curve= 0 ,0
Exp/Cntr=0.3,0.1

Type RM Length L Ch R = 1 ,88      ,34.66,34.66,34.66
XS GIS Cut Line= 6
      3494126.16      5378441.01      3494122.22      5378438.96
      3494119.17      5378437.25      3494119.02      5378437.28
       3494116.8      5378435.68      3494111.87       5378431.9
#Sta/Elev= 14
       0  369.52   4.433  369.43   4.443  369.43   7.939  368.43   7.971  368.23
   8.092  367.77   8.441  367.63   9.136  367.26  10.833  367.35  11.046  367.36
  12.566  367.47  13.643  367.61  13.746  367.73  17.052  370.19
#Mann= 3 , 0 , 0
       0     .05       0   7.971     .04       0  13.746     .05       0
Bank Sta=7.971,13.746
XS Rating Curve= 0 ,0
Exp/Cntr=0.3,0.1

Type RM Length L Ch R = 1 ,87      ,20.49,20.49,20.49
XS GIS Cut Line= 6
      3494138.92      5378406.84      3494131.73      5378404.49
      3494131.71      5378404.52      3494127.04      5378403.11
      3494123.62      5378401.74      3494120.09      5378400.15
#Sta/Elev= 14
       0  369.29   4.263  369.28   4.273  369.28    7.48  367.57   7.601  367.46
   8.857  367.15   8.867  367.14   9.952  367.21  11.354  367.29  12.297  367.32
  12.496  367.48  12.506  367.48   16.19  369.31  20.062  369.33
#Mann= 3 , 0 , 0
       0     .05       0    7.48     .04       0  12.506     .05       0
Bank Sta=7.48,12.506
XS Rating Curve= 0 ,0
Exp/Cntr=0.3,0.1

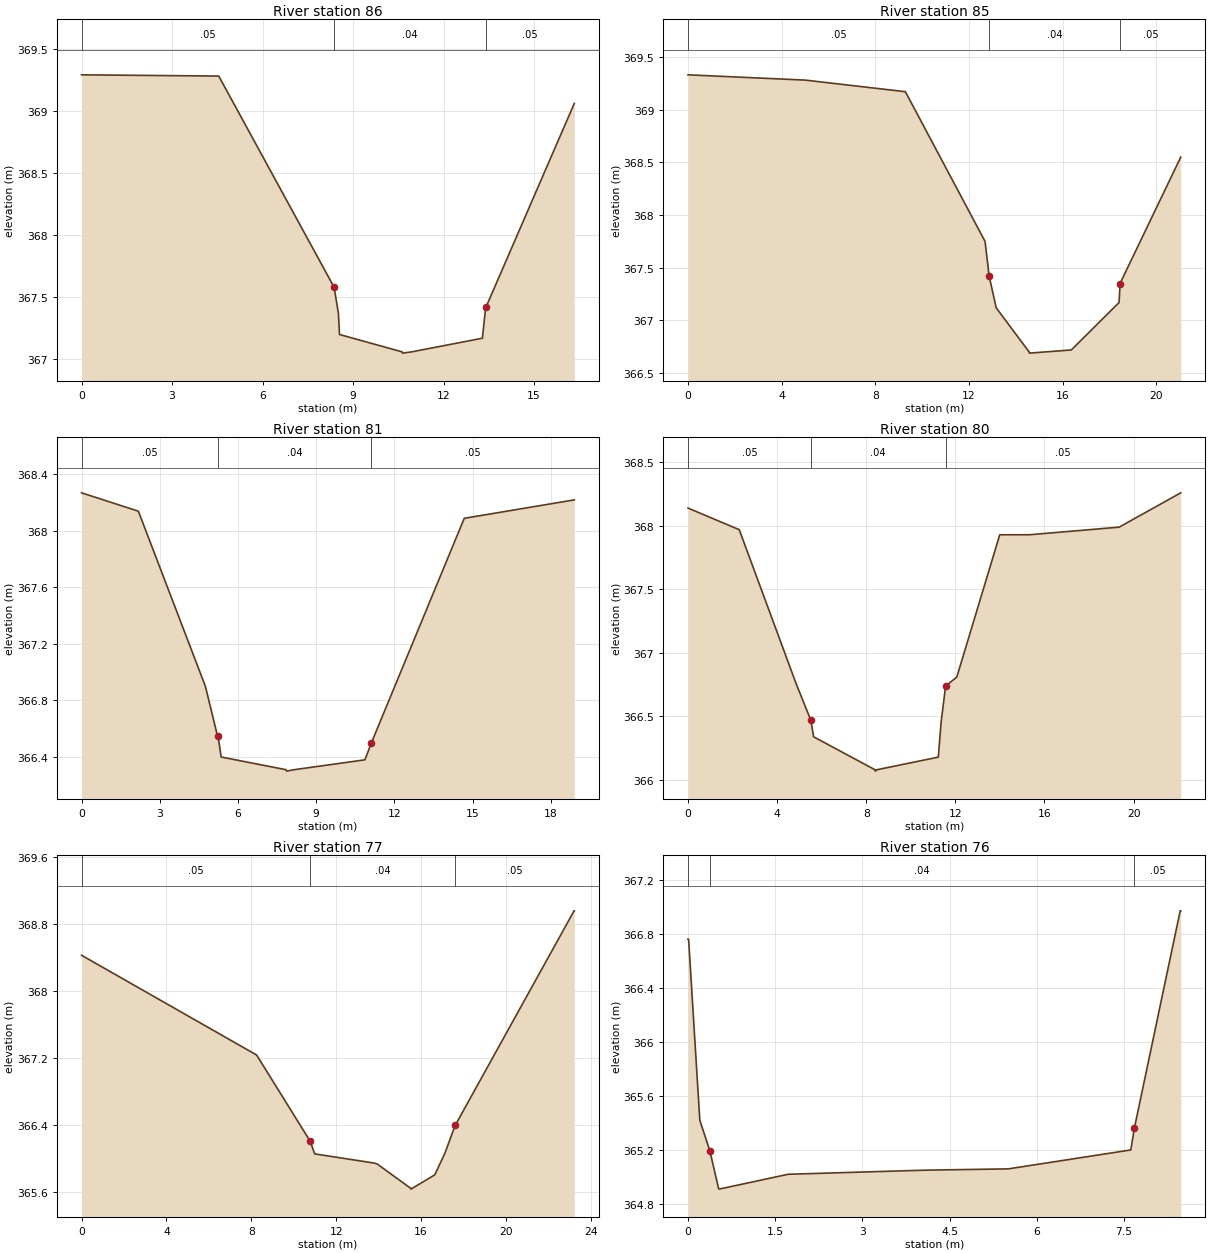
Type RM Length L Ch R = 1 ,86      ,25.68,25.68,25.68
XS GIS Cut Line= 6
       3494145.7      5378387.15      3494137.57      5378385.15
      3494135.53      5378384.24      3494135.23      5378384.27
        3494133.      5378383.53      3494130.24      5378382.28
#Sta/Elev= 13
       0  369.29   4.538  369.28   4.548  369.28   8.373  367.58   8.515  367.37
   8.551   367.2  10.629  367.06  10.639  367.05   10.94  367.06  13.289  367.17
  13.397  367.42  13.407  367.42  16.335  369.06
#Mann= 3 , 0 , 0
       0     .05       0   8.373     .04       0  13.397     .05       0
Bank Sta=8.373,13.397
XS Rating Curve= 0 ,0
Exp/Cntr=0.3,0.1

Type RM Length L Ch R = 1 ,85      ,81.35,81.35,81.35
XS GIS Cut Line= 6
      3494154.48      5378358.98      3494149.49      5378358.67
      3494138.78      5378359.45      3494138.23      5378359.67
      3494136.16      5378359.64      3494133.61      5378359.18
#Sta/Elev= 15
       0  369.33       5  369.28    9.28  369.17  12.683  367.75  12.858  367.42
  12.918  367.36  13.159  367.12  14.569   366.7  14.579  366.69  15.773  366.71
  16.365  366.72  18.406  367.17  18.448  367.35  18.619  367.43   21.04  368.55
#Mann= 3 , 0 , 0
       0     .05       0  12.858     .04       0  18.448     .05       0
Bank Sta=12.858,18.448
XS Rating Curve= 0 ,0
Exp/Cntr=0.3,0.1

Type RM Length L Ch R = 1 ,81      ,24.62,24.62,24.62
XS GIS Cut Line= 6
      3494118.27      5378282.29      3494113.23      5378283.97
      3494110.76      5378284.29      3494107.89      5378285.16
      3494104.29      5378285.55      3494100.26      5378286.77
#Sta/Elev= 14
       0  368.27   2.179  368.14   4.751   366.9   5.213  366.55   5.233  366.55
   5.355   366.4   7.845  366.31   7.865   366.3   8.149  366.31  10.869  366.38
  11.117   366.5   14.68  368.09   14.69  368.09    18.9  368.22
#Mann= 3 , 0 , 0
       0     .05       0   5.233     .04       0  11.117     .05       0
Bank Sta=5.233,11.117
XS Rating Curve= 0 ,0
Exp/Cntr=0.3,0.1

Type RM Length L Ch R = 1 ,80      ,60.5,60.5,60.5
XS GIS Cut Line= 6
      3494114.08      5378259.86      3494112.04      5378260.92
       3494109.5      5378261.13      3494103.03      5378260.86
      3494099.19      5378261.71      3494092.46      5378262.62
#Sta/Elev= 16
       0  368.14   2.299  367.97   4.848  366.76   5.513  366.47   5.639  366.34
     8.4  366.08    8.41  366.07   8.453  366.08  11.233  366.18  11.363  366.46
  11.562  366.74  12.064  366.81  13.992  367.93  15.322  367.93  19.353  367.99
  22.117  368.26
#Mann= 3 , 0 , 0
       0     .05       0   5.513     .04       0  11.562     .05       0
Bank Sta=5.513,11.562
XS Rating Curve= 0 ,0
Exp/Cntr=0.3,0.1

Type RM Length L Ch R = 1 ,77      ,85.39,85.39,85.39
XS GIS Cut Line= 6
      3494142.02      5378227.84      3494139.53      5378217.36
      3494137.26      5378212.06      3494137.66      5378211.79
      3494137.62       5378211.3      3494136.14      5378205.92
#Sta/Elev= 15
       0  368.43   8.249  367.24  10.777  366.21  10.988  366.06  10.998  366.06
  13.811  365.95  13.931  365.94   15.51  365.65   15.52  365.64  16.643  365.81
  17.125  366.07  17.618  366.41  17.628  366.41   23.21  368.96   23.22  368.96
#Mann= 3 , 0 , 0
       0     .05       0  10.777     .04       0  17.618     .05       0
Bank Sta=10.777,17.618
XS Rating Curve= 0 ,0
Exp/Cntr=0.3,0.1

Type RM Length L Ch R = 1 ,76      ,76.45,76.45,76.45
XS GIS Cut Line= 6
      3494220.59      5378193.06      3494220.61      5378191.47
      3494219.83      5378189.28      3494219.92      5378187.82
      3494218.93      5378185.94      3494219.07      5378185.21
#Sta/Elev= 13
       0  366.76     .01  366.76    .203  365.42    .378  365.19    .523  364.92
    .533  364.91   1.724  365.02   4.049  365.05   5.512  365.06   7.618   365.2
   7.679  365.36   8.468  366.97   8.478  366.97
#Mann= 3 , 0 , 0
       0     .05       0    .378     .04       0   7.679     .05       0
Bank Sta=0.378,7.679
XS Rating Curve= 0 ,0
Exp/Cntr=0.3,0.1

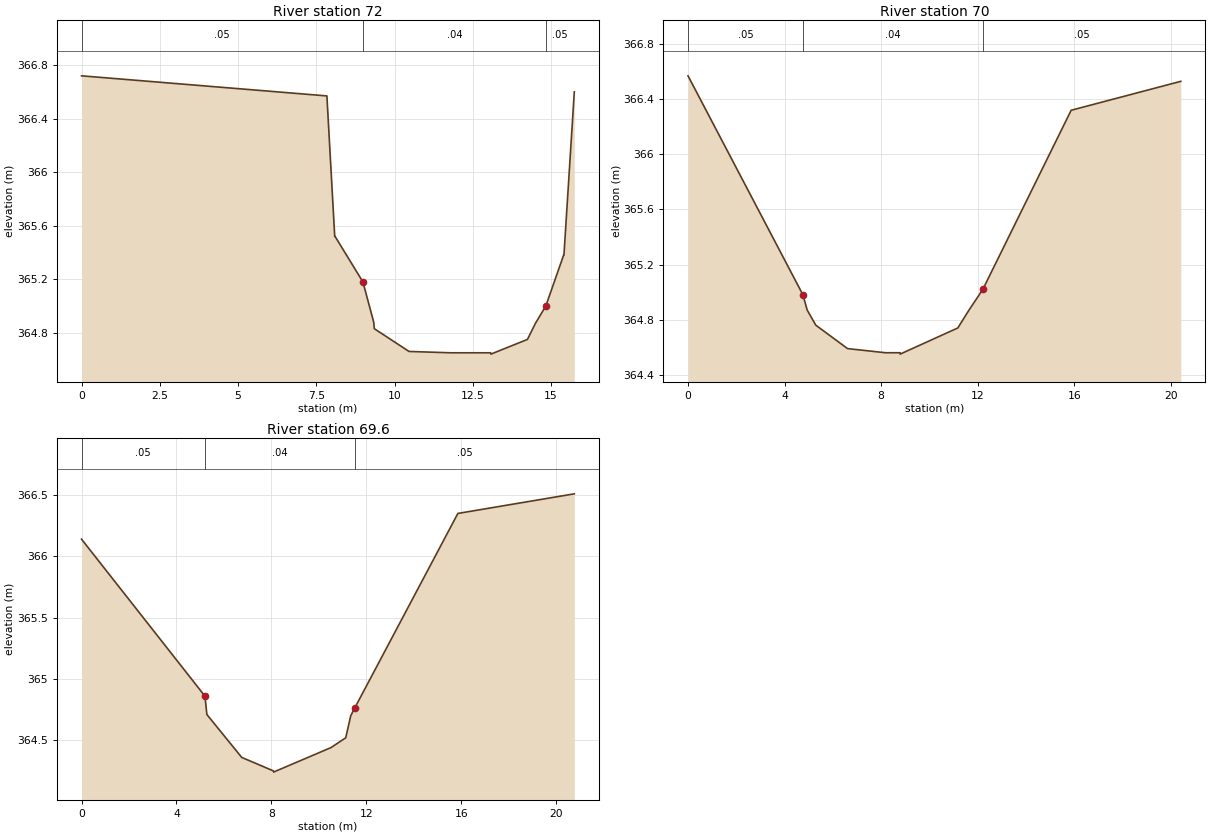
Type RM Length L Ch R = 1 ,72      ,46.57,46.57,46.57
XS GIS Cut Line= 6
      3494290.86      5378161.95      3494287.56      5378154.84
      3494287.36      5378154.69      3494286.76      5378153.62
       3494284.5      5378148.63      3494284.43      5378147.74
#Sta/Elev= 18
       0  366.72   7.829  366.57   7.839  366.57   8.089  365.52   8.099  365.52
   8.989  365.18   9.334  364.88   9.354  364.83  10.464  364.66  11.793  364.65
  13.068  364.65  13.078  364.64  14.247  364.75  14.502  364.87  14.834     365
  15.403  365.38  15.413  365.38  15.744   366.6
#Mann= 3 , 0 , 0
       0     .05       0   8.989     .04       0  14.834     .05       0
Bank Sta=8.989,14.834
XS Rating Curve= 0 ,0
Exp/Cntr=0.3,0.1

Type RM Length L Ch R = 1 ,70      ,23.5,23.5,23.5
XS GIS Cut Line= 6
       3494330.2      5378132.69      3494326.44      5378129.77
      3494324.28      5378126.48      3494322.28      5378124.46
      3494321.82       5378124.8      3494316.31      5378118.75
#Sta/Elev= 13
       0  366.57   4.761  364.98   4.936  364.87   5.294  364.76   6.609  364.59
   8.188  364.56   8.785  364.56   8.785  364.55  11.176  364.74   11.64  364.87
  12.212  365.02  15.871  366.32  20.411  366.53
#Mann= 3 , 0 , 0
       0     .05       0   4.761     .04       0  12.212     .05       0
Bank Sta=4.761,12.212
XS Rating Curve= 0 ,0
Exp/Cntr=0.3,0.1

Type RM Length L Ch R = 1 ,69.6    ,10.76,10.76,10.76
XS GIS Cut Line= 6
      3494345.59      5378113.98      3494341.73      5378110.38
      3494337.22      5378106.72      3494337.07      5378106.87
      3494333.54      5378104.16      3494329.05      5378102.18
#Sta/Elev= 13
       0  366.14   5.201  364.86   5.282  364.71   6.751  364.36   8.087  364.25
   8.097  364.24   8.209  364.25  10.512  364.44  11.134  364.52  11.346   364.7
  11.506  364.76  15.861  366.35  20.768  366.51
#Mann= 3 , 0 , 0
       0     .05       0   5.201     .04       0  11.506     .05       0
Bank Sta=5.201,11.506
XS Rating Curve= 0 ,0
Exp/Cntr=0.3,0.1

River Reach=Ammer           ,MiddleAmmer
Reach XY= 30
3494346.195783445378100.061837183494490.07594833 5378109.0531027
3494594.439752755378084.422613313494919.372741995377812.53990351
3495017.393000555377767.885002213495121.469064195377794.06703633
3495323.881170765377749.384801433495408.225997925377641.95199803
3495474.234998315377572.403998393495637.04100109 5377507.4610025
3495713.382999085377524.09800161 3495783.49241965377564.81401943
3495821.859143465377551.393560463495982.746760495377615.81176302
3496013.21909673 5377611.23301823496072.539999435377525.14999947
3496132.799999545377483.010000073496168.959999885377424.45000012
3496229.99898102 5377389.40073313496302.311571685377372.82251909
3496337.994203755377350.402458233496527.390000535377178.83000049
 3496604.19295465377098.255723323496774.300000585376969.55000069
3496816.394094015376918.105799923496877.180878185376823.84680864
 3496991.33372545376718.377787183497064.59364257 5376673.0640022
3497193.999999365376629.779998883497218.371753315376606.84435723

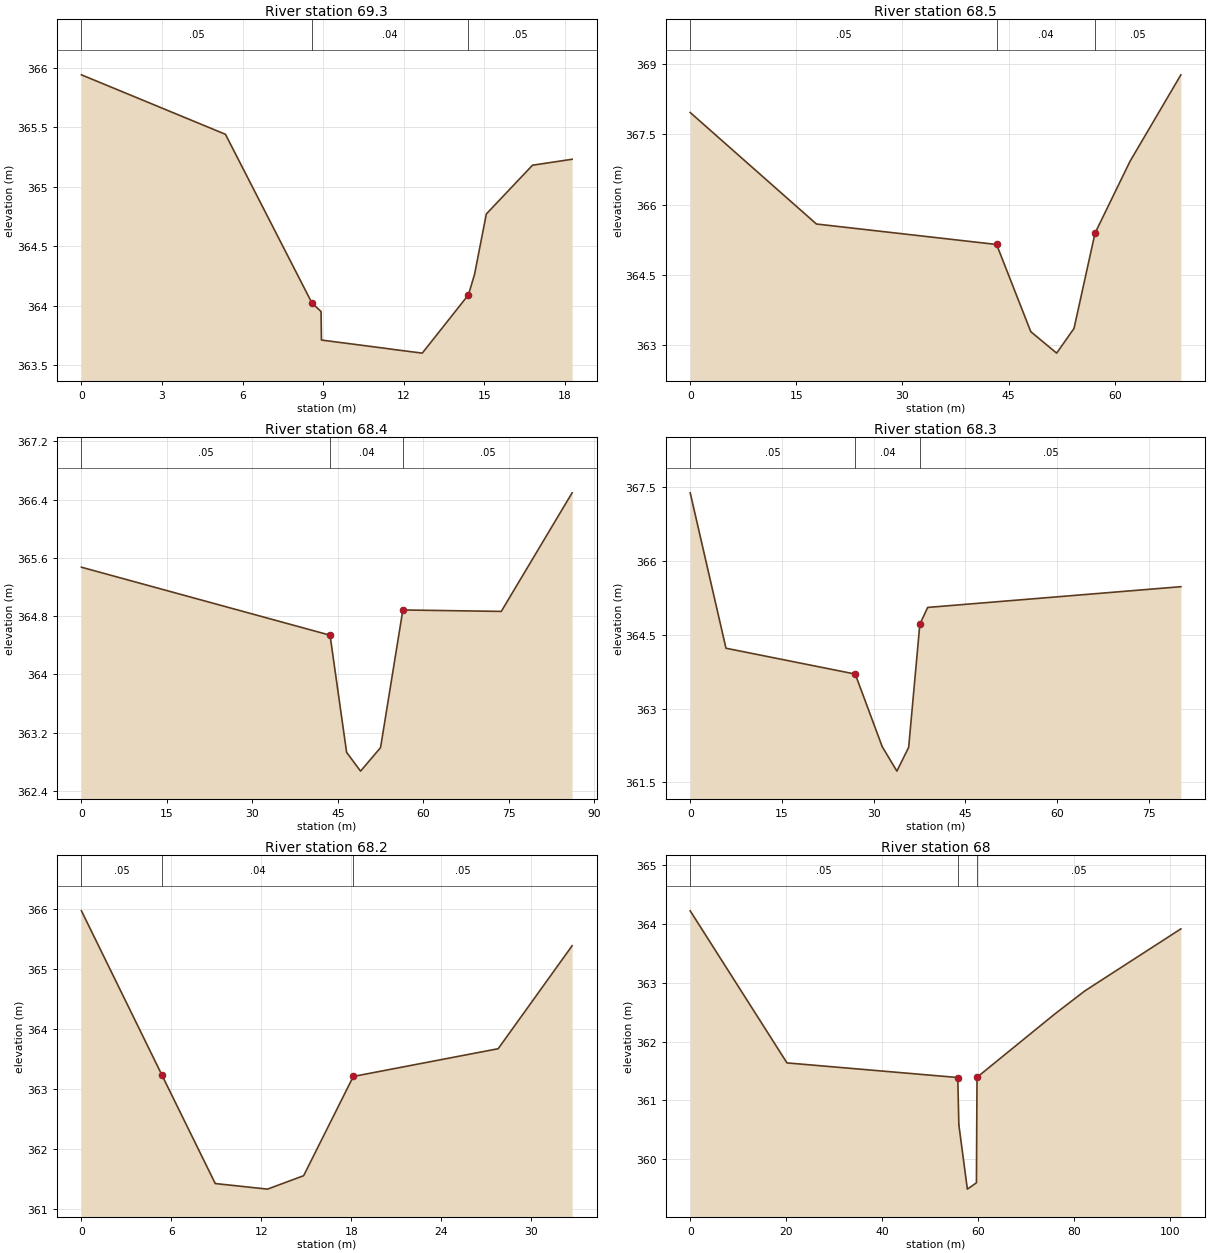
Type RM Length L Ch R = 1 ,69.3    ,72.79,72.79,72.79
XS GIS Cut Line= 6
      3494355.28       5378106.7      3494351.03      5378103.43
      3494348.02      5378101.533494345.340342635378099.17534082
      3494343.12      5378097.89       3494341.1      5378095.44
#Sta/Elev= 13
       0  365.94   5.362  365.44   8.586  364.02   8.922  363.95   8.936  363.71
  11.328  363.64  11.647  363.63  12.691   363.6  14.409  364.09  14.635  364.26
  15.076  364.77  16.795  365.18   18.27  365.23
#Mann= 3 , 0 , 0
       0     .05       0   8.586     .04       0  14.409     .05       0
Bank Sta=8.586,14.409
XS Rating Curve= 0 ,0
Exp/Cntr=0.3,0.1

Type RM Length L Ch R = 1 ,68.5    ,69.24,69.24,69.24
XS GIS Cut Line= 6
     3494409.232     5378154.922      3494419.93     5378107.975
     3494419.777     5378104.332     3494420.389     5378101.954
     3494420.834      5378099.02     3494423.235     5378087.124
#Sta/Elev= 10
       0 367.966  17.839 365.587  43.309  365.15  48.151 363.286  48.172 363.286
  51.798 362.832  54.253  363.36  57.221 365.391  62.168 366.925  69.357  368.77
#Mann= 3 , 0 , 0
       0     .05       0  43.309     .04       0  57.221     .05       0
Bank Sta=43.309,57.221
XS Rating Curve= 0 ,0
Exp/Cntr=0.3,0.1

Type RM Length L Ch R = 1 ,68.4    ,53.35,53.35,53.35
XS GIS Cut Line= 6
     3494508.209     5378156.329     3494492.264     5378115.732
     3494491.293     5378112.992      3494489.39     5378107.351
     3494483.953     5378086.884     3494479.703     5378075.205
#Sta/Elev= 9
       0 365.471  43.616 364.537  46.523 362.927  46.532 362.927  48.968  362.67
  52.477 362.993  56.391 364.884  73.655 364.864  86.083 366.493
#Mann= 3 , 0 , 0
       0     .05       0  43.616     .04       0  56.391     .05       0
Bank Sta=43.616,56.391
XS Rating Curve= 0 ,0
Exp/Cntr=0.3,0.1

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
Type RM Length L Ch R = 1 ,68.3    ,52.12,52.12,52.12
XS GIS Cut Line= 6
     3494609.438      5378113.46     3494606.163     5378108.618
     3494596.638     5378089.756     3494592.987     5378081.822
     3494574.618     5378045.267       3494573.3      5378041.93
#Sta/Elev= 10
       0 367.389   5.846 364.227  26.976 363.701  31.416 362.214  31.436 362.214
  33.785 361.726   35.71  362.21  37.538 364.715  38.817 365.057   80.21 365.479
#Mann= 3 , 0 , 0
       0     .05       0  26.976     .04       0  37.538     .05       0
Bank Sta=26.976,37.538
XS Rating Curve= 0 ,0
Exp/Cntr=0.3,0.1

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
Type RM Length L Ch R = 1 ,68.2    ,78.977,78.977,78.977
XS GIS Cut Line= 6
     3494687.841     5378026.444     3494680.275     5378021.696
     3494677.496     5378019.612     3494675.524      5378018.23
     3494665.197     5378010.381     3494661.374     5378007.268
#Sta/Elev= 9
       0 365.975   5.368 363.232   8.923 361.422   8.932 361.422  12.406 361.329
  14.814 361.553  18.126  363.21  27.785 363.673  32.715 365.392
#Mann= 3 , 0 , 0
       0     .05       0   5.368     .04       0  18.126     .05       0
Bank Sta=5.368,18.126
XS Rating Curve= 0 ,0
Exp/Cntr=0.3,0.1

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
Type RM Length L Ch R = 1 ,68      ,82.13,82.13,82.13
XS GIS Cut Line= 6
     3494889.572     5377914.395     3494877.805     5377898.033
     3494858.629     5377868.071     3494857.638     5377866.341
     3494847.729     5377851.007     3494835.472     5377827.839
#Sta/Elev= 11
       0 364.228  20.154 361.639  55.727  361.39   55.95 360.578   55.96 360.578
  57.722  359.49  59.611 359.598  59.732 361.394  75.982 362.475  82.194 362.865
 102.192 363.921
#Mann= 3 , 0 , 0
       0     .05       0  55.727     .04       0  59.732     .05       0
Bank Sta=55.727,59.732
XS Rating Curve= 0 ,0
Exp/Cntr=0.3,0.1

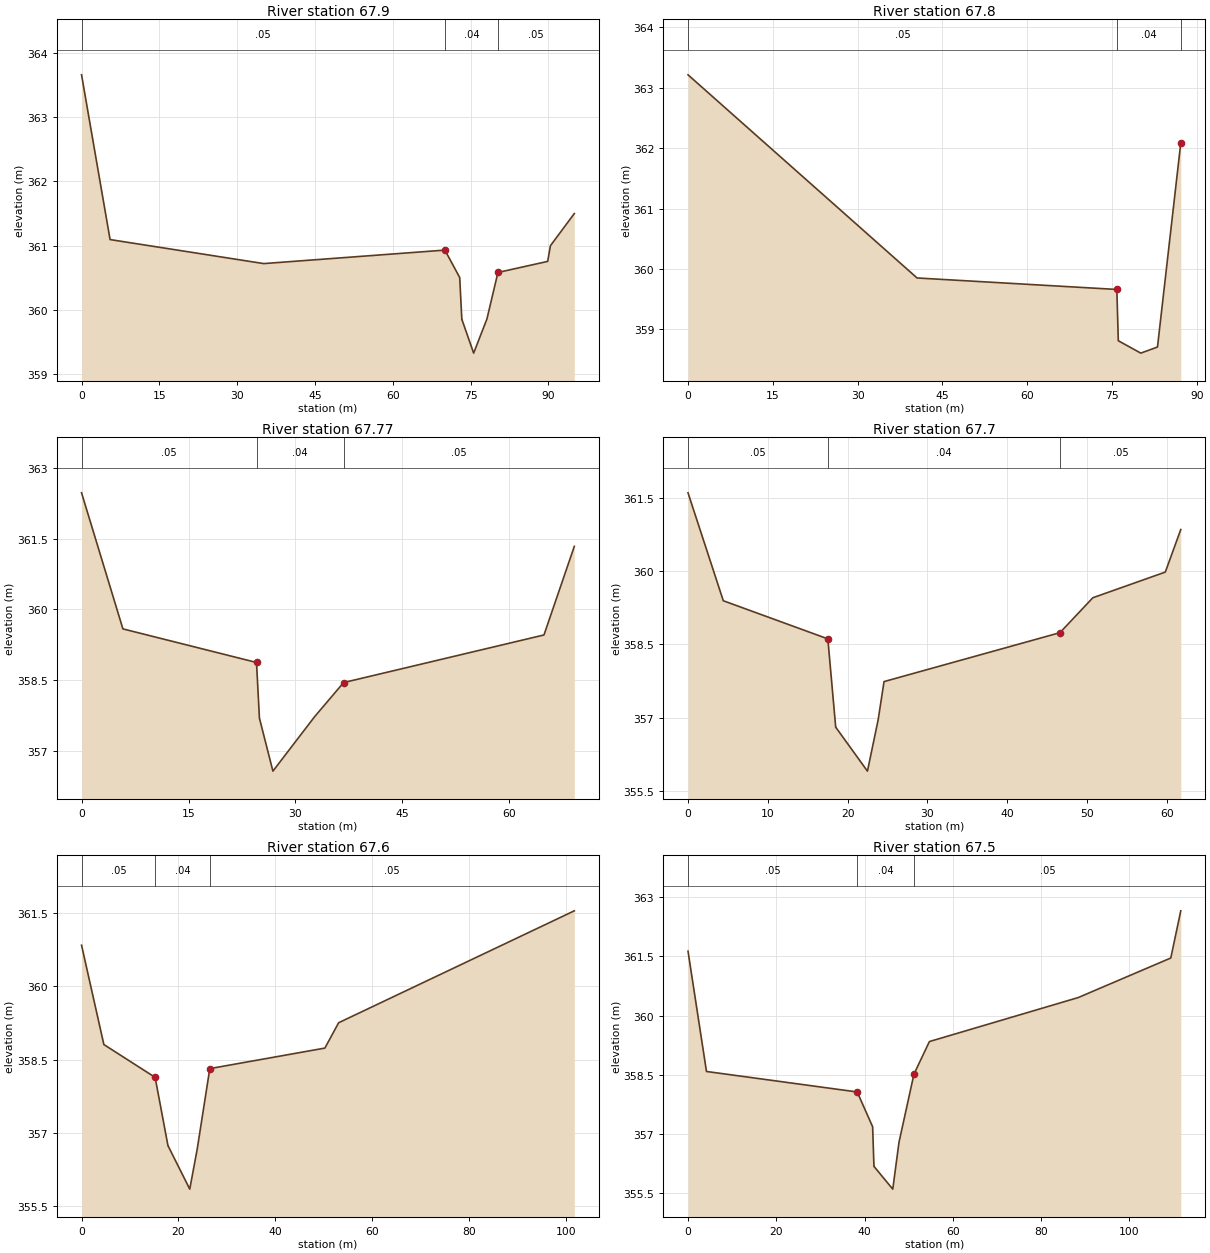
Type RM Length L Ch R = 1 ,67.9    ,53.34,53.34,53.34
XS GIS Cut Line= 6
     3494953.226     5377875.639     3494950.412     5377870.912
     3494920.347     5377813.791     3494916.997     5377809.385
     3494915.787     5377807.127       3494911.6     5377796.198
#Sta/Elev= 13
       0  363.66   5.501 361.095  35.119 360.721  70.055 360.931  72.906 360.504
  73.317 359.849  73.338 359.849  75.594 359.327  78.155 359.859  80.278 360.583
  89.862 360.755    90.4     361      95   361.5
#Mann= 3 , 0 , 0
       0     .05       0  70.055     .04       0  80.278     .05       0
Bank Sta=70.055,80.278
XS Rating Curve= 0 ,0
Exp/Cntr=0.3,0.1

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
Type RM Length L Ch R = 1 ,67.8    ,96.66,96.66,96.66
XS GIS Cut Line= 6
     3495039.899     5377844.631     3495029.687     5377805.436
     3495026.635     5377798.345     3495018.355     5377771.719
     3495017.393     5377767.885     3495015.885     5377760.978
#Sta/Elev= 8
       0 363.212  40.504 359.852   75.83 359.662   76.09 358.813   76.11 358.813
  80.063 358.609  83.017  358.71  87.136 362.085
#Mann= 3 , 0 , 0
       0     .05       0   75.83     .04       0  87.136     .05       0
Bank Sta=75.83,87.136
XS Rating Curve= 0 ,0
Exp/Cntr=0.3,0.1

Type RM Length L Ch R = 1 ,67.77   ,55.615,55.615,55.615
XS GIS Cut Line= 6
     3495129.221     5377823.935     3495127.637     5377818.355
     3495123.102     5377797.834     3495119.805     5377788.496
     3495113.894     5377761.025     3495113.585     5377756.783
#Sta/Elev= 10
       0 362.475     5.8 359.586  24.534 358.873  24.949 357.675  24.969 357.675
  26.835 356.566  32.693 357.724  36.745 358.446  64.844 359.457  69.098 361.338
#Mann= 3 , 0 , 0
       0     .05       0  24.534     .04       0  36.745     .05       0
Bank Sta=24.534,36.745
XS Rating Curve= 0 ,0
Exp/Cntr=0.3,0.1

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
Type RM Length L Ch R = 1 ,67.7    ,91.9,91.9,91.9
XS GIS Cut Line= 6
      3495237.58     5377803.921     3495236.219     5377799.716
     3495232.418     5377782.067     3495232.341     5377779.991
     3495225.025      5377759.19     3495221.396     5377744.493
#Sta/Elev= 12
       0 361.599    4.42 359.392  17.524 358.612  18.512 356.801  18.532 356.801
  22.488 355.907  23.831 356.957  24.566 357.738  46.616 358.739  50.737 359.453
  59.819 359.978  61.757 360.848
#Mann= 3 , 0 , 0
       0     .05       0  17.524     .04       0  46.616     .05       0
Bank Sta=17.524,46.616
XS Rating Curve= 0 ,0
Exp/Cntr=0.3,0.1

Type RM Length L Ch R = 1 ,67.6    ,66.11,66.11,66.11
XS GIS Cut Line= 6
      3495336.49      5377766.56     3495334.207     5377762.561
     3495323.236     5377748.651     3495321.765     5377744.829
     3495307.514     5377725.824     3495275.429     5377685.556
#Sta/Elev= 11
       0 360.845   4.605 358.812  15.187  358.14   17.84  356.74   17.85  356.74
  22.334 355.852  23.872 356.669  26.471 358.319  50.226 358.739  53.065 359.258
 101.713 361.549
#Mann= 3 , 0 , 0
       0     .05       0  15.187     .04       0  26.471     .05       0
Bank Sta=15.187,26.471
XS Rating Curve= 0 ,0
Exp/Cntr=0.3,0.1

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
Type RM Length L Ch R = 1 ,67.5    ,95.18,95.18,95.18
XS GIS Cut Line= 6
     3495444.463     5377670.829     3495441.643     5377667.736
     3495408.226     5377641.952      3495404.92     5377638.471
      3495401.82     5377636.848     3495361.206     5377596.912
#Sta/Elev= 13
       0 361.633   4.186 358.582   38.34 358.062  41.835 357.179  42.132 356.172
  42.153 356.172  46.396 355.597   47.81 356.787    51.2 358.515  54.699 359.341
  88.412 360.457 109.397 361.461 111.659 362.658
#Mann= 3 , 0 , 0
       0     .05       0   38.34     .04       0    51.2     .05       0
Bank Sta=38.34,51.2
XS Rating Curve= 0 ,0
Exp/Cntr=0.3,0.1

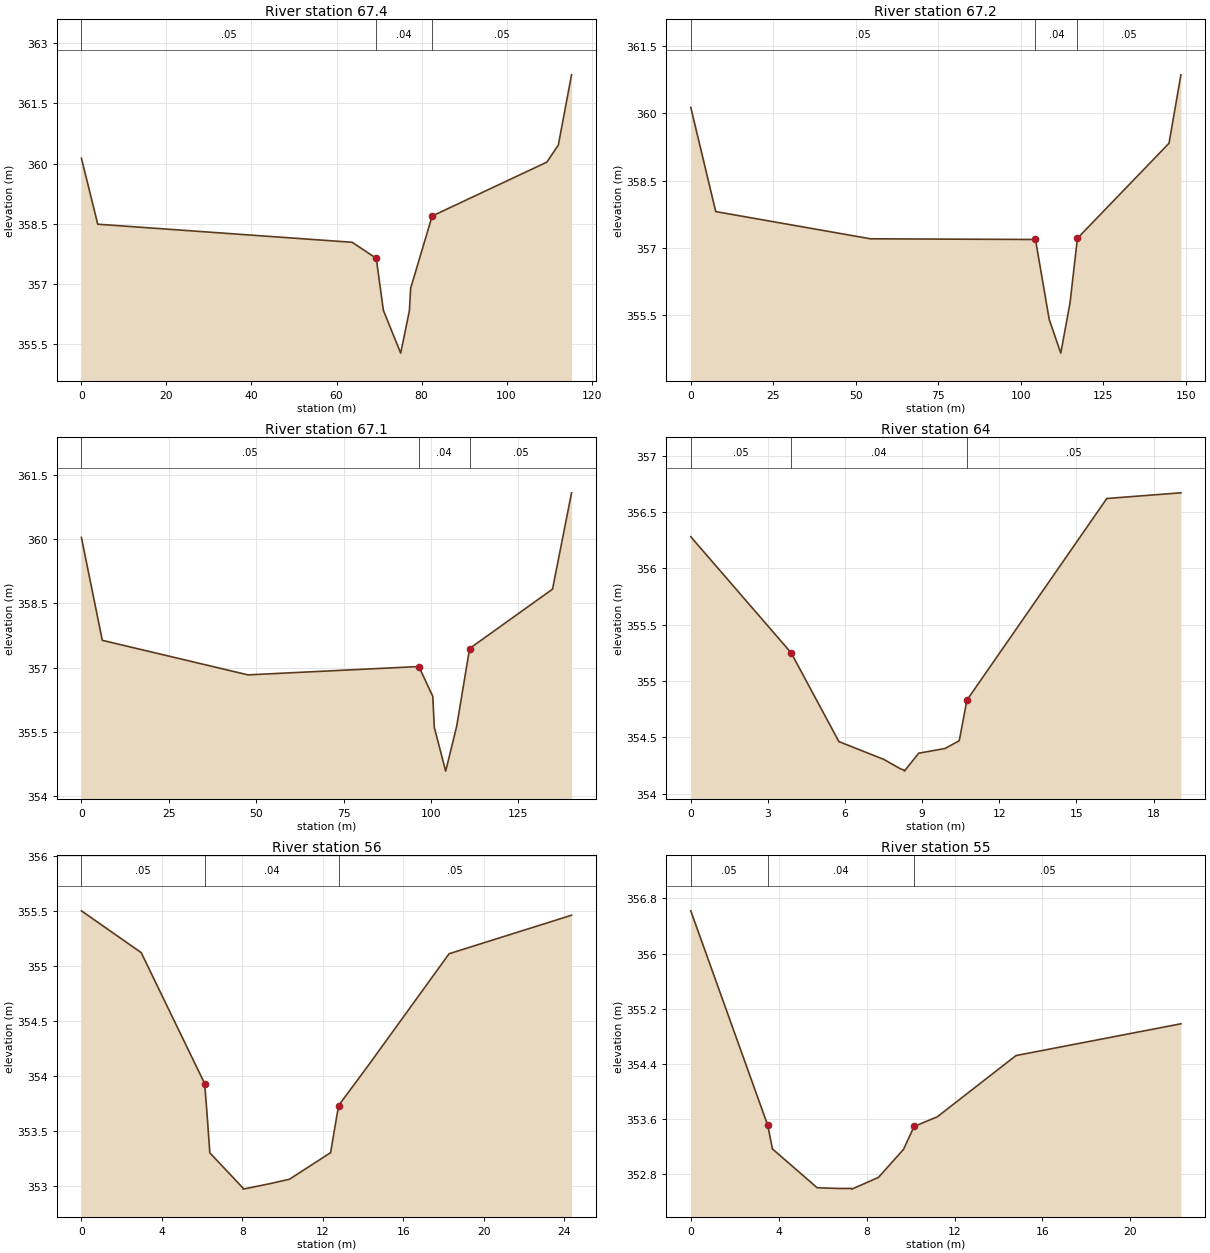
Type RM Length L Ch R = 1 ,67.4    ,87.46,87.46,87.46
XS GIS Cut Line= 6
     3495510.822     5377637.895        3495477.     5377577.371
      3495476.53      5377575.73     3495469.515     5377566.726
     3495454.925     5377540.895     3495453.065     5377538.401
#Sta/Elev= 13
       0 360.137   3.845 358.493  63.689 358.043  69.351 357.644  71.037  356.34
  71.058  356.34  75.099 355.282   77.15 356.342  77.437 356.897  82.504 358.697
 109.473 360.039 112.177 360.464 115.288 362.214
#Mann= 3 , 0 , 0
       0     .05       0  69.351     .04       0  82.504     .05       0
Bank Sta=69.351,82.504
XS Rating Curve= 0 ,0
Exp/Cntr=0.3,0.1

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
Type RM Length L Ch R = 1 ,67.2    ,73.47,73.47,73.47
XS GIS Cut Line= 6
     3495624.058     5377617.788     3495623.971     5377610.224
     3495628.257     5377563.521     3495639.274     5377514.748
     3495635.914     5377504.892     3495638.953      5377471.46
#Sta/Elev= 11
       0 360.137   7.565 357.809  54.464 357.201 104.466 357.186 108.647 355.392
 108.669 355.392 112.129 354.648 114.934 355.769 117.175 357.212 144.939 359.335
 148.538 360.863
#Mann= 3 , 0 , 0
       0     .05       0 104.466     .04       0 117.175     .05       0
Bank Sta=104.466,117.175
XS Rating Curve= 0 ,0
Exp/Cntr=0.3,0.1

Type RM Length L Ch R = 1 ,67.1    ,77.32,77.32,77.32
XS GIS Cut Line= 6
     3495684.255     5377624.031     3495685.647     5377618.224
     3495711.775     5377526.904     3495713.383     5377524.098
     3495713.559     5377520.948     3495723.307     5377489.581
#Sta/Elev= 12
       0 360.039   5.972 357.635  47.647 356.828  96.522 357.023 100.521 356.326
 100.953 355.594 100.974 355.594 104.208  354.58 107.363 355.631 111.051 357.444
 134.769  358.83 140.215  361.08
#Mann= 3 , 0 , 0
       0     .05       0  96.522     .04       0 111.051     .05       0
Bank Sta=96.522,111.051
XS Rating Curve= 0 ,0
Exp/Cntr=0.3,0.1

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
Type RM Length L Ch R = 1 ,64      ,65.8,65.8,65.8
XS GIS Cut Line= 6
      3495849.37       5377573.5      3495851.14      5377570.02
      3495851.65      5377568.23      3495854.66      5377565.51
       3495854.3      5377565.08      3495859.11      5377557.95
#Sta/Elev= 19
       0  356.28   3.904  355.25   5.766  354.46   5.786  354.46   7.442  354.31
   7.462  354.31   8.158  354.22   8.288  354.21   8.308   354.2   8.867  354.36
   8.887  354.36   9.867   354.4   9.881   354.4  10.442  354.47   10.74  354.83
  16.182  356.62  16.202  356.62  19.043  356.67  19.063  356.67
#Mann= 3 , 0 , 0
       0     .05       0   3.904     .04       0   10.74     .05       0
Bank Sta=3.904,10.74
XS Rating Curve= 0 ,0
Exp/Cntr=0.3,0.1

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
Type RM Length L Ch R = 1 ,56      ,55.73,55.73,55.73
XS GIS Cut Line= 6
      3495968.51      5377621.44      3495971.05      5377615.87
      3495971.04      5377615.76      3495973.17      5377610.04
      3495973.16      5377609.64      3495977.45      5377598.89
#Sta/Elev= 15
       0   355.5   2.971  355.12   6.122  353.93   6.232  353.68    6.38   353.3
   8.028  352.98   8.038  352.97    9.37  353.02  10.337  353.06  12.368   353.3
  12.378   353.3  12.778  353.73  14.276   354.1  18.269  355.11  24.352  355.46
#Mann= 3 , 0 , 0
       0     .05       0   6.122     .04       0  12.778     .05       0
Bank Sta=6.122,12.778
XS Rating Curve= 0 ,0
Exp/Cntr=0.3,0.1

Type RM Length L Ch R = 1 ,55      ,35.75,35.75,35.75
XS GIS Cut Line= 6
      3496024.48      5377608.47      3496021.36      5377606.89
      3496019.12      5377606.86      3496018.26      5377606.45
      3496014.89      5377606.01      3496003.06      5377603.37
#Sta/Elev= 16
       0  356.62   3.497  353.51   3.719  353.16   3.729  353.16   5.751   352.6
   6.703  352.59   7.315  352.59   7.325  352.58   8.538  352.75   9.659  353.15
   9.669  353.15   10.16  353.49  11.216  353.63  14.801  354.52  14.811  354.52
  22.299  354.98
#Mann= 3 , 0 , 0
       0     .05       0   3.497     .04       0   10.16     .05       0
Bank Sta=3.497,10.16
XS Rating Curve= 0 ,0
Exp/Cntr=0.3,0.1

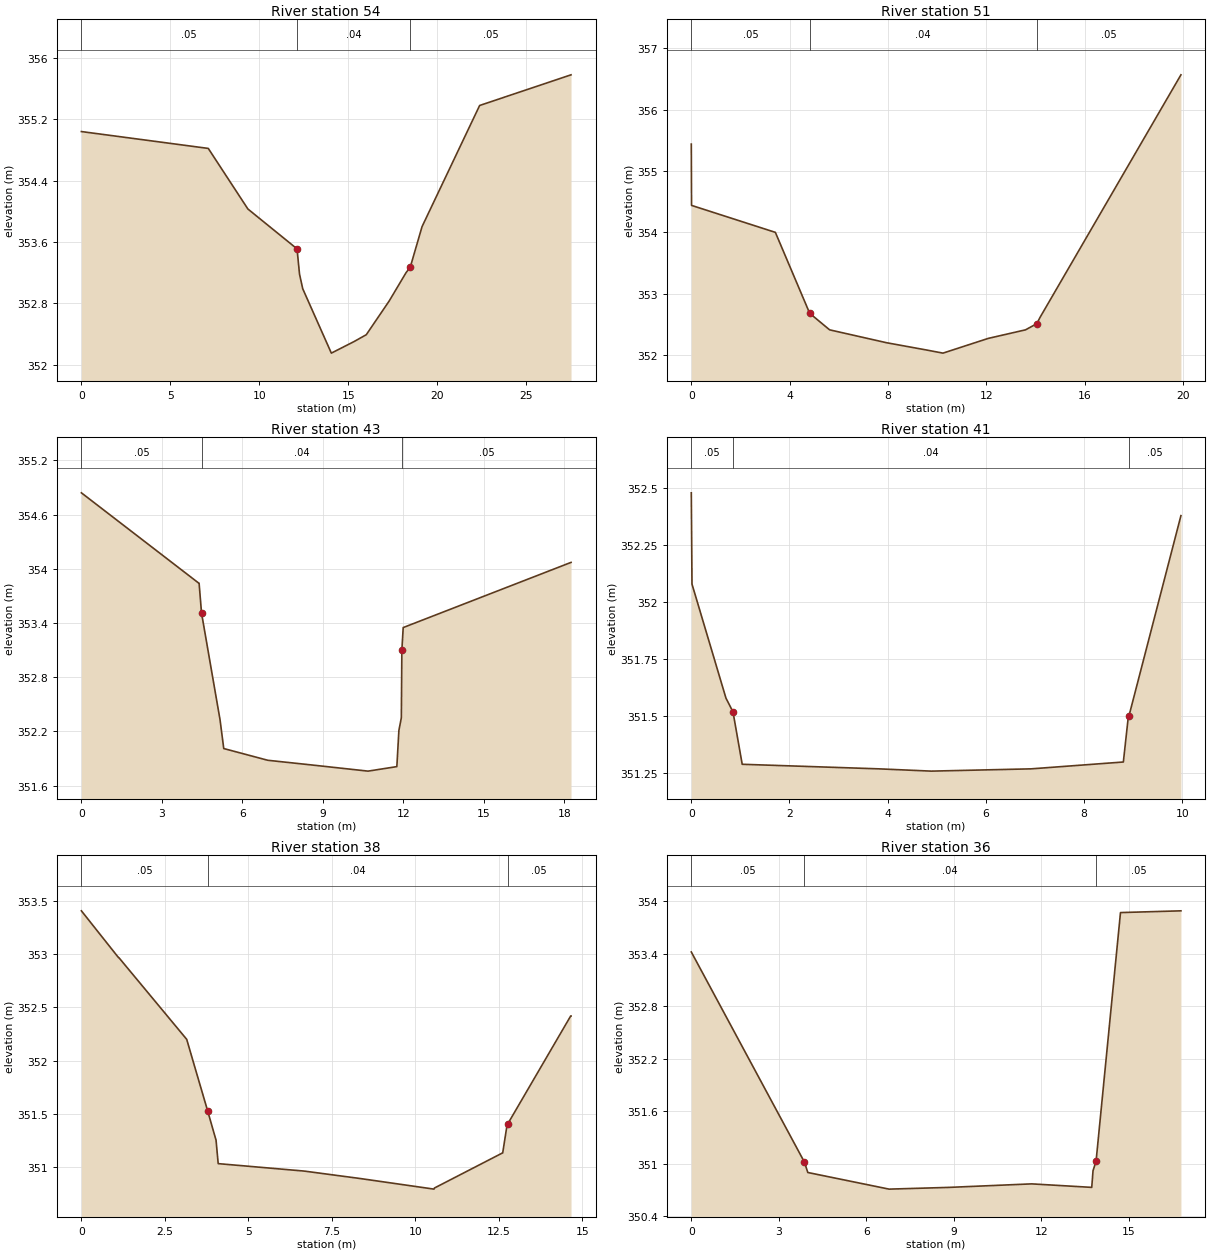
Type RM Length L Ch R = 1 ,54      ,61.53,61.53,61.53
XS GIS Cut Line= 6
      3496043.33      5377585.69      3496039.04      5377579.99
      3496037.36      5377578.53       3496033.2      5377573.47
       3496031.5      5377572.02      3496025.45        5377565.
#Sta/Elev= 15
       0  355.04   7.134  354.82    9.36  354.03  12.123  353.51  12.263  353.18
  12.443  352.99  14.052  352.15  15.321   352.3  16.015  352.39  17.303  352.83
  18.253   353.2  18.486  353.27  19.151   353.8  22.388  355.38  27.526  355.78
#Mann= 3 , 0 , 0
       0     .05       0  12.123     .04       0  18.486     .05       0
Bank Sta=12.123,18.486
XS Rating Curve= 0 ,0
Exp/Cntr=0.3,0.1

Type RM Length L Ch R = 1 ,51      ,89.045,89.045,89.045
XS GIS Cut Line= 6
      3496078.14       5377533.6      3496076.18       5377530.8
      3496075.17      5377528.85      3496073.58      5377527.17
      3496072.54      5377525.15      3496065.63      5377518.39
#Sta/Elev= 13
       0  355.44     .01  354.44    3.42     354   4.816  352.68   5.626  352.41
   7.939   352.2   9.581  352.08  10.238  352.03  12.078  352.27  13.596  352.41
  14.056  352.51  14.182  352.61  19.918  356.57
#Mann= 3 , 0 , 0
       0     .05       0   4.816     .04       0  14.056     .05       0
Bank Sta=4.816,14.056
XS Rating Curve= 0 ,0
Exp/Cntr=0.3,0.1

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
Type RM Length L Ch R = 1 ,43      ,33.34,33.34,33.34
XS GIS Cut Line= 6
      3496204.61      5377411.72      3496202.79      5377407.73
      3496202.05      5377407.84      3496199.78      5377402.93
      3496199.02      5377402.08      3496195.92      5377396.58
#Sta/Elev= 16
       0  354.84   4.376  353.84   4.386  353.84   4.477  353.51   5.166  352.33
   5.305  352.01   6.947  351.88   8.526  351.83  10.683  351.76  11.756  351.81
  11.832  352.21  11.923  352.35  11.943   353.1  11.993  353.35  12.003  353.35
  18.247  354.07
#Mann= 3 , 0 , 0
       0     .05       0   4.477     .04       0  11.943     .05       0
Bank Sta=4.477,11.943
XS Rating Curve= 0 ,0
Exp/Cntr=0.3,0.1

Type RM Length L Ch R = 1 ,41      ,74.25,74.25,74.25
XS GIS Cut Line= 6
      3496231.54      5377394.12      3496231.57      5377393.28
      3496230.23      5377389.47      3496229.91      5377387.46
      3496228.97      5377385.73      3496228.22      5377384.98
#Sta/Elev= 12
       0  352.48    .014  352.08    .706  351.58    .849  351.52   1.037  351.29
   3.817  351.27   4.889  351.26   6.925  351.27   8.801   351.3   8.903   351.5
   8.913   351.5   9.974  352.38
#Mann= 3 , 0 , 0
       0     .05       0    .849     .04       0   8.913     .05       0
Bank Sta=0.849,8.913
XS Rating Curve= 0 ,0
Exp/Cntr=0.3,0.1

Type RM Length L Ch R = 1 ,38      ,43.01,43.01,43.01
XS GIS Cut Line= 6
      3496304.44      5377380.51      3496304.75      5377379.44
      3496303.45      5377376.87       3496303.1      5377374.32
      3496301.76      5377368.56       3496301.6      5377366.55
#Sta/Elev= 19
       0  353.41   1.111  352.97   1.121  352.97   3.155   352.2   3.387  351.95
   3.779  351.53   4.034  351.25   4.057  351.17   4.098  351.03   6.672  350.96
   8.348  350.89  10.563  350.79  10.573   350.8   12.61  351.13   12.62  351.13
  12.754   351.4  12.764   351.4  14.657  352.42  14.667  352.42
#Mann= 3 , 0 , 0
       0     .05       0   3.779     .04       0  12.764     .05       0
Bank Sta=3.779,12.764
XS Rating Curve= 0 ,0
Exp/Cntr=0.3,0.1

Type RM Length L Ch R = 1 ,36      ,65.135,65.135,65.135
XS GIS Cut Line= 6
      3496344.62      5377356.38      3496338.17      5377350.45
      3496335.94      5377348.72      3496334.41      5377347.25
        3496334.      5377346.52      3496332.58      5377345.01
#Sta/Elev= 11
       0  353.42   3.878  351.02   3.996   350.9   6.783  350.71   8.852  350.73
  11.674  350.77  13.734  350.73  13.778  350.92  13.883  351.03   14.72  353.87
  16.793  353.89
#Mann= 3 , 0 , 0
       0     .05       0   3.878     .04       0  13.883     .05       0
Bank Sta=3.878,13.883
XS Rating Curve= 0 ,0
Exp/Cntr=0.3,0.1

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