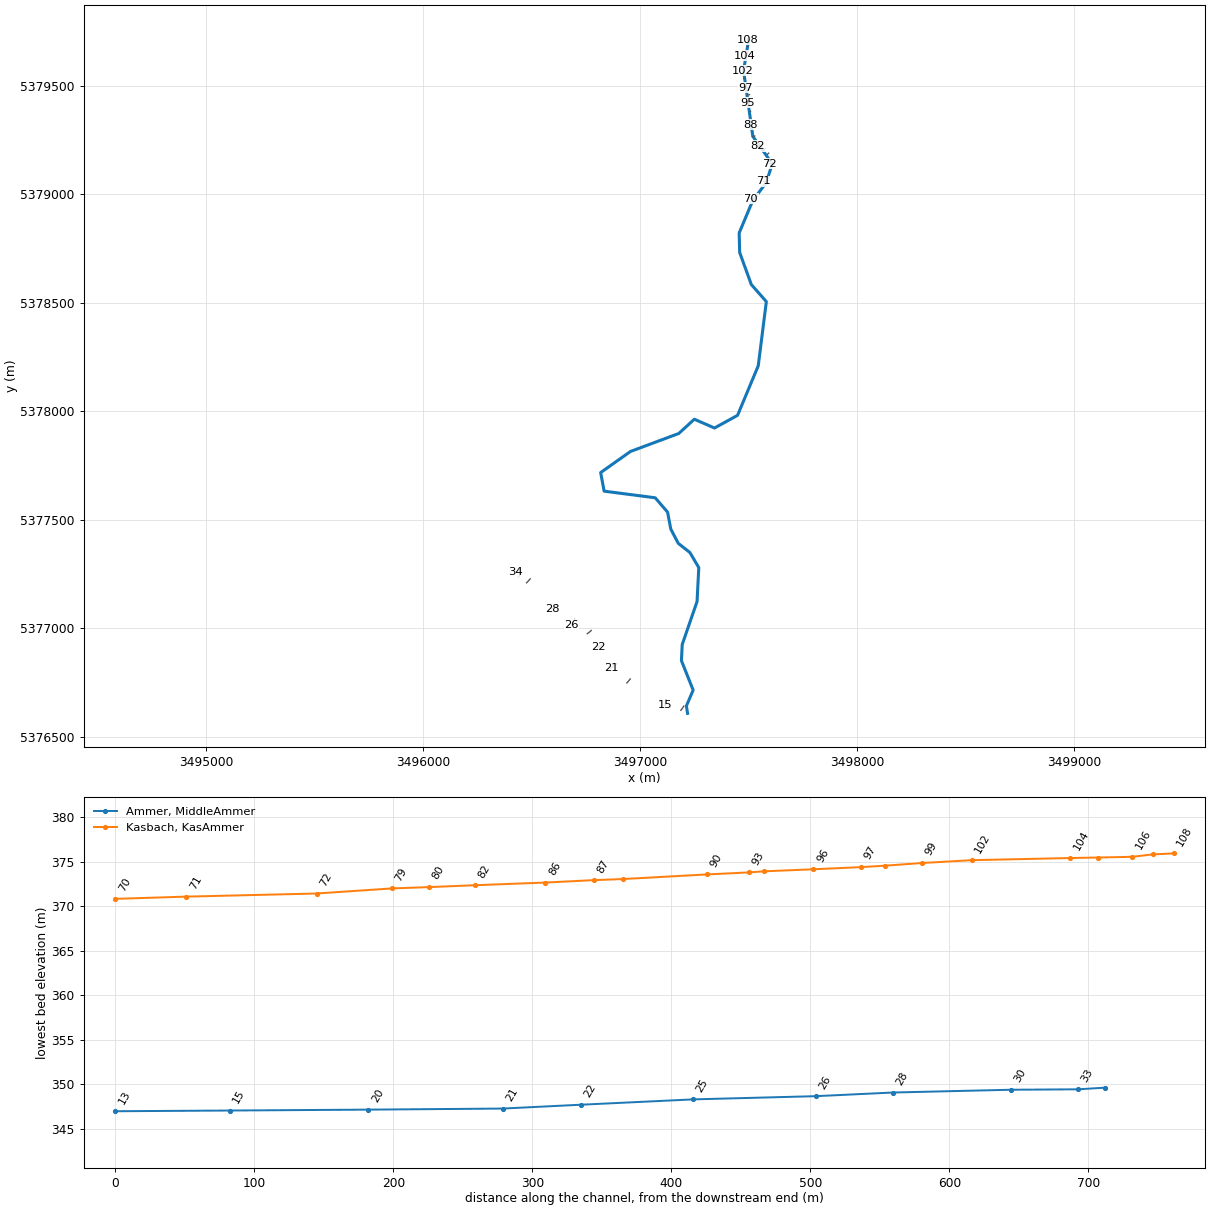
HEC-RAS study Amm_final.prj: Amm_final

--- Amm_final.g04 (geometry) --- (continued)

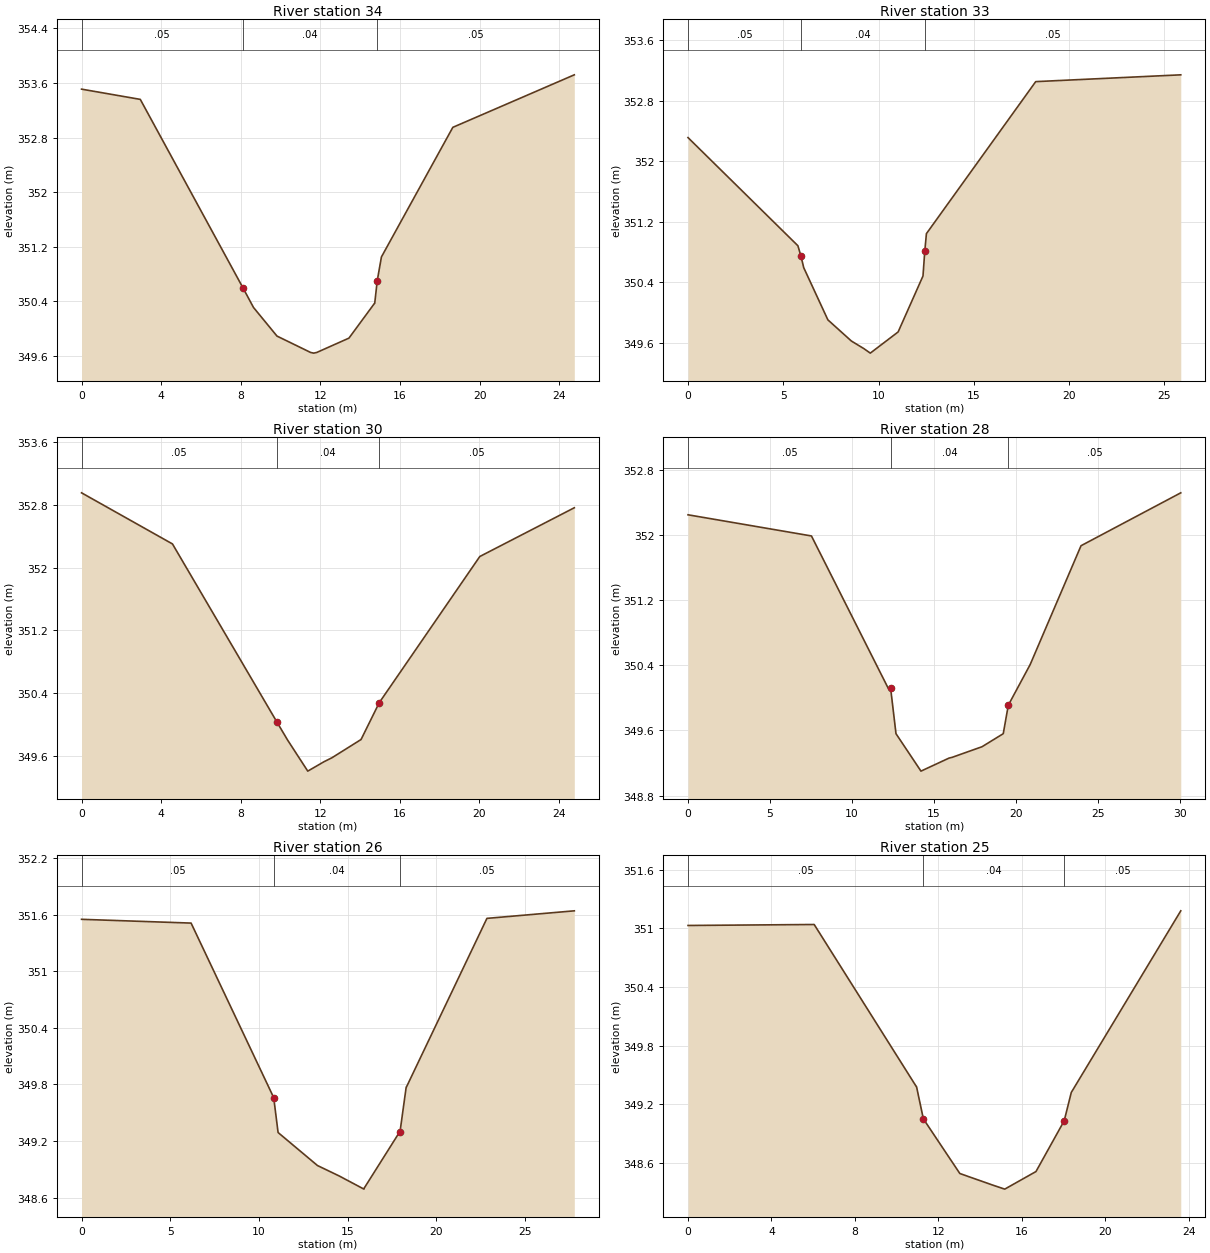
Type RM Length L Ch R = 1 ,34      ,19.08,19.08,19.08
XS GIS Cut Line= 6
      3496442.49      5377269.62      3496435.85       5377264.1
        3496434.      5377261.92      3496433.77      5377262.13
      3496428.89      5377257.45      3496422.89      5377256.34
#Sta/Elev= 15
       0  353.51    2.95  353.36   8.102   350.6   8.635  350.31   9.816  349.89
  11.504  349.65   11.66  349.64  11.816  349.65  13.431  349.86  14.715  350.37
  14.725  350.37  14.851   350.7  15.062  351.05  18.648  352.95   24.75  353.72
#Mann= 3 , 0 , 0
       0     .05       0   8.102     .04       0  14.851     .05       0
Bank Sta=8.102,14.851
XS Rating Curve= 0 ,0
Exp/Cntr=0.3,0.1

Type RM Length L Ch R = 1 ,33      ,48.59,48.59,48.59
XS GIS Cut Line= 6
      3496453.35      5377255.85      3496448.96      5377249.98
      3496447.95      5377249.27      3496445.63      5377246.35
      3496442.79      5377241.16        3496438.      5377235.24
#Sta/Elev= 14
       0  352.31   5.768  350.88   5.932  350.74   6.074  350.59   7.342   349.9
   8.576  349.62   9.229  349.52   9.568  349.46   11.03  349.74  12.335  350.48
  12.429  350.81  12.515  351.04  18.252  353.05  25.867  353.14
#Mann= 3 , 0 , 0
       0     .05       0   5.932     .04       0  12.429     .05       0
Bank Sta=5.932,12.429
XS Rating Curve= 0 ,0
Exp/Cntr=0.3,0.1

Type RM Length L Ch R = 1 ,30      ,84.52,84.52,84.52
XS GIS Cut Line= 6
      3496492.88      5377227.04      3496486.24      5377219.11
      3496483.66      5377216.47      3496483.24      5377215.66
      3496479.55       5377212.2      3496476.37      5377208.67
#Sta/Elev= 12
       0  352.95   4.571   352.3   9.811  350.04  10.349  349.81  11.375  349.41
  12.195  349.53  12.591  349.58  14.041  349.81  14.051  349.81  14.968  350.28
  20.026  352.14  24.778  352.76
#Mann= 3 , 0 , 0
       0     .05       0   9.811     .04       0  14.968     .05       0
Bank Sta=9.811,14.968
XS Rating Curve= 0 ,0
Exp/Cntr=0.3,0.1

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
Type RM Length L Ch R = 1 ,28      ,55.73,55.73,55.73
XS GIS Cut Line= 6
      3496615.05      5377108.64      3496610.06      5377103.01
      3496602.27      5377096.47      3496601.16      5377095.81
      3496600.24      5377094.45      3496593.26      5377088.49
#Sta/Elev= 14
       0  352.25   7.523  351.99  12.198  350.12  12.348  350.12  12.676  349.56
  14.198   349.1  15.906  349.26  16.107  349.27  17.921   349.4  19.213  349.56
  19.521  349.91  20.855  350.41  23.954  351.87  30.033  352.52
#Mann= 3 , 0 , 0
       0     .05       0  12.348     .04       0  19.521     .05       0
Bank Sta=12.348,19.521
XS Rating Curve= 0 ,0
Exp/Cntr=0.3,0.1

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
Type RM Length L Ch R = 1 ,26      ,87.98,87.98,87.98
XS GIS Cut Line= 6
      3496697.66      5377040.11      3496694.66      5377034.71
      3496692.29       5377030.7      3496692.06      5377030.61
      3496688.97      5377024.13       3496684.1      5377016.01
#Sta/Elev= 14
       0  351.55   6.177  351.51  10.835  349.66  11.082  349.29  13.304  348.94
  14.522  348.83  15.926  348.69  15.936   348.7  17.949   349.3  17.959   349.3
  18.304  349.77  18.314  349.77  22.858  351.56  27.785  351.64
#Mann= 3 , 0 , 0
       0     .05       0  10.835     .04       0  17.959     .05       0
Bank Sta=10.835,17.959
XS Rating Curve= 0 ,0
Exp/Cntr=0.3,0.1

Type RM Length L Ch R = 1 ,25      ,81.01,81.01,81.01
XS GIS Cut Line= 6
      3496774.31        5376989.      3496770.08      5376984.68
      3496763.26      5376979.62      3496761.81      5376978.21
      3496760.53      5376977.77      3496756.26      5376974.19
#Sta/Elev= 12
       0  351.03   6.046  351.04   10.94  349.38   10.95  349.38  11.277  349.05
  13.025  348.49  14.618  348.37  15.178  348.33  16.674  348.51  18.027  349.03
  18.366  349.32  23.613  351.18
#Mann= 3 , 0 , 0
       0     .05       0  11.277     .04       0  18.027     .05       0
Bank Sta=11.277,18.027
XS Rating Curve= 0 ,0
Exp/Cntr=0.3,0.1

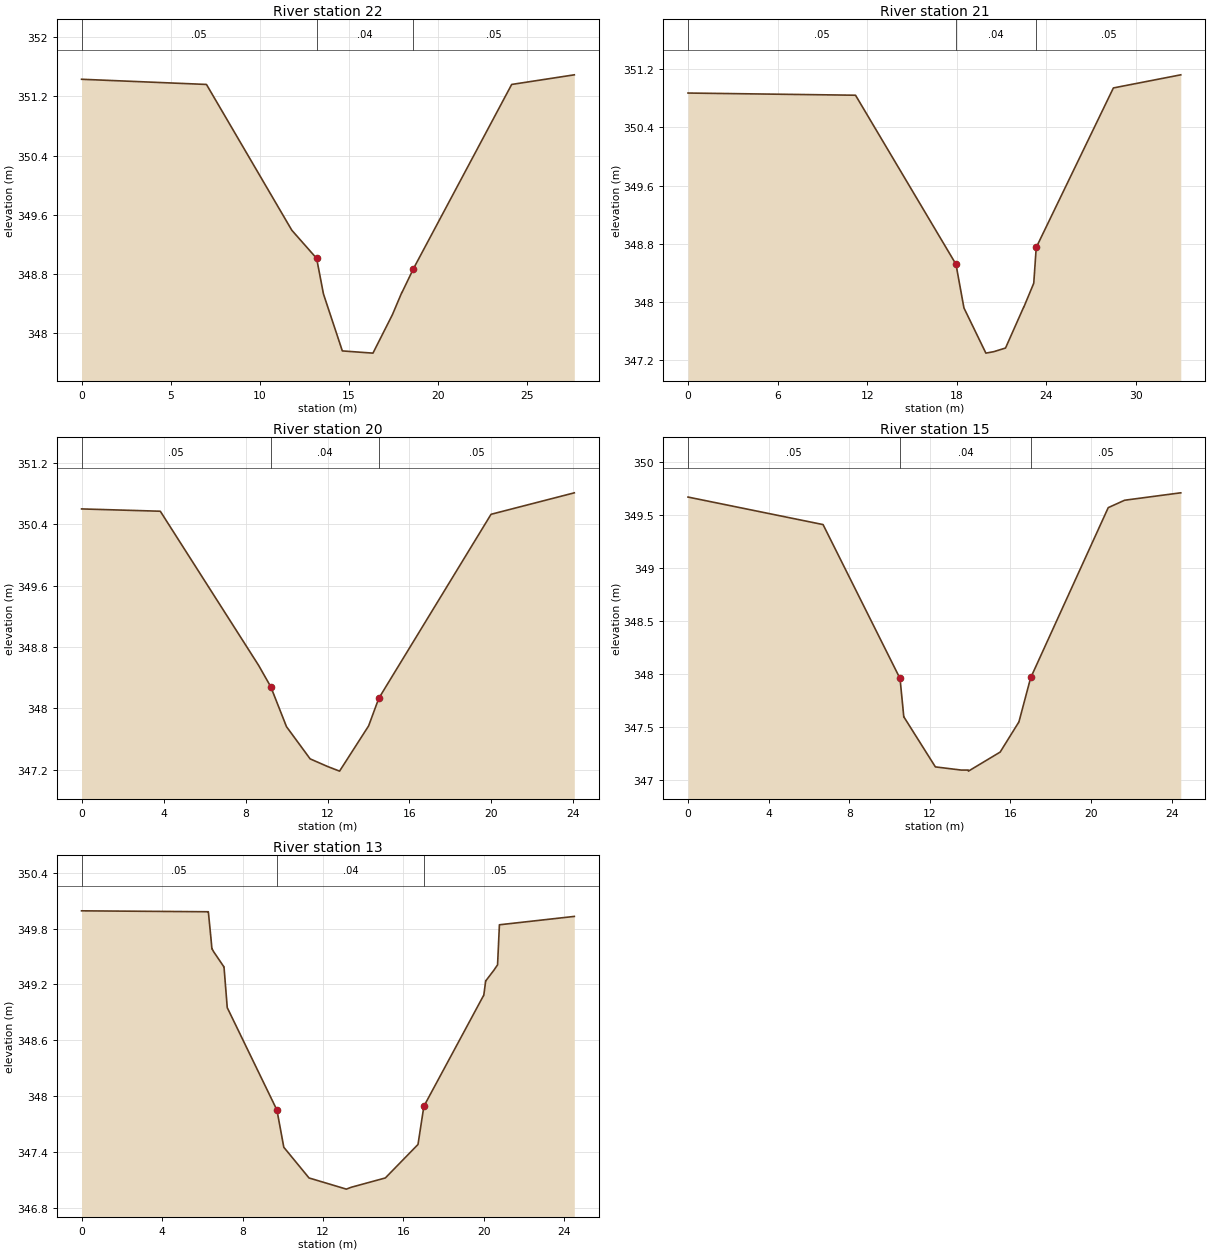
Type RM Length L Ch R = 1 ,22      ,56.19,56.19,56.19
XS GIS Cut Line= 6
      3496828.97      5376927.52      3496818.28      5376919.78
      3496817.28      5376918.74      3496815.01      5376917.09
      3496814.69      5376916.67      3496806.34      5376911.79
#Sta/Elev= 14
       0  351.43   7.015  351.36  11.809  349.39  13.202  349.01  13.584  348.53
  14.645  347.76  15.777  347.74  16.365  347.73  17.458  348.25  17.986  348.55
  17.996  348.55  18.636  348.87  24.155  351.36  27.672  351.49
#Mann= 3 , 0 , 0
       0     .05       0  13.202     .04       0  18.636     .05       0
Bank Sta=13.202,18.636
XS Rating Curve= 0 ,0
Exp/Cntr=0.3,0.1

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
Type RM Length L Ch R = 1 ,21      ,96.5,96.5,96.5
XS GIS Cut Line= 6
      3496893.04      5376836.26      3496884.37      5376829.13
      3496878.92      5376825.18      3496875.62       5376822.1
      3496870.59      5376818.88      3496867.12      5376815.99
#Sta/Elev= 13
       0  350.87  11.225  350.84  17.956  348.52  18.491  347.92  19.961   347.3
  20.492  347.32  21.277  347.37   22.49  347.93    22.5  347.93  23.169  348.26
  23.335  348.75  28.505  350.94  33.021  351.12
#Mann= 3 , 0 , 0
       0     .05       0  17.956     .04       0  23.335     .05       0
Bank Sta=17.956,23.335
XS Rating Curve= 0 ,0
Exp/Cntr=0.3,0.1

Type RM Length L Ch R = 1 ,20      ,99.91,99.91,99.91
XS GIS Cut Line= 6
      3496953.96      5376765.51      3496951.44      5376762.61
      3496948.54      5376758.79      3496948.29      5376758.25
      3496941.23      5376750.15      3496938.48      5376747.16
#Sta/Elev= 12
       0   350.6   3.842  350.57   8.638  348.56   9.233  348.28   9.999  347.76
  11.152  347.34  12.007  347.24  12.589  347.18  14.006  347.77  14.503  348.13
   19.98  350.53  24.042  350.81
#Mann= 3 , 0 , 0
       0     .05       0   9.233     .04       0  14.503     .05       0
Bank Sta=9.233,14.503
XS Rating Curve= 0 ,0
Exp/Cntr=0.3,0.1

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
Type RM Length L Ch R = 1 ,15      ,82.13,82.13,82.13
XS GIS Cut Line= 6
       3497119.5      5376667.47      3497116.18      5376652.38
      3497116.02      5376651.48      3497116.15      5376650.89
      3497114.83      5376646.44      3497114.32       5376643.7
#Sta/Elev= 19
       0  349.67   6.702  349.41   10.51  347.96   10.52  347.96  10.711  347.59
  10.721  347.59  12.277  347.12  13.562  347.09  13.907  347.09  13.917  347.08
  15.492  347.26  16.406  347.54  16.416  347.54  17.016  347.97  17.026  347.97
  20.856  349.57  21.669  349.64  24.446  349.71  24.456  349.71
#Mann= 3 , 0 , 0
       0     .05       0   10.52     .04       0  17.026     .05       0
Bank Sta=10.52,17.026
XS Rating Curve= 0 ,0
Exp/Cntr=0.3,0.1

Type RM Length L Ch R = 1 ,13      ,32.98,32.98,32.98
XS GIS Cut Line= 6
      3497201.23      5376640.43      3497197.55       5376635.2
      3497195.92      5376632.19      3497194.99      5376631.35
      3497192.91      5376628.18      3497187.35      5376620.69
#Sta/Elev= 26
       0  349.99    6.27  349.98   6.302  349.98   6.438  349.68    6.48  349.58
    6.49  349.58   6.567  349.55   7.069  349.39   7.079  349.39   7.241  348.95
    9.71  347.85  10.052  347.45  11.305  347.12  13.161     347  13.403  347.02
  15.098  347.12  16.722  347.48  17.013  347.89  19.979  349.08  19.989  349.08
  20.088  349.24  20.098  349.24  20.487  349.35  20.676  349.41  20.768  349.84
   24.49  349.93
#Mann= 3 , 0 , 0
       0     .05       0    9.71     .04       0  17.013     .05       0
Bank Sta=9.71,17.013
XS Rating Curve= 0 ,0
Exp/Cntr=0.3,0.1

River Reach=Kasbach         ,KasAmmer
Reach XY= 30
3497501.192918945379718.501591723497476.470596635379569.60725767
3497519.209999985379266.56999999 3497608.72532215379140.03805451
3497580.959999935379052.890000033497519.160000165378971.76999988
3497456.250001825378821.289999013497458.540000335378731.39000016
3497512.250069035378583.602596713497581.481192285378504.93086618
      3497544.095378208.809999323497448.769999685377980.71000034
3497342.560000095377922.259999343497249.41025141 5377962.6778749
3497177.765089045377896.981591633496955.319999925377814.19000013
3496817.771863045377716.834103813496833.78000165 5377631.1300012
3497069.199999935377600.689999863497126.189317355377534.41930011
      3497141.075377456.279999213497175.694610015377390.35235776
3497229.005474285377348.498789843497270.100000485377278.83000017
3497262.090000155377122.43000002 3497193.71999985376924.22000003
3497190.100000225376849.829999993497244.12707119 5376714.1170375
3497213.009548685376641.264370353497218.371753315376606.84435723

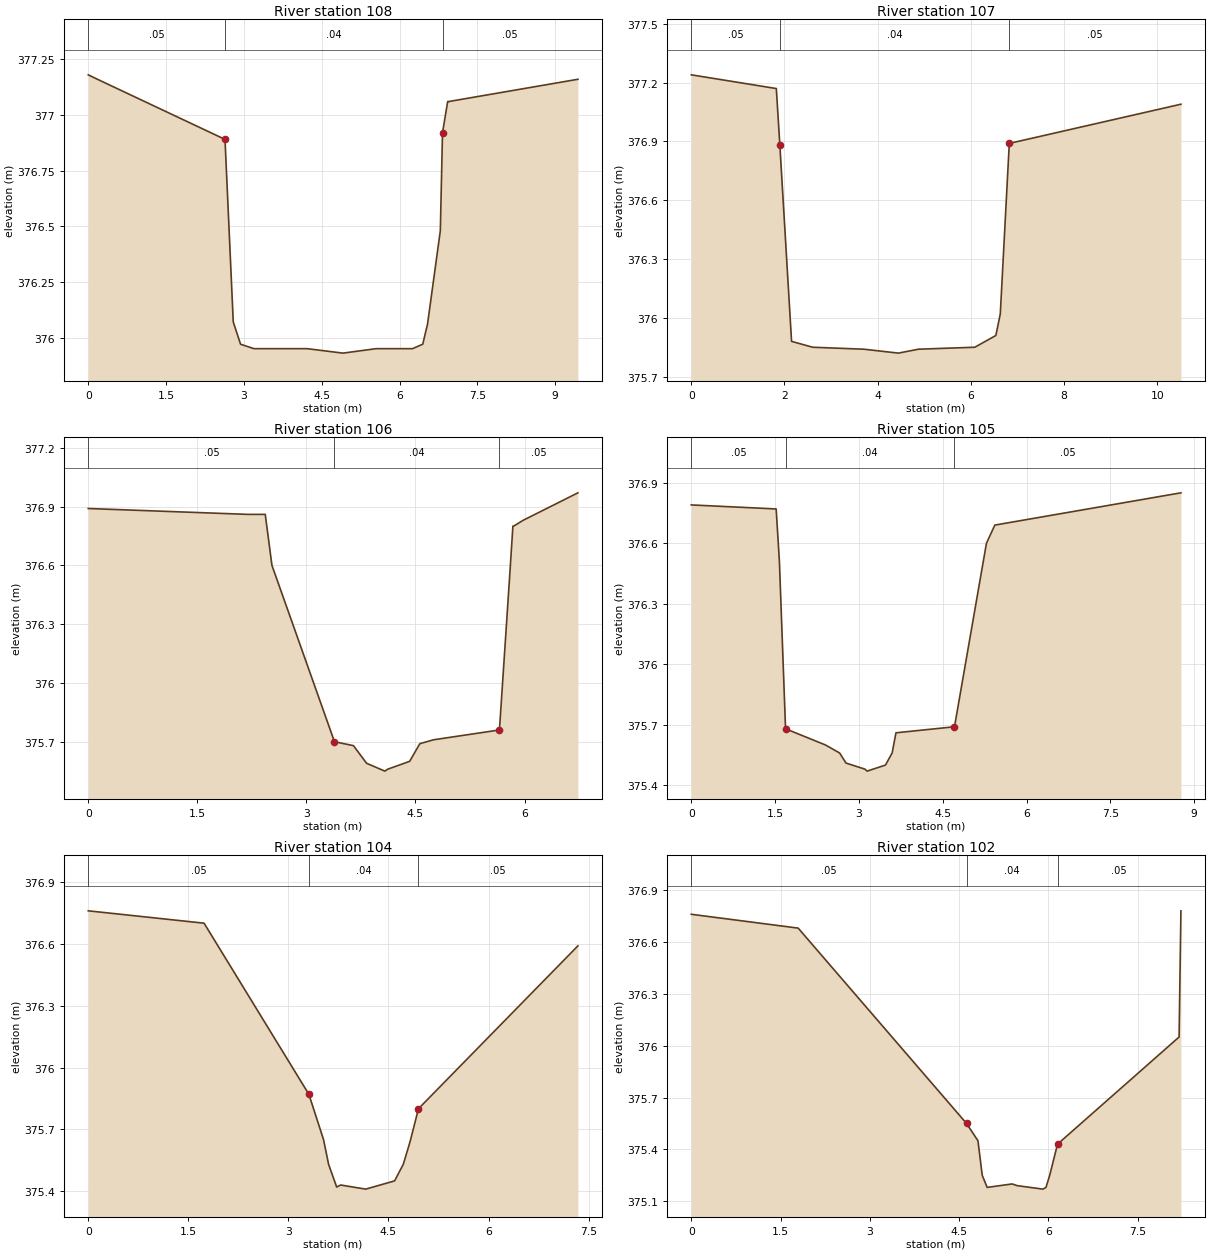
Type RM Length L Ch R = 1 ,108     ,14.99,14.99,14.99
XS GIS Cut Line= 6
      3497499.71      5379706.65      3497497.75      5379708.83
      3497497.27      5379710.02       3497496.6      5379710.18
      3497495.31      5379711.23      3497493.54      5379713.08
#Sta/Elev= 17
       0  377.18    .177  377.16   2.636  376.89   2.795  376.07   2.936  375.97
   3.195  375.95   4.221  375.95    4.91  375.93   5.548  375.95   6.249  375.95
   6.448  375.97    6.54  376.06   6.787  376.48   6.829  376.92   6.929  377.06
   6.949  377.06   9.439  377.16
#Mann= 3 , 0 , 0
       0     .05       0   2.636     .04       0   6.829     .05       0
Bank Sta=2.636,6.829
XS Rating Curve= 0 ,0
Exp/Cntr=0.3,0.1

Type RM Length L Ch R = 1 ,107     ,14.75,14.75,14.75
XS GIS Cut Line= 6
      3497497.03      5379692.08      3497495.81      5379693.48
      3497495.56      5379693.46      3497492.74      5379696.81
      3497492.66      5379696.76      3497490.31      5379699.84
#Sta/Elev= 13
       0  377.24   1.825  377.17   1.901  376.88   2.152  375.88   2.606  375.85
   3.704  375.84   4.446  375.82   4.874  375.84   6.085  375.85   6.537  375.91
   6.632  376.02   6.825  376.89  10.509  377.09
#Mann= 3 , 0 , 0
       0     .05       0   1.901     .04       0   6.825     .05       0
Bank Sta=1.901,6.825
XS Rating Curve= 0 ,0
Exp/Cntr=0.3,0.1

Type RM Length L Ch R = 1 ,106     ,24.34,24.34,24.34
XS GIS Cut Line= 6
      3497498.16        5379682.      3497495.97      5379681.84
      3497495.75      5379681.91      3497495.73      5379681.82
      3497493.51       5379681.7      3497491.55       5379681.5
#Sta/Elev= 18
       0  376.89   2.196  376.86   2.434  376.86   2.526   376.6   3.386   375.7
   3.647  375.68   3.828  375.59   4.079  375.55   4.119  375.56    4.42   375.6
    4.56  375.69    4.75  375.71   5.655  375.76     5.8  376.57    5.84   376.8
    5.85   376.8   5.982  376.83   6.734  376.97
#Mann= 3 , 0 , 0
       0     .05       0   3.386     .04       0   5.655     .05       0
Bank Sta=3.386,5.655
XS Rating Curve= 0 ,0
Exp/Cntr=0.3,0.1

Type RM Length L Ch R = 1 ,105     ,20.62,20.62,20.62
XS GIS Cut Line= 6
      3497495.94      5379656.71      3497491.47       5379657.8
      3497491.21      5379657.29      3497491.26       5379657.8
      3497491.02      5379657.31      3497488.79      5379657.58
#Sta/Elev= 16
       0  376.79   1.519  376.77   1.577  376.51   1.687  375.68   2.399   375.6
   2.655  375.56   2.769  375.51   3.107  375.48   3.147  375.47   3.475   375.5
   3.595  375.56   3.663  375.66   4.711  375.69   5.283   376.6   5.433  376.69
   8.764  376.85
#Mann= 3 , 0 , 0
       0     .05       0   1.687     .04       0   4.711     .05       0
Bank Sta=1.687,4.711
XS Rating Curve= 0 ,0
Exp/Cntr=0.3,0.1

Type RM Length L Ch R = 1 ,104     ,70.61,70.61,70.61
XS GIS Cut Line= 6
      3497489.65      5379636.57      3497488.08      5379637.31
      3497486.62      5379637.89      3497485.31      5379638.31
      3497485.18      5379638.47      3497482.97      5379639.38
#Sta/Elev= 13
       0  376.76   1.736   376.7   3.307  375.87   3.527  375.65   3.603  375.53
   3.724  375.42   3.783  375.43   4.159  375.41   4.592  375.45   4.722  375.53
   4.824  375.64    4.95   375.8    7.34  376.59
#Mann= 3 , 0 , 0
       0     .05       0   3.307     .04       0    4.95     .05       0
Bank Sta=3.307,4.95
XS Rating Curve= 0 ,0
Exp/Cntr=0.3,0.1

Type RM Length L Ch R = 1 ,102     ,35.98,35.98,35.98
XS GIS Cut Line= 6
      3497481.89      5379569.08      3497480.11      5379569.32
      3497477.29      5379569.55      3497476.53      5379569.58
      3497475.83      5379569.44      3497473.85      5379570.04
#Sta/Elev= 14
       0  376.76   1.796  376.68   4.625  375.55   4.817  375.45   4.889  375.25
   4.972  375.18   5.392   375.2   5.478  375.19   5.909  375.17    5.96  375.18
   6.023  375.25   6.154  375.43   8.197  376.05   8.228  376.78
#Mann= 3 , 0 , 0
       0     .05       0   4.625     .04       0   6.154     .05       0
Bank Sta=4.625,6.154
XS Rating Curve= 0 ,0
Exp/Cntr=0.3,0.1

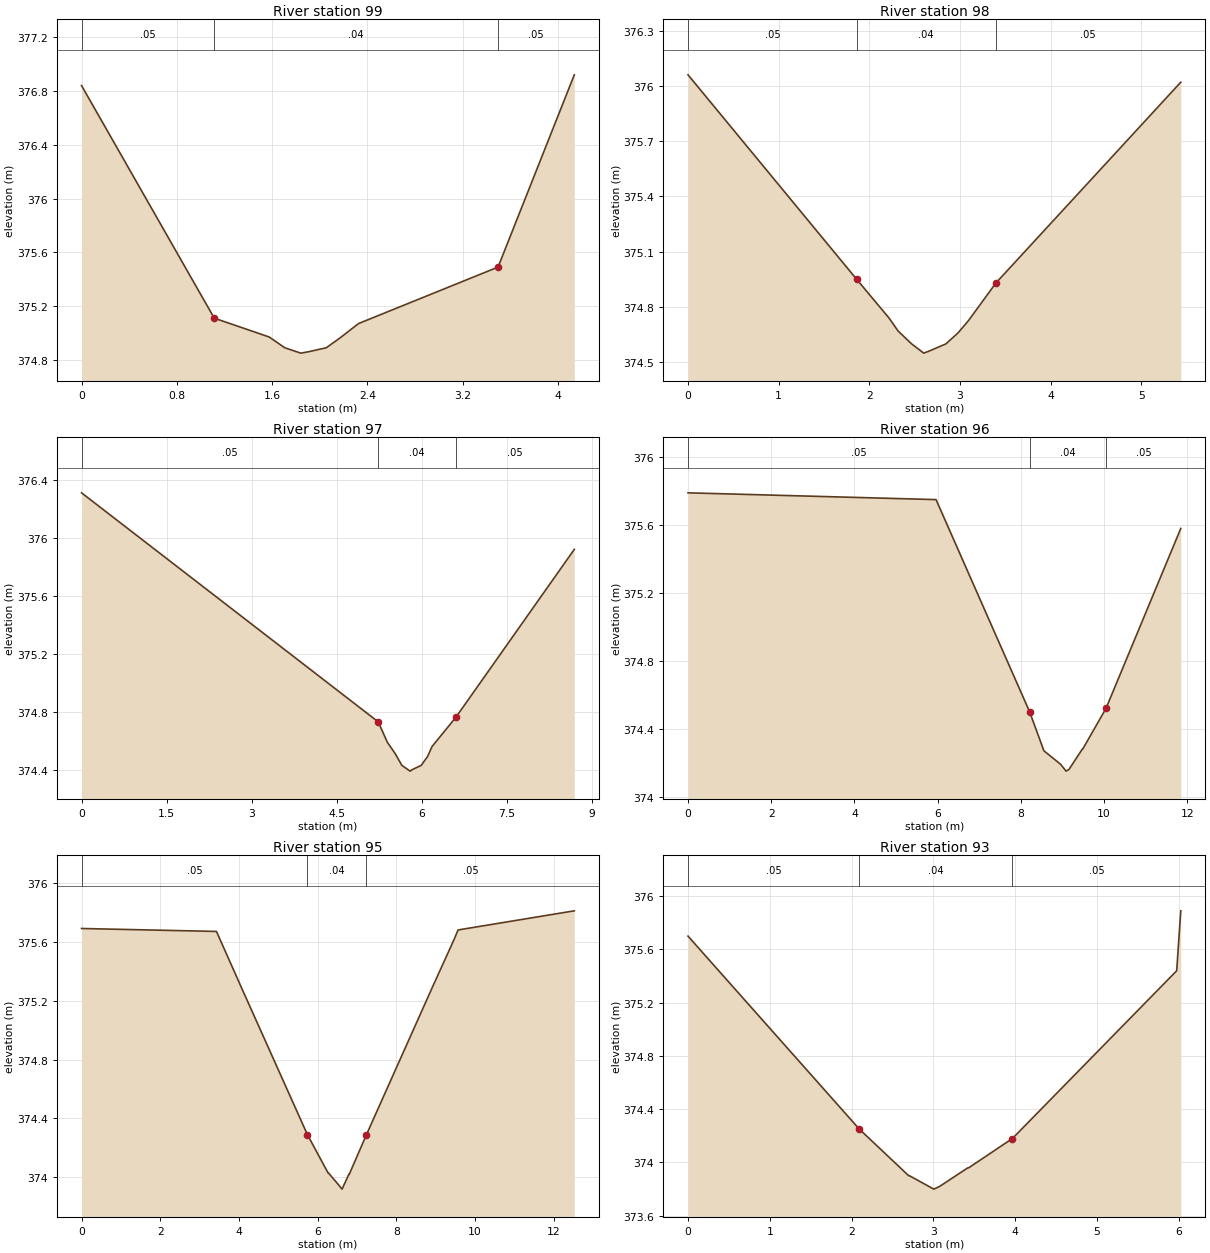
Type RM Length L Ch R = 1 ,99      ,26.7,26.7,26.7
XS GIS Cut Line= 6
      3497482.64        5379534.      3497481.53      5379533.91
      3497480.83      5379533.73      3497480.37      5379533.78
      3497479.22      5379533.56       3497479.2      5379532.92
#Sta/Elev= 11
       0  376.84   1.114  375.11   1.575  374.97   1.706  374.89    1.84  374.85
   1.904  374.86   2.054  374.89   2.165  374.96   2.325  375.07   3.496  375.49
   4.136  376.92
#Mann= 3 , 0 , 0
       0     .05       0   1.114     .04       0   3.496     .05       0
Bank Sta=1.114,3.496
XS Rating Curve= 0 ,0
Exp/Cntr=0.3,0.1

Type RM Length L Ch R = 1 ,98      ,17.07,17.07,17.07
XS GIS Cut Line= 6
      3497489.32      5379508.18      3497487.06      5379507.68
      3497486.54      5379507.66      3497486.42       5379507.6
      3497486.01      5379507.54      3497483.98      5379507.33
#Sta/Elev= 12
       0  376.06   1.861  374.95   2.218  374.74   2.317  374.67   2.467   374.6
     2.6  374.55   2.654  374.56   2.844   374.6   2.979  374.66   3.099  374.73
   3.395  374.93   5.435  376.02
#Mann= 3 , 0 , 0
       0     .05       0   1.861     .04       0   3.395     .05       0
Bank Sta=1.861,3.395
XS Rating Curve= 0 ,0
Exp/Cntr=0.3,0.1

Type RM Length L Ch R = 1 ,97      ,34.11,34.11,34.11
XS GIS Cut Line= 6
       3497495.7      5379491.56      3497490.34        5379491.
      3497489.97      5379490.85      3497489.94      5379490.87
      3497489.59      5379490.85      3497487.18      5379490.16
#Sta/Elev= 12
       0  376.31   5.229  374.73   5.389  374.59   5.529  374.51   5.645  374.43
   5.791  374.39   5.827   374.4   5.987  374.43   6.097  374.49   6.178  374.56
   6.595  374.76   8.685  375.92
#Mann= 3 , 0 , 0
       0     .05       0   5.229     .04       0   6.595     .05       0
Bank Sta=5.229,6.595
XS Rating Curve= 0 ,0
Exp/Cntr=0.3,0.1

Type RM Length L Ch R = 1 ,96      ,35.41,35.41,35.41
XS GIS Cut Line= 6
      3497503.62      5379458.75      3497495.53      5379457.35
      3497494.89      5379456.97      3497494.89      5379456.77
      3497494.15      5379456.38      3497492.38      5379456.07
#Sta/Elev= 11
       0  375.79   5.964  375.75   8.213   374.5   8.557  374.27    8.96  374.19
    9.09  374.15    9.16  374.16   9.481  374.28   9.491  374.28  10.051  374.52
  11.848  375.58
#Mann= 3 , 0 , 0
       0     .05       0   8.213     .04       0  10.051     .05       0
Bank Sta=8.213,10.051
XS Rating Curve= 0 ,0
Exp/Cntr=0.3,0.1

Type RM Length L Ch R = 1 ,95      ,10.77,10.77,10.77
XS GIS Cut Line= 6
      3497506.18      5379423.42      3497502.21      5379422.56
      3497500.55      5379422.31      3497500.06      5379422.12
      3497499.72      5379422.11      3497493.99      5379420.78
#Sta/Elev= 15
       0  375.69   3.429  375.67   4.062  375.29   5.741  374.29   6.266  374.03
   6.276  374.03    6.53  373.95   6.622  373.92   6.793  374.02   6.803  374.02
   7.242  374.29   8.899  375.28    9.46  375.61    9.57  375.68  12.525  375.81
#Mann= 3 , 0 , 0
       0     .05       0   5.741     .04       0   7.242     .05       0
Bank Sta=5.741,7.242
XS Rating Curve= 0 ,0
Exp/Cntr=0.3,0.1

Type RM Length L Ch R = 1 ,93      ,30.54,30.54,30.54
XS GIS Cut Line= 6
      3497504.19      5379412.67      3497502.37      5379411.63
      3497501.82      5379411.38      3497501.12      5379411.52
      3497500.62      5379411.33      3497498.59      5379411.08
#Sta/Elev= 11
       0   375.7   2.096  374.25     2.7   373.9    2.71   373.9   3.006   373.8
   3.076  373.82   3.422  373.96   3.432  373.96   3.967  374.18   5.976  375.44
   6.026  375.89
#Mann= 3 , 0 , 0
       0     .05       0   2.096     .04       0   3.967     .05       0
Bank Sta=2.096,3.967
XS Rating Curve= 0 ,0
Exp/Cntr=0.3,0.1

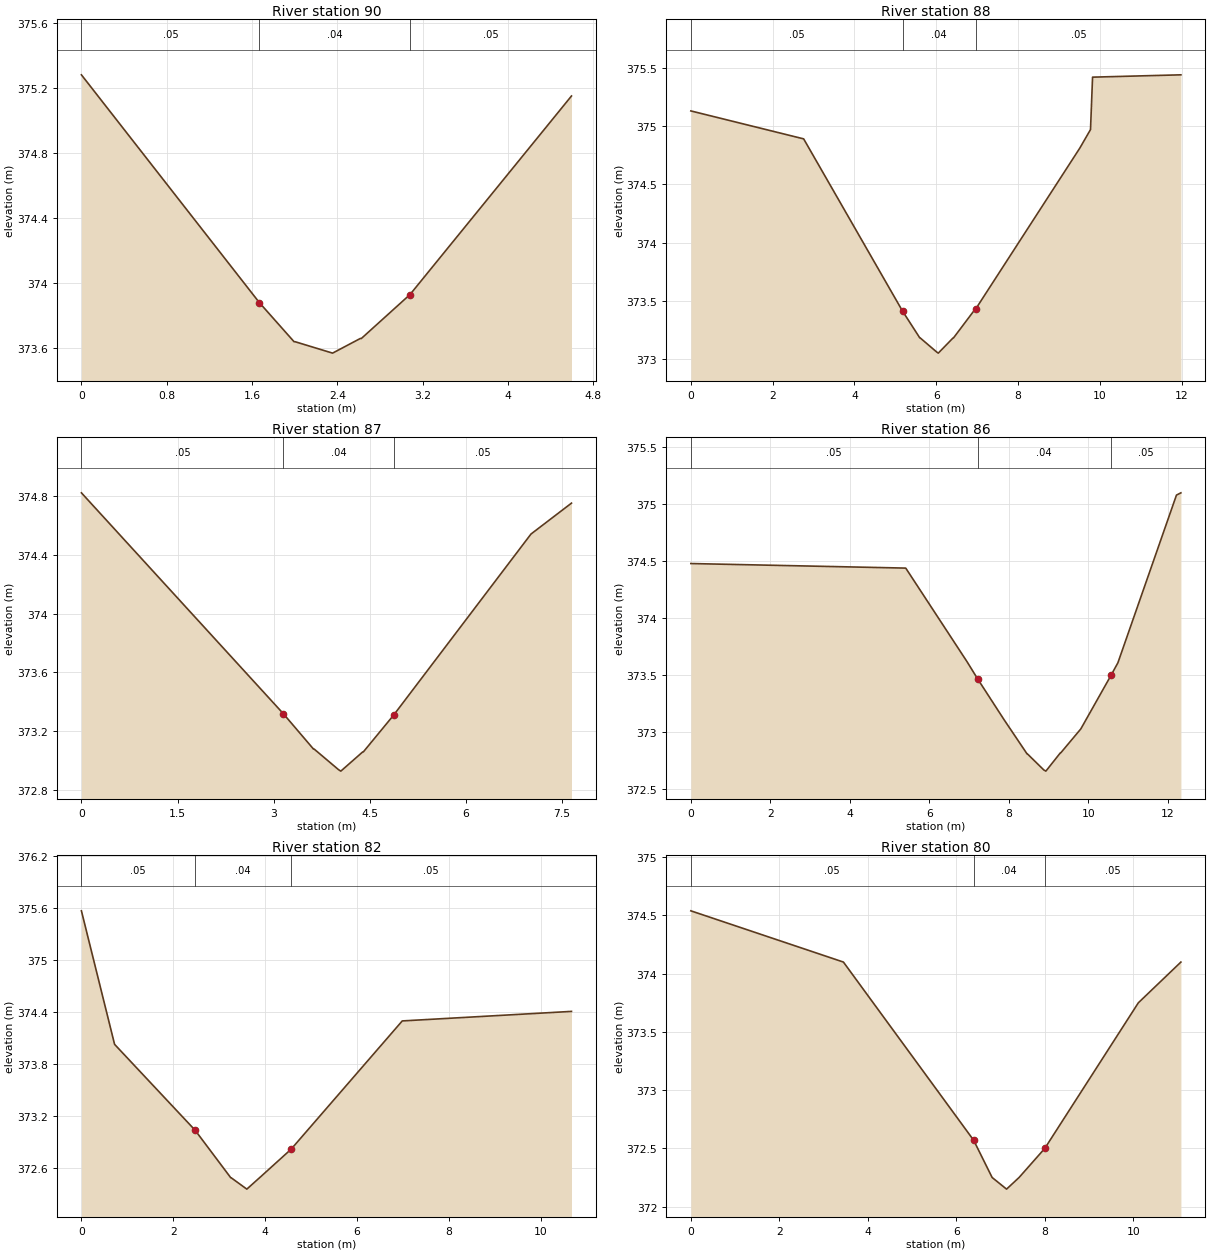
Type RM Length L Ch R = 1 ,90      ,60.61,60.61,60.61
XS GIS Cut Line= 6
      3497508.58       5379381.6      3497506.92      5379381.43
      3497506.32      5379381.26      3497506.28      5379381.29
       3497505.6      5379381.08       3497504.1      5379380.88
#Sta/Elev= 10
       0  375.28   1.669  373.88   1.994  373.64   2.004  373.64   2.305  373.58
   2.355  373.57   2.615  373.66   2.625  373.66   3.081  373.93   4.595  375.15
#Mann= 3 , 0 , 0
       0     .05       0   1.669     .04       0   3.081     .05       0
Bank Sta=1.669,3.081
XS Rating Curve= 0 ,0
Exp/Cntr=0.3,0.1

Type RM Length L Ch R = 1 ,88      ,20.74,20.74,20.74
XS GIS Cut Line= 6
       3497517.9      5379321.95      3497515.27      5379321.12
      3497512.44      5379320.87      3497511.64      5379320.93
      3497508.63       5379320.3      3497506.17      5379320.37
#Sta/Elev= 15
       0  375.13   2.758  374.89   5.177  373.41   5.599  373.18   5.609  373.18
   6.009  373.06   6.049  373.05    6.41  373.18    6.42  373.18   6.956  373.43
   6.966  373.43   9.508  374.81   9.771  374.97   9.821  375.42  11.981  375.44
#Mann= 3 , 0 , 0
       0     .05       0   5.177     .04       0   6.966     .05       0
Bank Sta=5.177,6.966
XS Rating Curve= 0 ,0
Exp/Cntr=0.3,0.1

Type RM Length L Ch R = 1 ,87      ,34.7,34.7,34.7
XS GIS Cut Line= 6
      3497517.59      5379300.26      3497513.97      5379300.28
      3497513.22      5379300.26      3497512.76      5379300.15
      3497510.63      5379299.91        3497510.      5379299.96
#Sta/Elev= 11
       0  374.82    3.15  373.32    3.62  373.08    3.63  373.08   4.011  372.94
   4.047  372.93   4.387  373.06   4.397  373.06    4.87  373.31   7.013  374.54
   7.645  374.75
#Mann= 3 , 0 , 0
       0     .05       0    3.15     .04       0    4.87     .05       0
Bank Sta=3.15,4.87
XS Rating Curve= 0 ,0
Exp/Cntr=0.3,0.1

Type RM Length L Ch R = 1 ,86      ,50.82,50.82,50.82
XS GIS Cut Line= 6
      3497527.89      5379268.56      3497520.84      5379267.04
      3497518.37      5379266.36      3497517.61      5379266.34
        3497516.        5379266.      3497515.98      5379266.11
#Sta/Elev= 16
       0  374.48   5.406  374.44   6.947  373.62   7.212  373.47   7.881  373.11
    8.46  372.81    8.47  372.81    8.88  372.67   8.931  372.66   9.295  372.82
   9.305  372.82    9.81  373.03   10.57   373.5  10.743  373.61  12.216  375.08
  12.328   375.1
#Mann= 3 , 0 , 0
       0     .05       0   7.212     .04       0   10.57     .05       0
Bank Sta=7.212,10.57
XS Rating Curve= 0 ,0
Exp/Cntr=0.3,0.1

Type RM Length L Ch R = 1 ,82      ,32.89,32.89,32.89
XS GIS Cut Line= 6
      3497548.86      5379231.14      3497547.29      5379229.23
      3497546.98      5379228.52      3497546.79      5379228.24
      3497544.78      5379225.52      3497542.67       5379222.5
#Sta/Elev= 10
       0  375.57    .722  374.03   2.474  373.04   3.253  372.49   3.263  372.49
   3.601  372.36   3.917  372.51   4.564  372.82   6.984   374.3  10.668  374.41
#Mann= 3 , 0 , 0
       0     .05       0   2.474     .04       0   4.564     .05       0
Bank Sta=2.474,4.564
XS Rating Curve= 0 ,0
Exp/Cntr=0.3,0.1

Type RM Length L Ch R = 1 ,80      ,26.77,26.77,26.77
XS GIS Cut Line= 6
      3497576.45      5379211.23      3497574.12      5379208.69
      3497571.84      5379206.83      3497570.74      5379205.66
      3497568.93      5379204.57      3497568.23      5379203.91
#Sta/Elev= 9
       0  374.54   3.447   374.1   6.389  372.57   6.807  372.25   7.133  372.15
   7.416  372.25   7.997   372.5   10.11  373.75  11.072   374.1
#Mann= 3 , 0 , 0
       0     .05       0   6.389     .04       0   7.997     .05       0
Bank Sta=6.389,7.997
XS Rating Curve= 0 ,0
Exp/Cntr=0.3,0.1

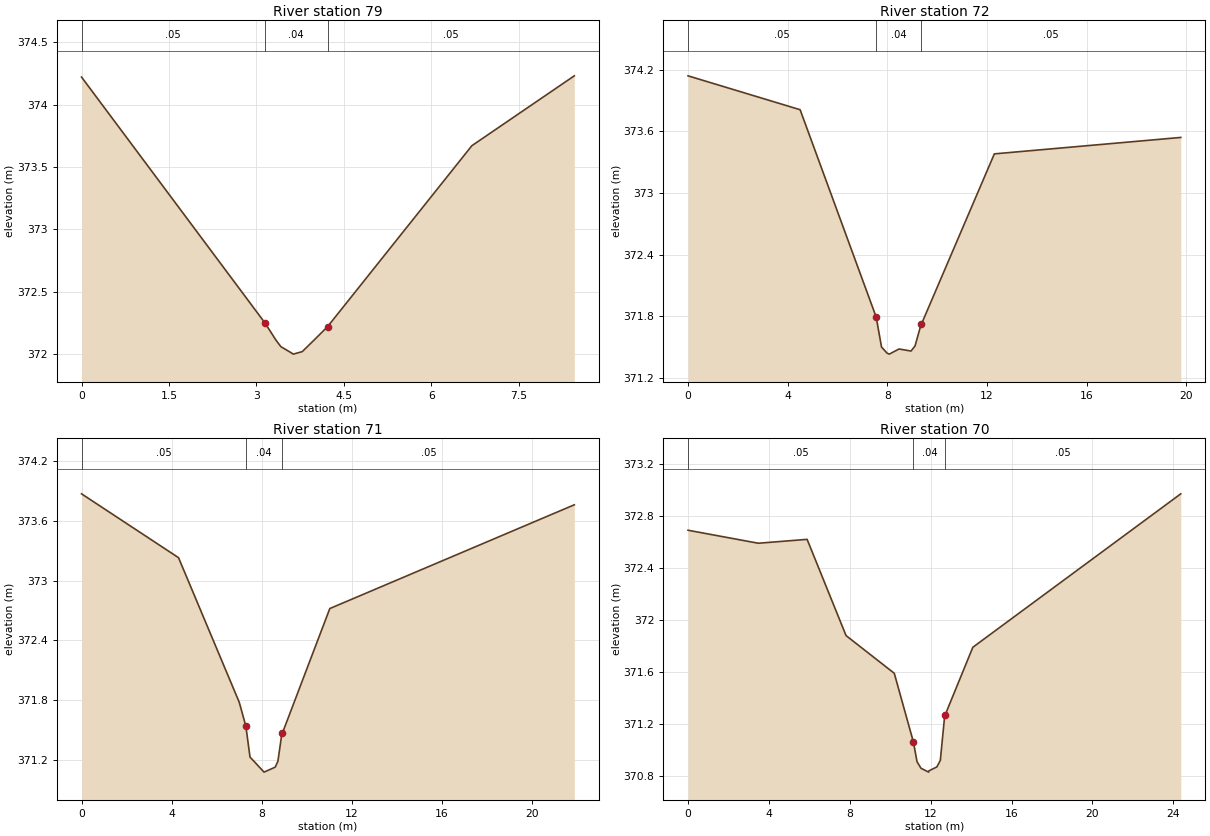
Type RM Length L Ch R = 1 ,79      ,54.26,54.26,54.26
XS GIS Cut Line= 6
       3497592.1      5379189.19      3497589.84        5379187.
      3497589.71      5379186.77      3497589.38      5379186.64
      3497587.28      5379184.65       3497585.9      5379183.56
#Sta/Elev= 11
       0  374.22   3.147  372.25   3.339  372.11    3.42  372.06     3.6  372.01
   3.632     372   3.787  372.02   3.984  372.11   4.221  372.22   6.697  373.67
   8.455  374.23
#Mann= 3 , 0 , 0
       0     .05       0   3.147     .04       0   4.221     .05       0
Bank Sta=3.147,4.221
XS Rating Curve= 0 ,0
Exp/Cntr=0.3,0.1

Type RM Length L Ch R = 1 ,72      ,93.73,93.73,93.73
XS GIS Cut Line= 6
      3497617.18       5379139.8      3497612.68      5379139.81
      3497609.21      5379140.03      3497608.09      5379139.93
      3497604.92      5379140.06      3497597.48      5379140.87
#Sta/Elev= 13
       0  374.14     4.5  373.81   7.555  371.79   7.767   371.5   7.989  371.44
   8.079  371.43   8.471  371.48   8.953  371.46   9.114  371.51   9.356  371.72
   9.366  371.72  12.297  373.38  19.781  373.54
#Mann= 3 , 0 , 0
       0     .05       0   7.555     .04       0   9.366     .05       0
Bank Sta=7.555,9.366
XS Rating Curve= 0 ,0
Exp/Cntr=0.3,0.1

Type RM Length L Ch R = 1 ,71      ,50.945,50.945,50.945
XS GIS Cut Line= 6
      3497587.79      5379048.55      3497584.14      5379050.84
      3497581.93      5379052.39      3497581.48      5379052.55
      3497580.25      5379053.23      3497569.42      5379060.39
#Sta/Elev= 13
       0  373.87   4.309  373.23   7.008  371.78   7.302  371.54   7.486  371.23
   7.657  371.19   8.109  371.08   8.606  371.13   8.726  371.19   8.903  371.47
   8.923  371.47  11.032  372.72  21.896  373.76
#Mann= 3 , 0 , 0
       0     .05       0   7.302     .04       0   8.923     .05       0
Bank Sta=7.302,8.923
XS Rating Curve= 0 ,0
Exp/Cntr=0.3,0.1

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
Type RM Length L Ch R = 1 ,70      ,83.285,83.285,83.285
XS GIS Cut Line= 6
      3497528.46      5378964.42        3497524.      5378968.26
      3497522.36      5378969.27      3497519.66      5378971.51
      3497517.38        5378973.      3497509.37      5378979.45
#Sta/Elev= 16
       0  372.69   3.478  372.59    5.89  372.62   7.816  371.88  10.201  371.59
   11.15  371.06  11.326  370.91  11.521  370.86  11.901  370.83  11.915  370.84
  12.306  370.87  12.478  370.92  12.698  371.27  12.718  371.27  14.086  371.79
   24.37  372.97
#Mann= 3 , 0 , 0
       0     .05       0   11.15     .04       0  12.718     .05       0
Bank Sta=11.15,12.718
XS Rating Curve= 0 ,0
Exp/Cntr=0.3,0.1

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