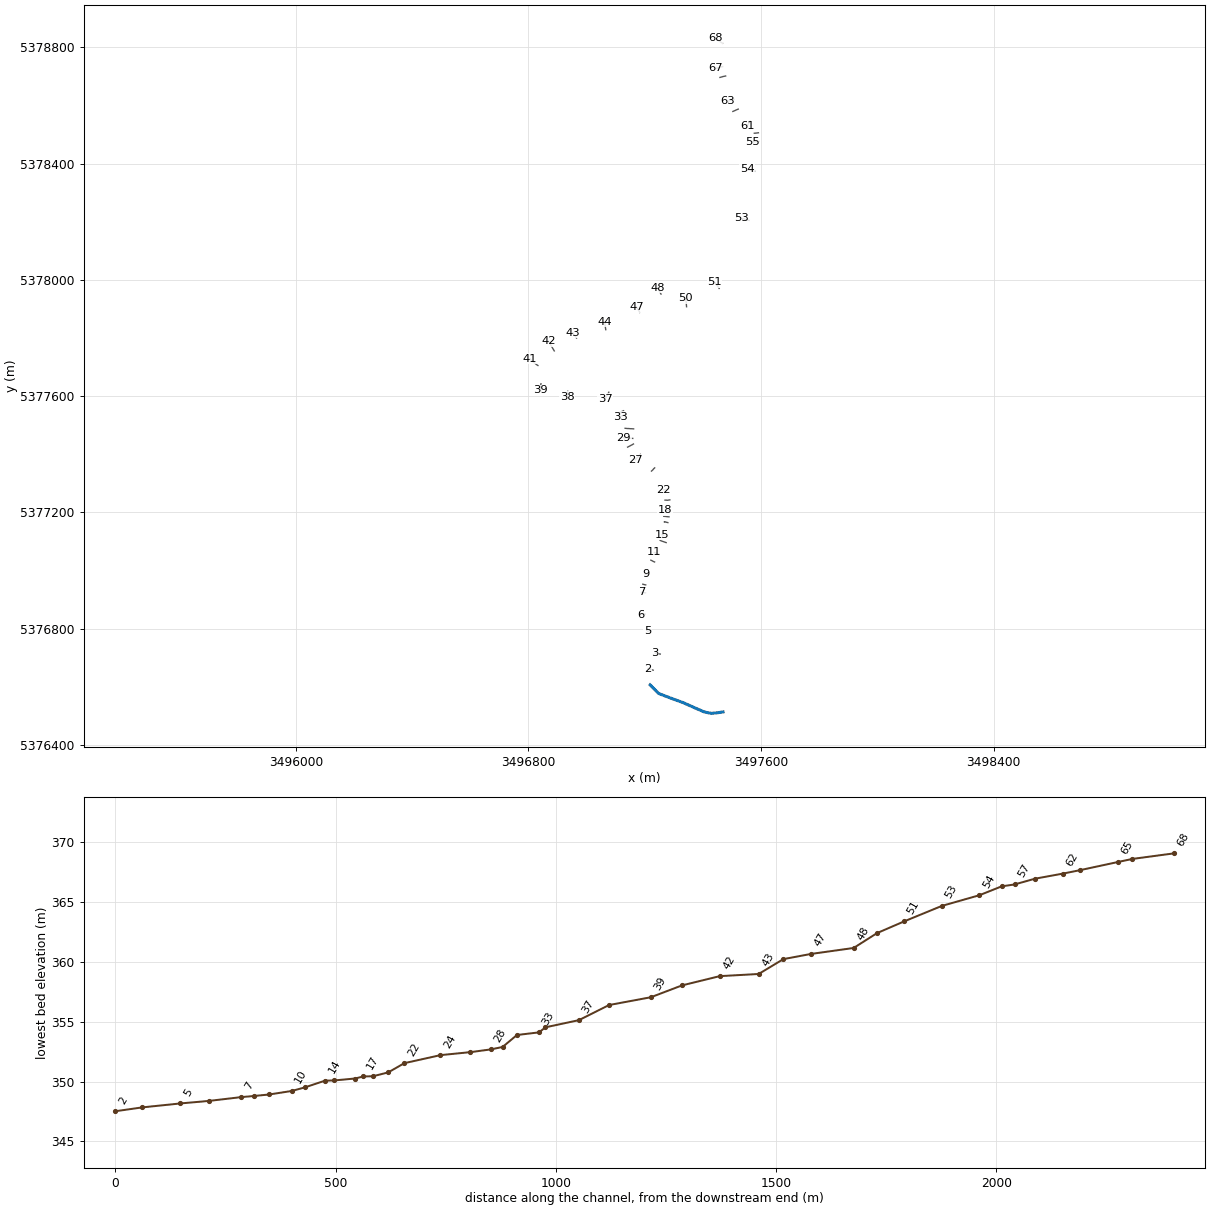
HEC-RAS study Amm_final.prj: Amm_final

--- Amm_final.g04 (geometry) --- (continued)

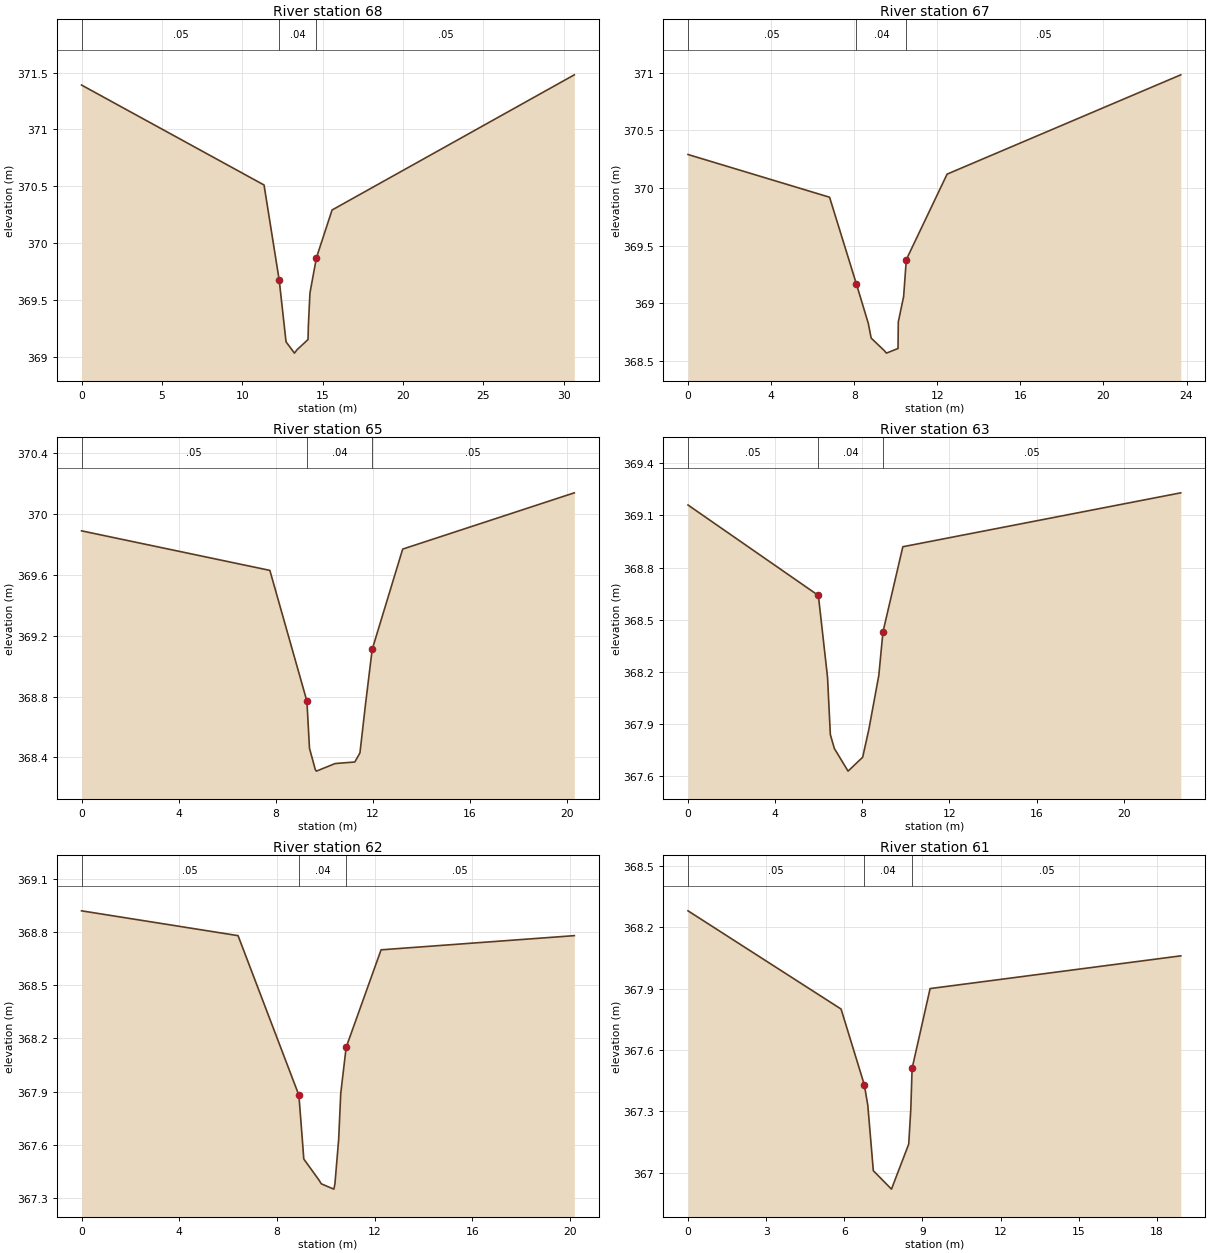
Type RM Length L Ch R = 1 ,68      ,93.61,93.61,93.61
XS GIS Cut Line= 6
      3497467.25      5378814.16       3497457.7      5378820.31
      3497455.53      5378821.76      3497455.34      5378822.21
      3497454.44      5378822.58      3497441.96      5378831.04
#Sta/Elev= 12
       0  371.39  11.359  370.51  12.305  369.67  12.727  369.13   13.25  369.03
  13.413  369.06  14.096  369.15  14.116  369.27  14.216  369.56  14.619  369.87
  15.592  370.29  30.669  371.48
#Mann= 3 , 0 , 0
       0     .05       0  12.305     .04       0  14.619     .05       0
Bank Sta=12.305,14.619
XS Rating Curve= 0 ,0
Exp/Cntr=0.3,0.1

Type RM Length L Ch R = 1 ,67      ,33.24,33.24,33.24
XS GIS Cut Line= 6
      3497467.77      5378733.77      3497459.23      5378731.63
        3497458.      5378731.24      3497457.79      5378731.07
      3497457.67      5378731.12      3497444.94      5378727.58
#Sta/Elev= 13
       0  370.29   6.815  369.92   8.104  369.17   8.676  368.83   8.818   368.7
    9.46  368.59   9.549  368.57   10.11  368.61  10.124  368.84   10.38  369.06
   10.51  369.38  12.473  370.12  23.723  370.98
#Mann= 3 , 0 , 0
       0     .05       0   8.104     .04       0   10.51     .05       0
Bank Sta=8.104,10.51
XS Rating Curve= 0 ,0
Exp/Cntr=0.3,0.1

Type RM Length L Ch R = 1 ,65      ,86,86,86
XS GIS Cut Line= 6
      3497478.04       5378701.5      3497470.45      5378699.86
      3497468.93      5378699.71      3497468.62       5378699.8
       3497466.8      5378698.86       3497458.5      5378696.55
#Sta/Elev= 13
       0  369.89   7.765  369.63   9.293  368.77   9.399  368.46   9.639  368.32
   9.684  368.31  10.458  368.36  11.268  368.37   11.48  368.43  11.702  368.74
  11.984  369.11  13.242  369.77  20.319  370.14
#Mann= 3 , 0 , 0
       0     .05       0   9.293     .04       0  11.984     .05       0
Bank Sta=9.293,11.984
XS Rating Curve= 0 ,0
Exp/Cntr=0.3,0.1

Type RM Length L Ch R = 1 ,63      ,37.94,37.94,37.94
XS GIS Cut Line= 6
      3497506.72      5378621.22      3497500.92      5378619.75
      3497498.25      5378619.16      3497498.24      5378618.97
      3497497.33       5378618.9      3497485.42      5378614.33
#Sta/Elev= 12
       0  369.16   5.983  368.64   6.403  368.17   6.533  367.84   6.717  367.76
   7.346  367.63   8.017  367.71     8.3  367.87   8.757  368.18   8.947  368.43
    9.86  368.92  22.617  369.23
#Mann= 3 , 0 , 0
       0     .05       0   5.983     .04       0   8.947     .05       0
Bank Sta=5.983,8.947
XS Rating Curve= 0 ,0
Exp/Cntr=0.3,0.1

Type RM Length L Ch R = 1 ,62      ,64.05,64.05,64.05
XS GIS Cut Line= 6
      3497521.38      5378587.52      3497515.43      5378585.14
      3497513.09      5378584.29      3497512.39      5378583.71
      3497511.52      5378583.19      3497502.93      5378579.52
#Sta/Elev= 14
       0  368.92   6.408  368.78   8.898  367.88   9.028  367.65   9.099  367.52
   9.727   367.4   9.816  367.38   10.33  367.35  10.374  367.38  10.527  367.63
  10.612  367.89  10.834  368.15  12.263   368.7  20.175  368.78
#Mann= 3 , 0 , 0
       0     .05       0   8.898     .04       0  10.834     .05       0
Bank Sta=8.898,10.834
XS Rating Curve= 0 ,0
Exp/Cntr=0.3,0.1

Type RM Length L Ch R = 1 ,61      ,46.46,46.46,46.46
XS GIS Cut Line= 6
      3497562.36      5378546.53       3497559.1      5378541.64
      3497558.44      5378541.04      3497558.35      5378540.71
      3497557.71      5378539.44      3497552.16      5378530.69
#Sta/Elev= 11
       0  368.28   5.877   367.8   6.769  367.43   6.903  367.33   7.115  367.01
   7.812  366.92   8.474  367.14   8.554  367.31   8.604  367.51   9.295   367.9
   18.92  368.06
#Mann= 3 , 0 , 0
       0     .05       0   6.769     .04       0   8.604     .05       0
Bank Sta=6.769,8.604
XS Rating Curve= 0 ,0
Exp/Cntr=0.3,0.1

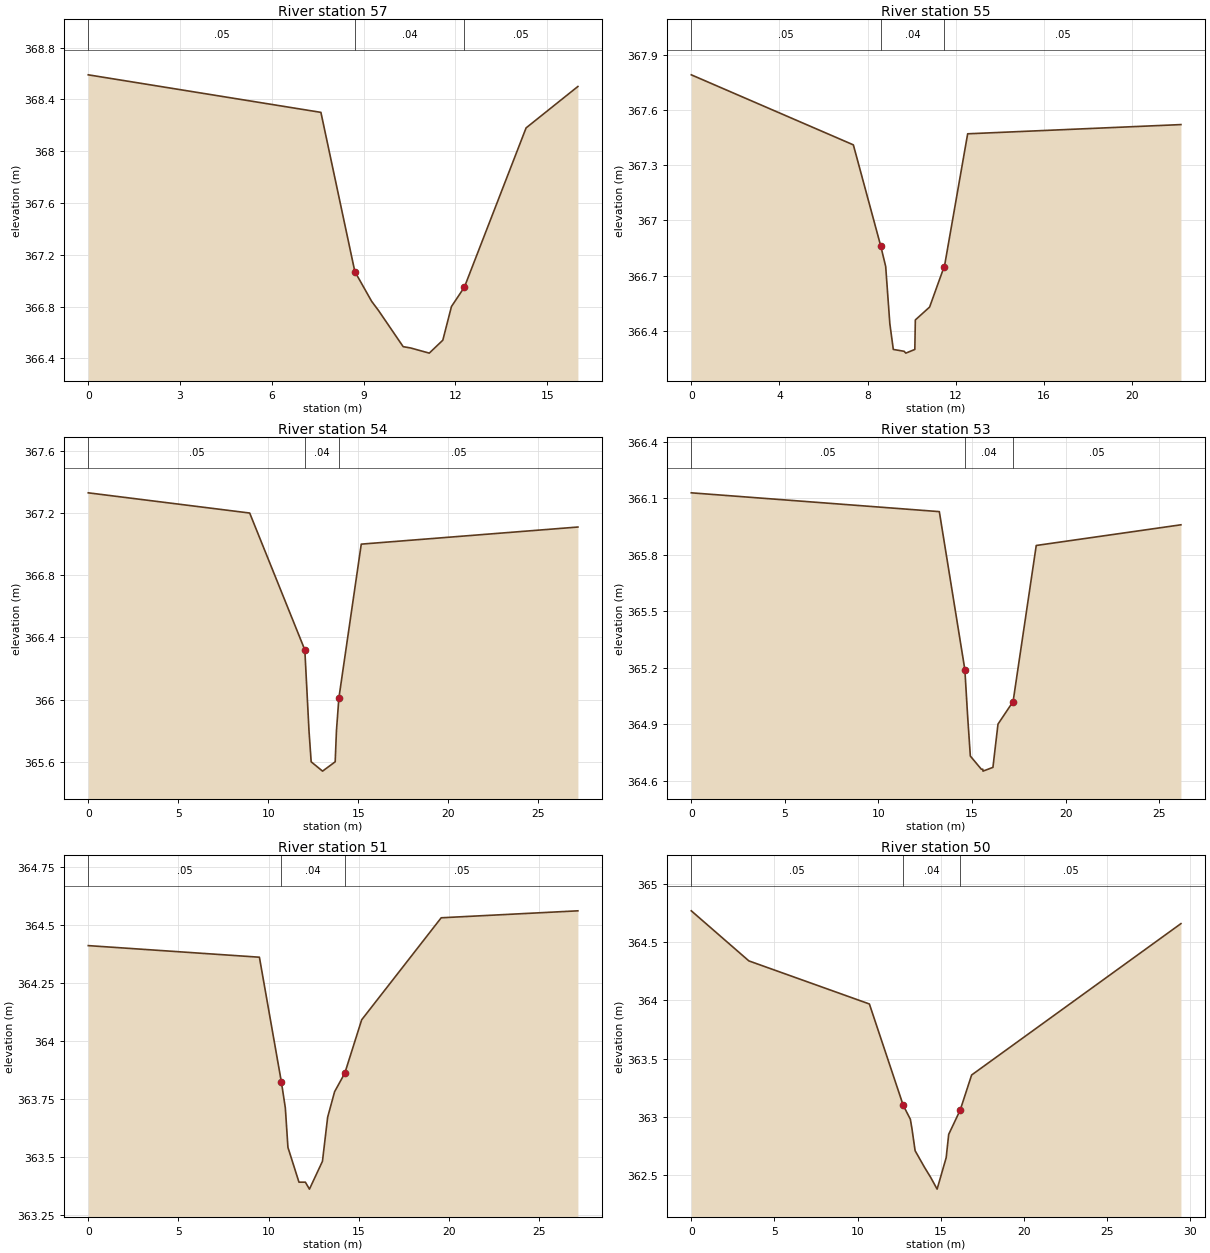
Type RM Length L Ch R = 1 ,57      ,29.37,29.37,29.37
XS GIS Cut Line= 6
      3497590.77       5378506.1      3497582.13      5378504.99
      3497581.37      5378505.05      3497579.29      5378504.77
      3497579.02      5378504.85       3497576.6      5378504.55
#Sta/Elev= 13
       0  368.59   7.602   368.3   8.711  367.07   9.261  366.84   9.482  366.77
   10.29  366.49  10.532  366.48  11.143  366.44  11.586  366.54  11.868   366.8
  12.291  366.95  14.307  368.18      16   368.5
#Mann= 3 , 0 , 0
       0     .05       0   8.711     .04       0  12.291     .05       0
Bank Sta=8.711,12.291
XS Rating Curve= 0 ,0
Exp/Cntr=0.3,0.1

Type RM Length L Ch R = 1 ,55      ,50.44,50.44,50.44
XS GIS Cut Line= 6
      3497592.81       5378476.5      3497585.46      5378476.15
      3497582.53      5378475.65      3497582.23      5378475.91
       3497580.6      5378475.39      3497570.96      5378474.48
#Sta/Elev= 15
       0  367.79   7.358  367.41   8.604  366.86   8.826  366.75   9.014  366.44
   9.172   366.3   9.663  366.29    9.74  366.28  10.149   366.3  10.172  366.46
   10.82  366.53  11.483  366.75  11.493  366.75  12.548  367.47  22.231  367.52
#Mann= 3 , 0 , 0
       0     .05       0   8.604     .04       0  11.493     .05       0
Bank Sta=8.604,11.493
XS Rating Curve= 0 ,0
Exp/Cntr=0.3,0.1

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
Type RM Length L Ch R = 1 ,54      ,85.195,85.195,85.195
XS GIS Cut Line= 6
      3497577.64      5378373.88      3497566.12       5378376.9
       3497566.1      5378376.78        3497566.      5378376.99
      3497563.19      5378377.25      3497551.48      5378380.05
#Sta/Elev= 11
       0  367.33   8.971   367.2  12.035  366.32  12.267   365.8  12.388   365.6
  13.021  365.54  13.723   365.6  13.793   365.8  13.928  366.01  15.172     367
  27.212  367.11
#Mann= 3 , 0 , 0
       0     .05       0  12.035     .04       0  13.928     .05       0
Bank Sta=12.035,13.928
XS Rating Curve= 0 ,0
Exp/Cntr=0.3,0.1

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
Type RM Length L Ch R = 1 ,53      ,85.523,85.523,85.523
XS GIS Cut Line= 6
       3497558.9      5378204.52      3497544.84       5378208.5
      3497544.85      5378208.65      3497543.34      5378209.03
       3497542.6      5378209.35      3497533.96      5378211.74
#Sta/Elev= 13
       0  366.13  13.251  366.03  14.615  365.19  14.765  364.94  14.908  364.73
  15.497  364.66  15.573  364.66  15.583  364.65  16.115  364.67  16.385   364.9
  17.192  365.02  18.429  365.85  26.159  365.96
#Mann= 3 , 0 , 0
       0     .05       0  14.615     .04       0  17.192     .05       0
Bank Sta=14.615,17.192
XS Rating Curve= 0 ,0
Exp/Cntr=0.3,0.1

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
Type RM Length L Ch R = 1 ,51      ,61.685,61.685,61.685
XS GIS Cut Line= 6
      3497455.77      5377970.68      3497449.57      5377979.85
      3497448.01      5377981.34      3497447.95      5377981.72
      3497444.51      5377986.52       3497439.8      5377992.46
#Sta/Elev= 15
       0  364.41   9.489  364.36  10.712  363.82  10.927  363.71  11.071  363.54
  11.683  363.39  12.037  363.39  12.264  363.36  12.985  363.48  13.273  363.67
  13.658  363.78  14.224  363.86  15.159  364.09  19.569  364.53  27.149  364.56
#Mann= 3 , 0 , 0
       0     .05       0  10.712     .04       0  14.224     .05       0
Bank Sta=10.712,14.224
XS Rating Curve= 0 ,0
Exp/Cntr=0.3,0.1

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
Type RM Length L Ch R = 1 ,50      ,53.075,53.075,53.075
XS GIS Cut Line= 6
      3497343.68       5377907.6      3497342.72      5377918.26
      3497342.86      5377920.81      3497342.73      5377920.95
      3497342.44      5377923.64      3497340.56      5377936.77
#Sta/Elev= 15
       0  364.77    3.46  364.34  10.704  363.97  12.737   363.1  13.167  362.98
  13.262   362.9  13.453  362.71  14.006  362.57  14.392  362.48  14.775  362.38
   15.32  362.65  15.471  362.85  16.165  363.06  16.849  363.36   29.43  364.66
#Mann= 3 , 0 , 0
       0     .05       0  12.737     .04       0  16.165     .05       0
Bank Sta=12.737,16.165
XS Rating Curve= 0 ,0
Exp/Cntr=0.3,0.1

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
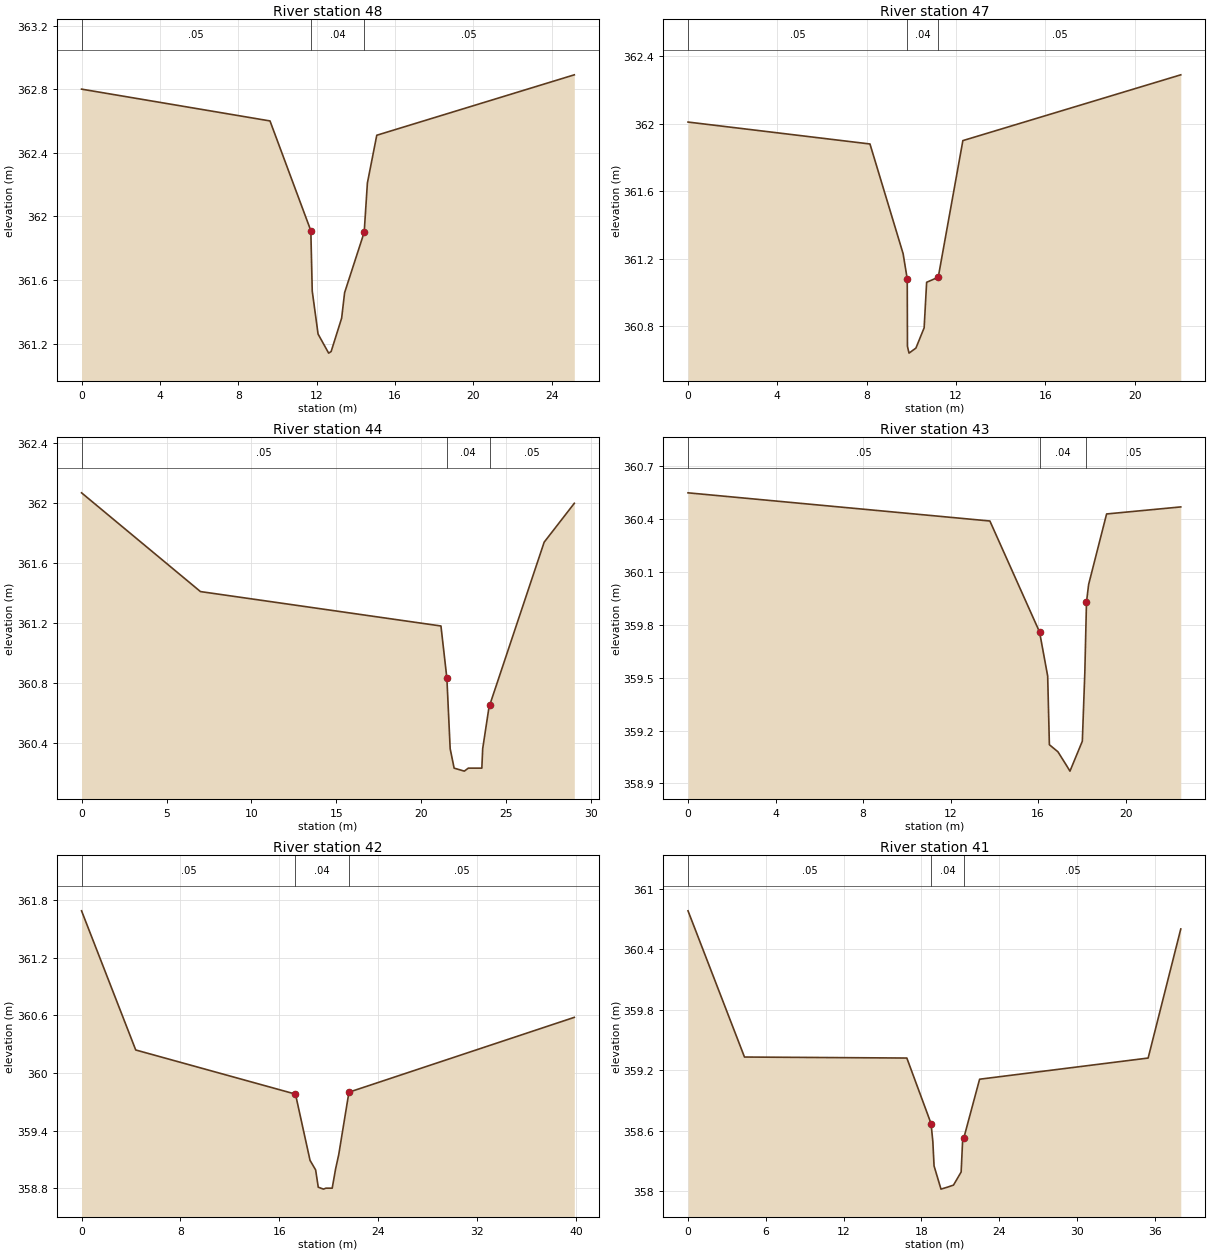
Type RM Length L Ch R = 1 ,48      ,97.3,97.3,97.3
XS GIS Cut Line= 6
       3497255.9      5377951.18      3497249.95      5377961.31
      3497249.78      5377962.13      3497249.46      5377962.73
      3497248.53      5377964.07      3497243.45      5377972.78
#Sta/Elev= 14
       0   362.8    9.62   362.6  11.704  361.91  11.744   361.7  11.776  361.53
  12.074  361.26  12.614  361.14   12.74  361.15  13.277  361.36  13.428  361.52
  14.428   361.9  14.592  362.21   15.07  362.51  25.154  362.89
#Mann= 3 , 0 , 0
       0     .05       0  11.704     .04       0  14.428     .05       0
Bank Sta=11.704,14.428
XS Rating Curve= 0 ,0
Exp/Cntr=0.3,0.1

Type RM Length L Ch R = 1 ,47      ,62.21,62.21,62.21
XS GIS Cut Line= 6
      3497182.71      5377887.95      3497178.95      5377895.18
      3497178.05      5377896.36      3497177.41      5377897.69
      3497176.64      5377898.48      3497171.49      5377906.77
#Sta/Elev= 12
       0  362.01   8.149  361.88   9.633  361.23   9.818  361.08   9.828  360.68
   9.898  360.64  10.207  360.67  10.575  360.79  10.687  361.06  11.207  361.09
   12.31   361.9  22.069  362.29
#Mann= 3 , 0 , 0
       0     .05       0   9.818     .04       0  11.207     .05       0
Bank Sta=9.818,11.207
XS Rating Curve= 0 ,0
Exp/Cntr=0.3,0.1

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
Type RM Length L Ch R = 1 ,44      ,56.08,56.08,56.08
XS GIS Cut Line= 6
      3497065.88       5377828.7      3497064.71       5377835.6
      3497062.62      5377850.38      3497062.61      5377850.98
      3497062.46      5377851.16      3497061.66      5377855.53
#Sta/Elev= 14
       0  362.07   6.998  361.41  21.152  361.18  21.501  360.83  21.694  360.36
  21.927  360.23  22.527  360.21  22.762  360.23  23.558  360.23  23.608  360.36
  23.996  360.65  24.018  360.65  27.225  361.74      29     362
#Mann= 3 , 0 , 0
       0     .05       0  21.501     .04       0  24.018     .05       0
Bank Sta=21.501,24.018
XS Rating Curve= 0 ,0
Exp/Cntr=0.3,0.1

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
Type RM Length L Ch R = 1 ,43      ,88.33,88.33,88.33
XS GIS Cut Line= 6
      3496965.19       5377799.9       3496957.8      5377811.55
       3496956.2      5377813.16       3496955.5      5377814.11
      3496955.32      5377814.19      3496952.58      5377818.41
#Sta/Elev= 14
       0  360.55  13.796  360.39  16.066  359.76  16.437  359.51  16.515  359.12
  16.904  359.08  17.259  359.01  17.456  358.97  18.021  359.14  18.135  359.53
  18.211  359.93  18.309  360.03   19.13  360.43   22.52  360.47
#Mann= 3 , 0 , 0
       0     .05       0  16.066     .04       0  18.211     .05       0
Bank Sta=16.066,18.211
XS Rating Curve= 0 ,0
Exp/Cntr=0.3,0.1

Type RM Length L Ch R = 1 ,42      ,85.57,85.57,85.57
XS GIS Cut Line= 6
      3496888.78      5377755.68      3496879.86       5377770.5
       3496879.1       5377771.4      3496878.79      5377772.44
      3496870.15      5377787.34      3496868.42      5377789.75
#Sta/Elev= 13
       0  361.69   4.381  360.24  17.298  359.78  18.476  359.09  18.929  358.99
  19.141  358.81  19.567  358.79  19.757   358.8  20.269   358.8  20.542     359
  20.797  359.15  21.622   359.8  39.846  360.58
#Mann= 3 , 0 , 0
       0     .05       0  17.298     .04       0  21.622     .05       0
Bank Sta=17.298,21.622
XS Rating Curve= 0 ,0
Exp/Cntr=0.3,0.1

Type RM Length L Ch R = 1 ,41      ,70.76,70.76,70.76
XS GIS Cut Line= 6
      3496832.53      5377705.52      3496828.87      5377707.88
      3496818.99      5377715.57      3496817.71      5377716.93
      3496814.75      5377719.21      3496805.53      5377728.37
#Sta/Elev= 15
       0  360.78   4.355  359.33  16.875  359.32  18.743  358.67  18.881  358.49
  18.974  358.25  19.508  358.02  20.018  358.04  20.473  358.06  21.063  358.19
  21.172  358.49  21.274  358.53  22.486  359.11  35.483  359.32      38   360.6
#Mann= 3 , 0 , 0
       0     .05       0  18.743     .04       0  21.274     .05       0
Bank Sta=18.743,21.274
XS Rating Curve= 0 ,0
Exp/Cntr=0.3,0.1

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
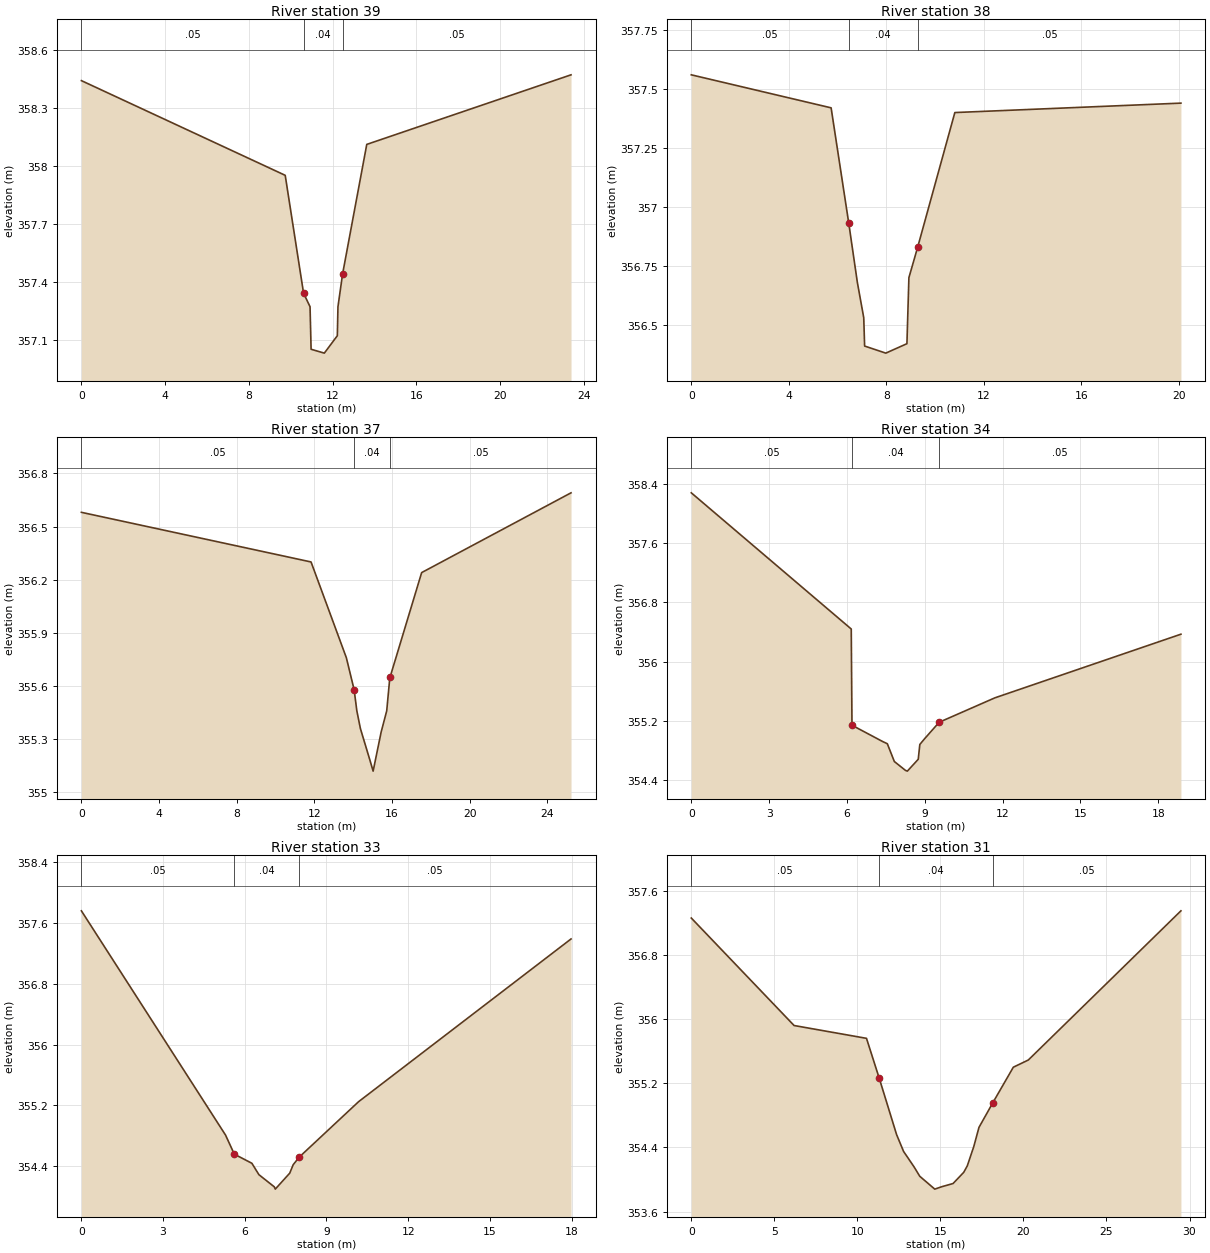
Type RM Length L Ch R = 1 ,39      ,94.94,94.94,94.94
XS GIS Cut Line= 6
      3496843.07      5377642.77      3496841.15      5377632.34
      3496841.73      5377631.54      3496841.76      5377630.92
      3496841.25      5377629.62      3496841.56      5377619.87
#Sta/Elev= 11
       0  358.44   9.734  357.95  10.611  357.34   10.92  357.27   10.97  357.05
  11.602  357.03  12.223  357.12  12.253  357.27  12.475  357.44  13.629  358.11
  23.384  358.47
#Mann= 3 , 0 , 0
       0     .05       0  10.611     .04       0  12.475     .05       0
Bank Sta=10.611,12.475
XS Rating Curve= 0 ,0
Exp/Cntr=0.3,0.1

Type RM Length L Ch R = 1 ,38      ,68.445,68.445,68.445
XS GIS Cut Line= 6
      3496934.97       5377616.8      3496934.34      5377610.02
      3496934.16      5377609.83       3496933.8      5377607.77
      3496933.72      5377606.25      3496932.35      5377597.08
#Sta/Elev= 12
       0  357.56   5.734  357.42   6.459  356.93    6.81  356.68   7.072  356.53
   7.108  356.41   7.976  356.38   8.843  356.42   8.924   356.7   9.286  356.83
  10.808   357.4   20.08  357.44
#Mann= 3 , 0 , 0
       0     .05       0   6.459     .04       0   9.286     .05       0
Bank Sta=6.459,9.286
XS Rating Curve= 0 ,0
Exp/Cntr=0.3,0.1

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
Type RM Length L Ch R = 1 ,37      ,76.13,76.13,76.13
XS GIS Cut Line= 6
      3497076.44      5377613.63      3497070.69      5377603.29
      3497069.96      5377601.23       3497069.2      5377600.69
      3497068.21      5377598.45      3497064.27      5377591.84
#Sta/Elev= 14
       0  356.58  11.831   356.3  13.649  355.76  14.049  355.58   14.19  355.46
  14.374  355.36  14.869  355.18  15.029  355.12  15.441  355.34  15.729  355.46
  15.891  355.65  15.901  355.65  17.529  356.24  25.224  356.69
#Mann= 3 , 0 , 0
       0     .05       0  14.049     .04       0  15.901     .05       0
Bank Sta=14.049,15.901
XS Rating Curve= 0 ,0
Exp/Cntr=0.3,0.1

Type RM Length L Ch R = 1 ,34      ,14.4,14.4,14.4
XS GIS Cut Line= 6
      3497127.11      5377549.81       3497120.3      5377546.98
      3497119.86      5377546.93       3497119.5      5377546.66
      3497116.45      5377545.29      3497110.06      5377542.03
#Sta/Elev= 14
       0  358.28   6.167  356.44   6.195  355.14   7.377  354.92   7.558  354.89
   7.828  354.65   8.257  354.53    8.33  354.52    8.75  354.68   8.811  354.88
   9.001  354.96   9.556  355.18  11.704  355.51  18.878  356.37
#Mann= 3 , 0 , 0
       0     .05       0   6.195     .04       0   9.556     .05       0
Bank Sta=6.195,9.556
XS Rating Curve= 0 ,0
Exp/Cntr=0.3,0.1

Type RM Length L Ch R = 1 ,33      ,50.15,50.15,50.15
XS GIS Cut Line= 6
      3497132.35      5377536.76      3497126.45      5377534.67
       3497126.3      5377534.46      3497125.39       5377533.6
      3497123.13      5377532.78      3497115.88       5377529.9
#Sta/Elev= 12
       0  357.76   5.295  354.81   5.615  354.56   6.261  354.44   6.519  354.29
   7.084  354.13    7.12   354.1   7.651  354.31   7.776  354.42   7.997  354.52
   10.18  355.25  17.981  357.39
#Mann= 3 , 0 , 0
       0     .05       0   5.615     .04       0   7.997     .05       0
Bank Sta=5.615,7.997
XS Rating Curve= 0 ,0
Exp/Cntr=0.3,0.1

Type RM Length L Ch R = 1 ,31      ,32.68,32.68,32.68
XS GIS Cut Line= 6
      3497161.63      5377487.49      3497155.46      5377487.97
       3497151.1        5377488.      3497143.56      5377488.72
      3497141.44      5377488.53       3497132.3      5377489.48
#Sta/Elev= 19
       0  357.26   6.189  355.92  10.549  355.76   11.32  355.26  12.361  354.56
  12.782  354.35  13.405  354.16  13.758  354.04   14.66  353.88  15.082  353.91
  15.763  353.95  16.406  354.09  16.618  354.17  17.008  354.41  17.322  354.65
  18.164  354.96   19.39   355.4  20.293  355.49  29.482  357.35
#Mann= 3 , 0 , 0
       0     .05       0   11.32     .04       0  18.164     .05       0
Bank Sta=11.32,18.164
XS Rating Curve= 0 ,0
Exp/Cntr=0.3,0.1

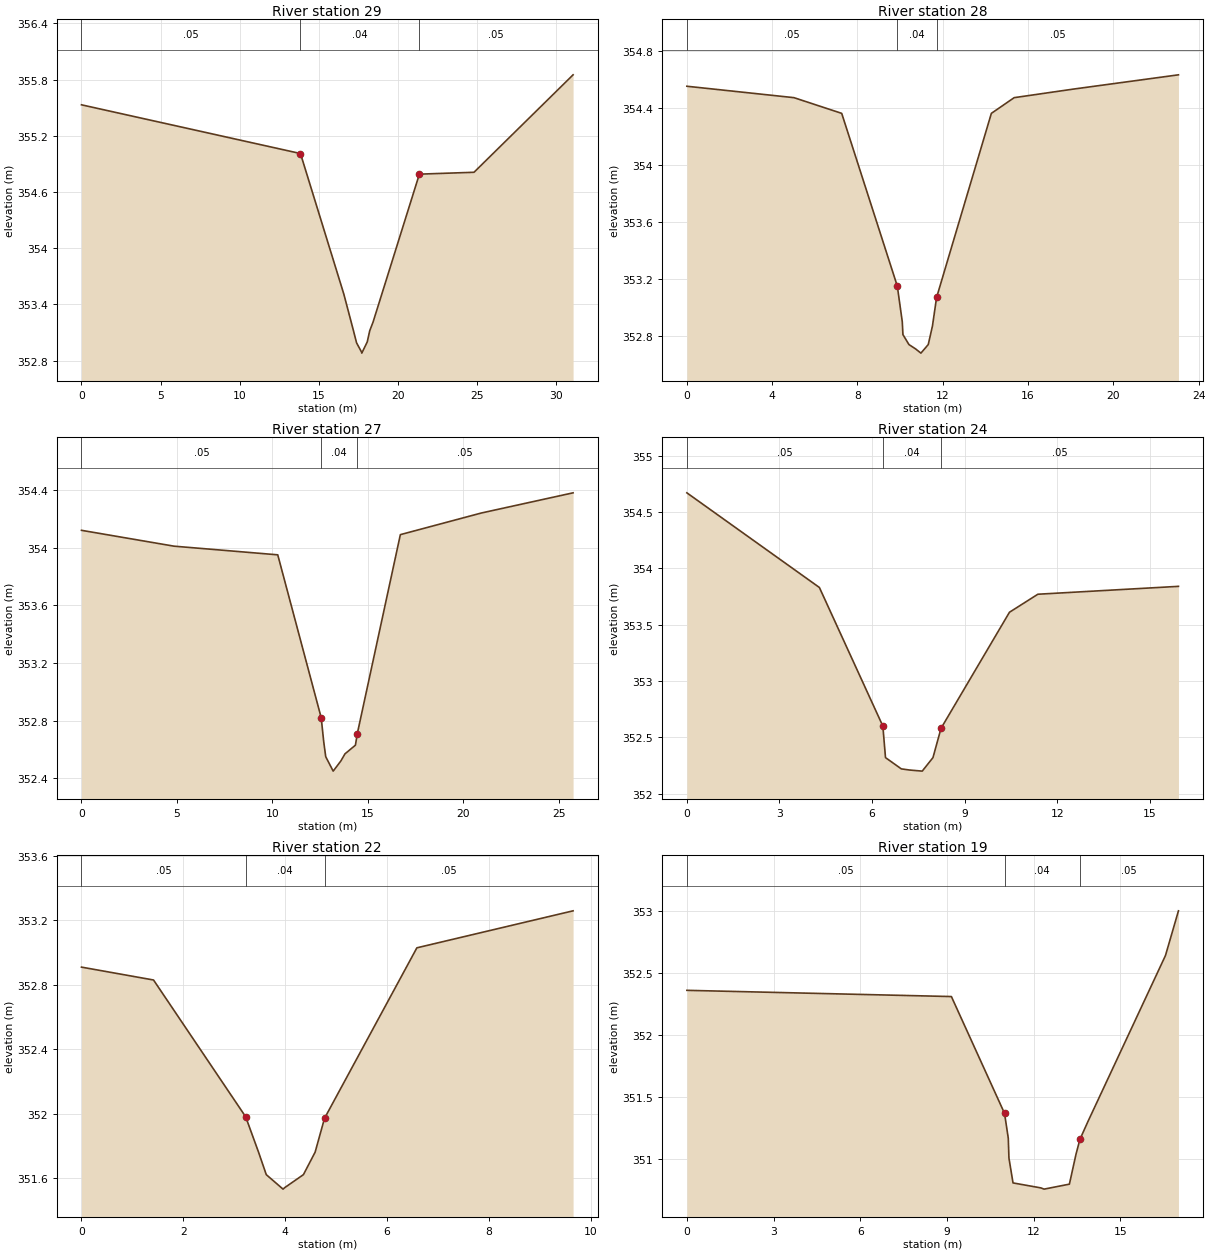
Type RM Length L Ch R = 1 ,29      ,26.42,26.42,26.42
XS GIS Cut Line= 6
      3497158.61      5377454.66      3497144.83      5377455.91
      3497142.15      5377456.48      3497141.07      5377456.27
      3497137.49      5377456.65      3497127.78      5377456.93
#Sta/Elev= 13
       0  355.53  13.839  355.01  16.579  353.51  17.172  353.13  17.384  352.99
  17.704  352.89  17.714  352.88   18.06     353  18.218  353.12  18.424  353.21
  21.354  354.79  24.806  354.81  31.068  355.85
#Mann= 3 , 0 , 0
       0     .05       0  13.839     .04       0  21.354     .05       0
Bank Sta=13.839,21.354
XS Rating Curve= 0 ,0
Exp/Cntr=0.3,0.1

Type RM Length L Ch R = 1 ,28      ,46.49,46.49,46.49
XS GIS Cut Line= 6
      3497161.09      5377435.55      3497154.85      5377431.84
      3497152.23      5377430.74      3497148.72      5377428.53
      3497147.69      5377428.24      3497140.89      5377424.62
#Sta/Elev= 16
       0  354.55   5.023  354.47   7.262  354.36   9.869  353.15  10.103   352.9
  10.133  352.81  10.416  352.74  10.723  352.71  10.977  352.68  11.321  352.74
  11.518  352.87  11.712  353.07  14.281  354.36  15.351  354.47  18.127  354.53
  23.056  354.63
#Mann= 3 , 0 , 0
       0     .05       0   9.869     .04       0  11.712     .05       0
Bank Sta=9.869,11.712
XS Rating Curve= 0 ,0
Exp/Cntr=0.3,0.1

Type RM Length L Ch R = 1 ,27      ,68.08,68.08,68.08
XS GIS Cut Line= 6
      3497184.98      5377399.96      3497176.16      5377390.83
      3497175.76      5377390.56      3497175.05      5377389.64
      3497170.54      5377384.84      3497167.15      5377381.43
#Sta/Elev= 14
       0  354.12   4.851  354.01  10.283  353.95   12.56  352.82  12.695  352.65
  12.797  352.55  13.187  352.45  13.587  352.52  13.807  352.57  14.353  352.63
  14.451  352.71  16.707  354.09  20.948  354.24  25.757  354.38
#Mann= 3 , 0 , 0
       0     .05       0   12.56     .04       0  14.451     .05       0
Bank Sta=12.56,14.451
XS Rating Curve= 0 ,0
Exp/Cntr=0.3,0.1

Type RM Length L Ch R = 1 ,24      ,81.92,81.92,81.92
XS GIS Cut Line= 6
      3497234.03      5377353.33      3497231.38      5377350.74
      3497230.87      5377350.74      3497228.53      5377347.58
      3497227.12      5377345.87      3497223.03      5377342.23
#Sta/Elev= 13
       0  354.67   4.293  353.83   6.349   352.6   6.435  352.32   6.947  352.22
   7.205  352.21   7.625   352.2   7.973  352.32   7.983  352.33   8.234  352.58
  10.451  353.61  11.371  353.77  15.926  353.84
#Mann= 3 , 0 , 0
       0     .05       0   6.349     .04       0   8.234     .05       0
Bank Sta=6.349,8.234
XS Rating Curve= 0 ,0
Exp/Cntr=0.3,0.1

Type RM Length L Ch R = 1 ,22      ,36.72,36.72,36.72
XS GIS Cut Line= 6
        3497274.      5377279.32      3497270.55        5377279.
      3497269.72      5377278.75       3497269.4      5377278.49
      3497267.63       5377278.1       3497264.6      5377277.63
#Sta/Elev= 12
       0  352.91   1.414  352.83   3.222  351.98   3.475  351.76   3.627  351.62
   3.956  351.53   3.992  351.54   4.356  351.62   4.586  351.76    4.77  351.97
   6.583  353.03   9.649  353.26
#Mann= 3 , 0 , 0
       0     .05       0   3.222     .04       0    4.77     .05       0
Bank Sta=3.222,4.77
XS Rating Curve= 0 ,0
Exp/Cntr=0.3,0.1

Type RM Length L Ch R = 1 ,19      ,34.34,34.34,34.34
XS GIS Cut Line= 6
      3497286.23      5377243.27       3497277.2      5377241.76
      3497275.29      5377242.23      3497274.08      5377242.21
      3497272.99      5377242.37      3497269.45       5377242.3
#Sta/Elev= 14
       0  352.36   9.155  352.31  10.994  351.37  11.124  351.17  11.147  351.01
  11.288  350.81  12.249  350.77  12.363  350.76  13.239   350.8  13.467  351.04
  13.603  351.16  13.873   351.3  16.564  352.64  17.014     353
#Mann= 3 , 0 , 0
       0     .05       0  10.994     .04       0  13.603     .05       0
Bank Sta=10.994,13.603
XS Rating Curve= 0 ,0
Exp/Cntr=0.3,0.1

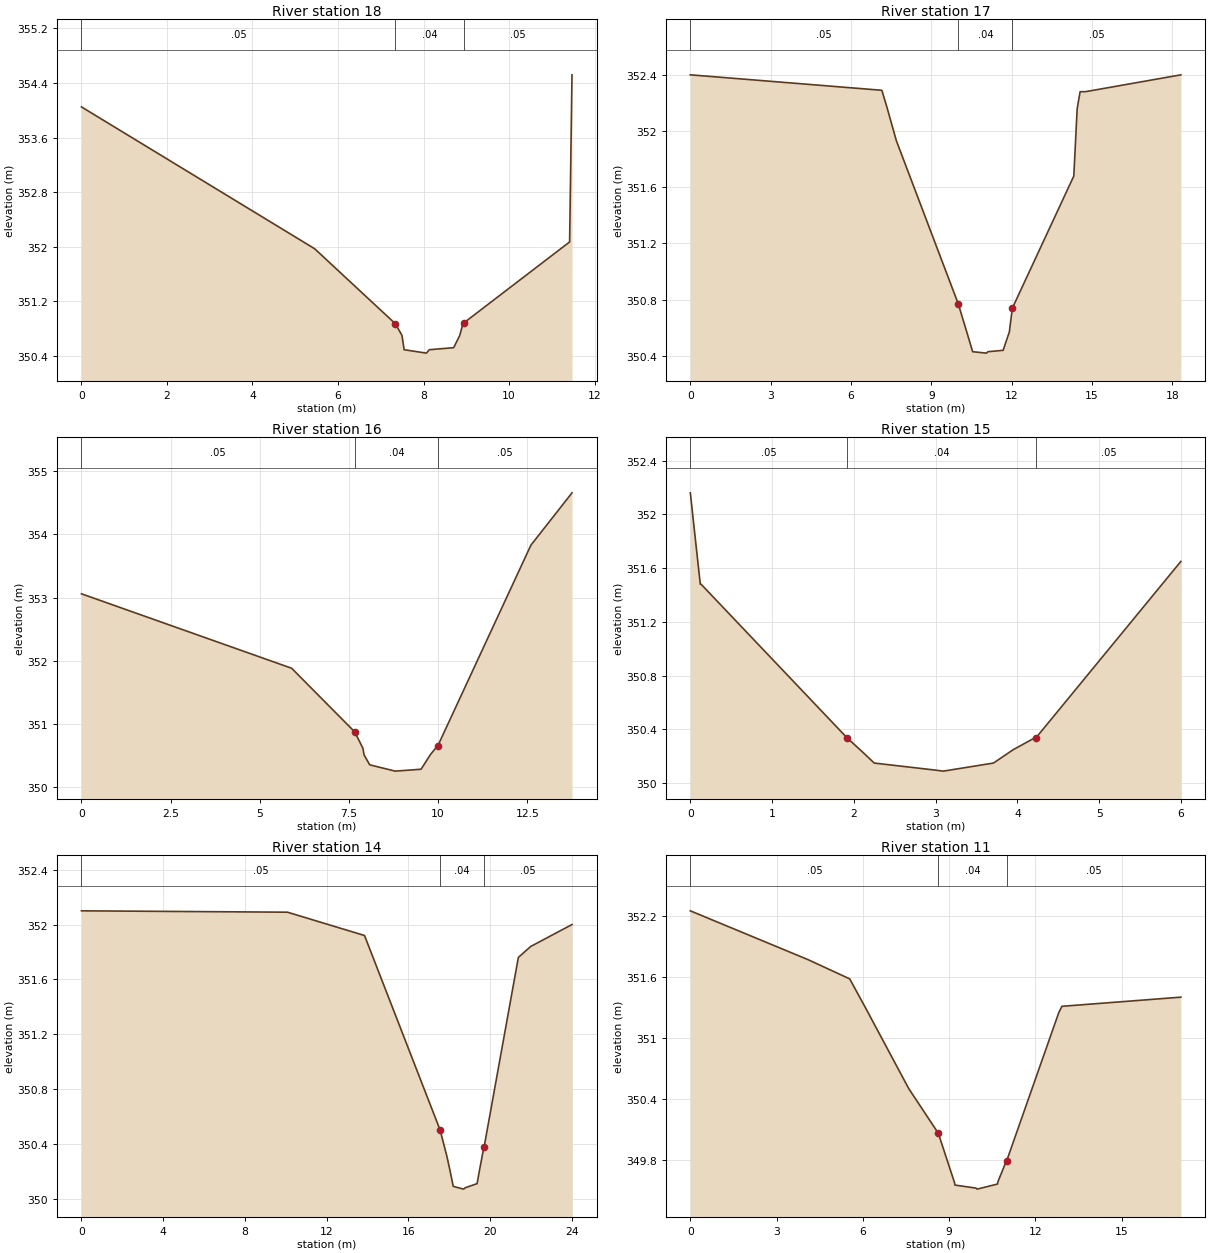
Type RM Length L Ch R = 1 ,18      ,21.95,21.95,21.95
XS GIS Cut Line= 6
      3497281.16      5377206.42      3497275.88      5377207.79
      3497272.65      5377208.04      3497272.54      5377207.95
      3497272.49      5377208.02      3497269.97      5377207.97
#Sta/Elev= 13
       0  354.05   5.455  351.97   7.343  350.87   7.496   350.7   7.547  350.49
   8.068  350.44   8.135  350.49   8.706  350.52   8.848   350.7   8.926  350.88
   8.936  350.88  11.417  352.07  11.473  354.52
#Mann= 3 , 0 , 0
       0     .05       0   7.343     .04       0   8.936     .05       0
Bank Sta=7.343,8.936
XS Rating Curve= 0 ,0
Exp/Cntr=0.3,0.1

Type RM Length L Ch R = 1 ,17      ,19.11,19.11,19.11
XS GIS Cut Line= 6
      3497283.27       5377184.9      3497275.63      5377185.54
      3497271.36      5377186.24      3497269.07      5377186.39
      3497268.87      5377186.28      3497265.32      5377186.62
#Sta/Elev= 17
       0   352.4   7.155  352.29   7.344  352.17   7.699  351.93   10.01  350.77
  10.343  350.56  10.547  350.43  11.067  350.42  11.117  350.43  11.685  350.44
  11.916  350.57   12.03  350.74  14.325  351.68  14.451  352.16  14.561  352.28
  14.759  352.28  18.325   352.4
#Mann= 3 , 0 , 0
       0     .05       0   10.01     .04       0   12.03     .05       0
Bank Sta=10.01,12.03
XS Rating Curve= 0 ,0
Exp/Cntr=0.3,0.1

Type RM Length L Ch R = 1 ,16      ,47.04,47.04,47.04
XS GIS Cut Line= 6
       3497279.4      5377165.01      3497273.68      5377166.43
      3497272.04       5377167.1      3497269.97      5377167.16
      3497267.32      5377166.34      3497267.41      5377167.49
#Sta/Elev= 13
       0  353.06   5.894  351.88   7.665  350.87   7.893  350.61   7.922  350.51
   8.082  350.35   8.797  350.25   9.522  350.28   9.782  350.51   9.981  350.65
   9.991  350.65  12.601  353.83  13.754  354.66
#Mann= 3 , 0 , 0
       0     .05       0   7.665     .04       0   9.991     .05       0
Bank Sta=7.665,9.991
XS Rating Curve= 0 ,0
Exp/Cntr=0.3,0.1

Type RM Length L Ch R = 1 ,15      ,20.97,20.97,20.97
XS GIS Cut Line= 6
      3497265.05       5377122.1      3497264.98        5377122.
       3497263.2      5377122.08      3497261.31      5377122.68
       3497261.1      5377122.86      3497259.34      5377123.04
#Sta/Elev= 13
       0  352.16    .122  351.48    .132  351.48   1.913  350.34    2.11  350.23
   2.249  350.15   2.962   350.1   3.094  350.09   3.707  350.15    3.95  350.25
    4.22  350.34    4.23  350.34   5.999  351.65
#Mann= 3 , 0 , 0
       0     .05       0   1.913     .04       0    4.23     .05       0
Bank Sta=1.913,4.23
XS Rating Curve= 0 ,0
Exp/Cntr=0.3,0.1

Type RM Length L Ch R = 1 ,14      ,45.78,45.78,45.78
XS GIS Cut Line= 6
      3497273.51      5377096.19      3497260.44      5377100.77
      3497256.91      5377101.88      3497256.65      5377102.08
      3497255.24      5377102.84      3497252.94      5377103.77
#Sta/Elev= 16
       0   352.1  10.079  352.09  13.849  351.92   17.55   350.5  17.878  350.31
  18.025  350.21   18.19  350.09  18.701  350.07  18.774  350.08  19.356  350.11
   19.49  350.22  19.693  350.38  19.703  350.38  21.375  351.76  21.979  351.84
      24     352
#Mann= 3 , 0 , 0
       0     .05       0   17.55     .04       0  19.703     .05       0
Bank Sta=17.55,19.703
XS Rating Curve= 0 ,0
Exp/Cntr=0.3,0.1

Type RM Length L Ch R = 1 ,11      ,29.88,29.88,29.88
XS GIS Cut Line= 6
      3497248.53      5377055.93      3497243.38      5377057.97
      3497241.61      5377059.01      3497238.77      5377060.16
      3497236.67      5377060.75      3497232.88      5377062.41
#Sta/Elev= 17
       0  352.25    4.09  351.77   5.545  351.58   6.123  351.28   7.598   350.5
   8.627  350.06   9.195  349.57   9.205  349.55   9.939  349.52   9.975  349.51
  10.687  349.56  10.697  349.58  10.997  349.79  11.007  349.79   12.82  351.25
  12.928  351.31  17.065   351.4
#Mann= 3 , 0 , 0
       0     .05       0   8.627     .04       0  11.007     .05       0
Bank Sta=8.627,11.007
XS Rating Curve= 0 ,0
Exp/Cntr=0.3,0.1

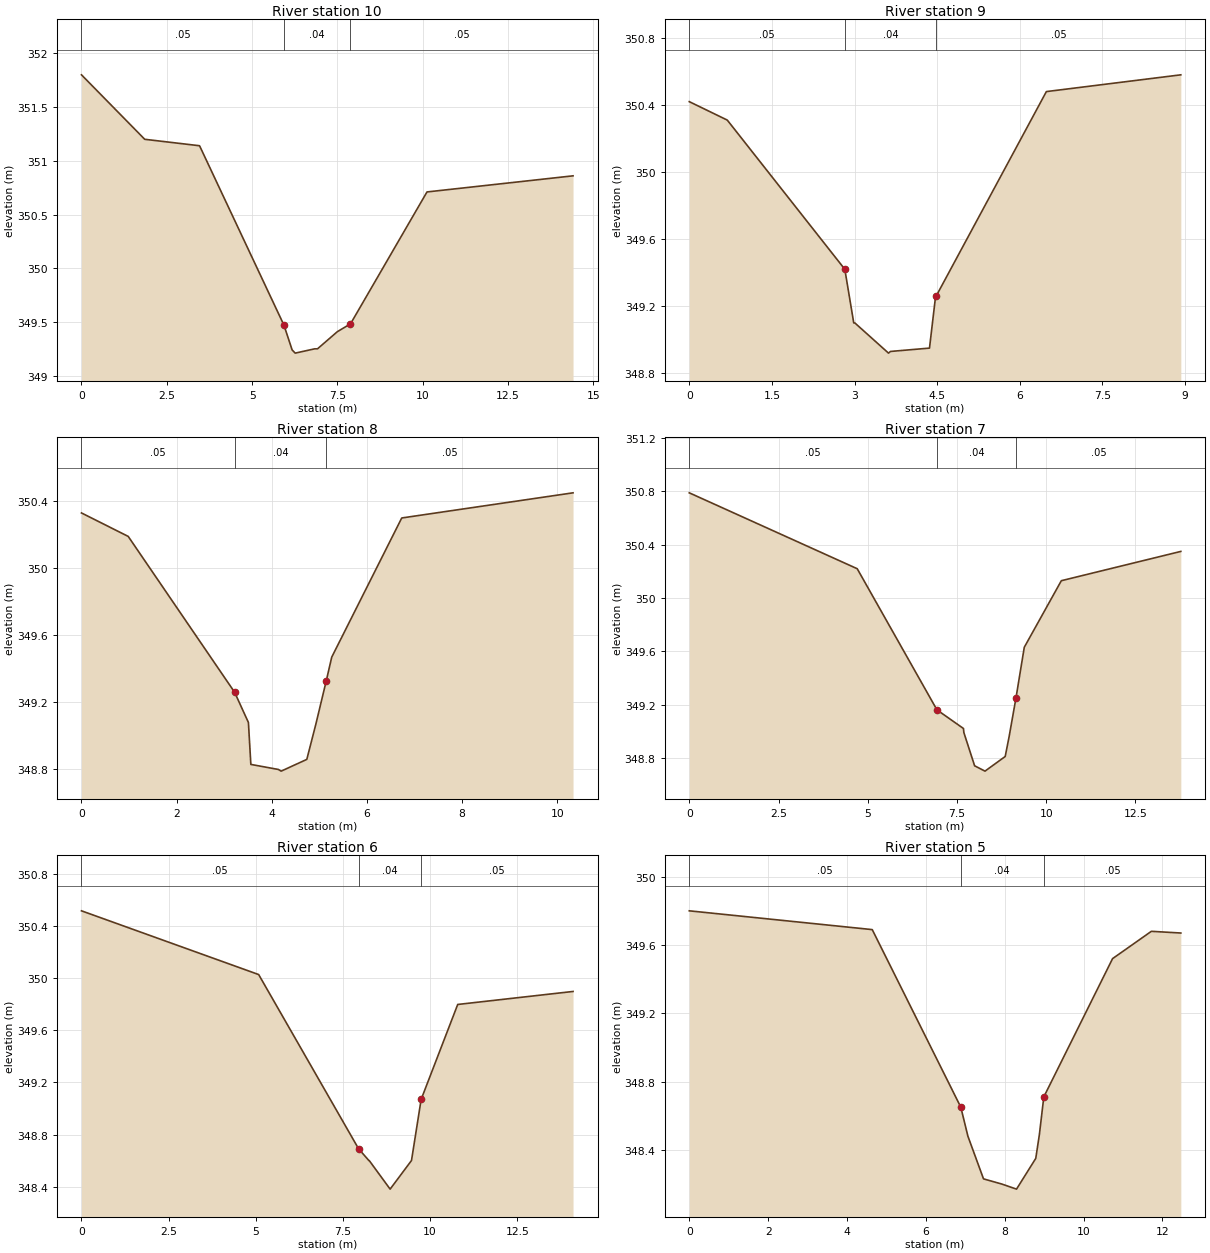
Type RM Length L Ch R = 1 ,10      ,50.67,50.67,50.67
XS GIS Cut Line= 6
      3497233.72      5377029.54      3497232.03       5377030.3
      3497230.49      5377030.76      3497228.29      5377031.89
      3497227.12      5377032.78       3497220.9      5377035.76
#Sta/Elev= 13
       0   351.8   1.853   351.2    3.46  351.14   5.933  349.47   6.172  349.24
   6.262  349.21   6.833  349.25   6.916  349.25   7.499  349.41   7.869  349.48
   7.879  349.48  10.124  350.71  14.404  350.86
#Mann= 3 , 0 , 0
       0     .05       0   5.933     .04       0   7.879     .05       0
Bank Sta=5.933,7.879
XS Rating Curve= 0 ,0
Exp/Cntr=0.3,0.1

Type RM Length L Ch R = 1 ,9       ,35.28,35.28,35.28
XS GIS Cut Line= 6
      3497210.75      5376985.61      3497210.15      5376985.95
      3497208.02      5376985.82      3497206.66      5376986.14
      3497204.53      5376986.12      3497202.15      5376986.66
#Sta/Elev= 12
       0  350.42     .69  350.31   2.824  349.42   2.986   349.1   3.006   349.1
   3.617  348.92   3.653  348.93   4.361  348.95   4.472  349.26   4.482  349.26
   6.483  350.48   8.924  350.58
#Mann= 3 , 0 , 0
       0     .05       0   2.824     .04       0   4.482     .05       0
Bank Sta=2.824,4.482
XS Rating Curve= 0 ,0
Exp/Cntr=0.3,0.1

Type RM Length L Ch R = 1 ,8       ,28.16,28.16,28.16
XS GIS Cut Line= 6
      3497203.21      5376950.72      3497200.03      5376951.22
      3497198.38      5376951.65      3497198.18       5376951.9
      3497196.74       5376952.2      3497193.26      5376953.12
#Sta/Elev= 13
       0  350.33    .982  350.19   3.219  349.26   3.508  349.08   3.559  348.83
   4.136   348.8   4.197  348.79   4.735  348.86   4.925  349.07   5.145  349.33
   5.259  349.47    6.73   350.3   10.33  350.45
#Mann= 3 , 0 , 0
       0     .05       0   3.219     .04       0   5.145     .05       0
Bank Sta=3.219,5.145
XS Rating Curve= 0 ,0
Exp/Cntr=0.3,0.1

Type RM Length L Ch R = 1 ,7       ,74.03,74.03,74.03
XS GIS Cut Line= 6
      3497201.92      5376923.52      3497197.22      5376923.73
      3497194.69      5376924.18        3497194.      5376924.13
      3497191.65      5376924.64      3497188.33      5376925.07
#Sta/Elev= 13
       0  350.79   4.705  350.22   6.939  349.16   7.682  349.02   7.692  348.99
   7.994  348.74   8.285   348.7   8.851  348.81   8.961  348.96   9.153  349.25
   9.385  349.63  10.423  350.13  13.771  350.35
#Mann= 3 , 0 , 0
       0     .05       0   6.939     .04       0   9.153     .05       0
Bank Sta=6.939,9.153
XS Rating Curve= 0 ,0
Exp/Cntr=0.3,0.1

Type RM Length L Ch R = 1 ,6       ,64.65,64.65,64.65
XS GIS Cut Line= 6
      3497198.89      5376850.66      3497193.84      5376850.09
      3497190.98      5376849.89       3497190.7       5376849.8
      3497189.49      5376849.78      3497185.03      5376848.55
#Sta/Elev= 10
       0  350.52   5.082  350.03   7.949  348.69   8.243   348.6   8.253   348.6
   8.853  348.38   9.466   348.6   9.743  349.07  10.792   349.8    14.1   349.9
#Mann= 3 , 0 , 0
       0     .05       0   7.949     .04       0   9.743     .05       0
Bank Sta=7.949,9.743
XS Rating Curve= 0 ,0
Exp/Cntr=0.3,0.1

Type RM Length L Ch R = 1 ,5       ,86.63,86.63,86.63
XS GIS Cut Line= 6
      3497221.47      5376795.12       3497217.1      5376793.56
      3497215.12       5376792.5      3497213.15      5376791.84
      3497210.47      5376791.36      3497209.84      5376791.76
#Sta/Elev= 13
       0   349.8    4.64  349.69   6.886  348.65   7.066  348.48   7.462  348.23
   7.923   348.2   8.299  348.17   8.787  348.35   8.879  348.49   8.991  348.71
  10.735  349.52  11.719  349.68  12.466  349.67
#Mann= 3 , 0 , 0
       0     .05       0   6.886     .04       0   8.991     .05       0
Bank Sta=6.886,8.991
XS Rating Curve= 0 ,0
Exp/Cntr=0.3,0.1

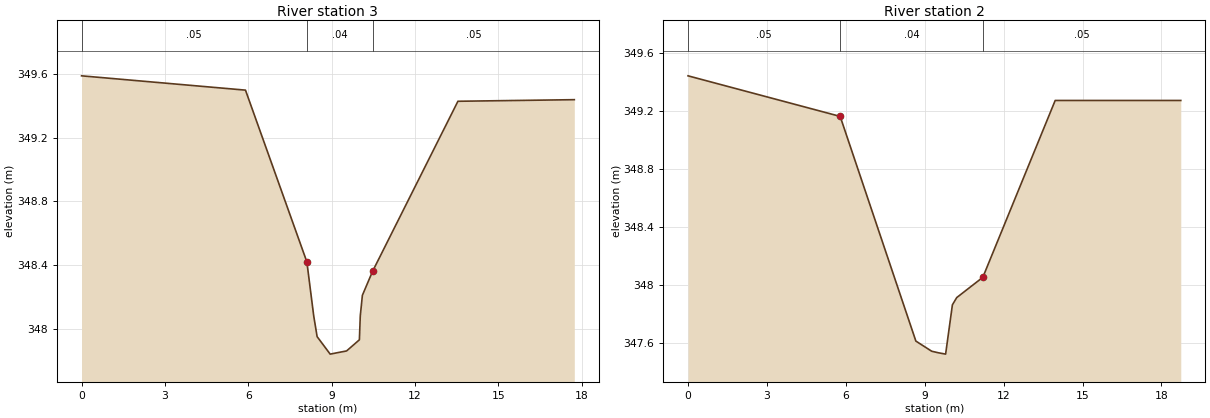
Type RM Length L Ch R = 1 ,3       ,60.81,60.81,60.81
XS GIS Cut Line= 6
       3497253.3      5376712.73       3497245.3      5376714.05
      3497245.09      5376714.18      3497243.45       5376714.2
      3497239.95      5376714.75      3497235.89      5376715.78
#Sta/Elev= 14
       0  349.59   5.899   349.5   8.108  348.42   8.355  348.08   8.477  347.95
   8.947  347.84   9.237  347.85   9.537  347.86   9.998  347.93   10.03  348.08
  10.106  348.21  10.471  348.36  13.544  349.43  17.732  349.44
#Mann= 3 , 0 , 0
       0     .05       0   8.108     .04       0  10.471     .05       0
Bank Sta=8.108,10.471
XS Rating Curve= 0 ,0
Exp/Cntr=0.3,0.1

Type RM Length L Ch R = 1 ,2       ,57.96,57.96,57.96
XS GIS Cut Line= 6
      3497229.02      5376657.22      3497220.79      5376659.92
       3497220.4      5376659.89      3497220.26      5376660.08
      3497219.97      5376660.04      3497211.58        5376663.
#Sta/Elev= 11
       0  349.44   5.785  349.16   8.663  347.61   9.265  347.54   9.501  347.53
   9.794  347.52  10.052  347.86  10.216  347.91  11.209  348.05   13.96  349.27
  18.735  349.27
#Mann= 3 , 0 , 0
       0     .05       0   5.785     .04       0  11.209     .05       0
Bank Sta=5.785,11.209
XS Rating Curve= 0 ,0
Exp/Cntr=0.3,0.1

River Reach=Ammer           ,LowerAmmer
Reach XY= 11
3497218.371753315376606.844357233497219.307558295376606.01864695
3497248.059214885376576.910359173497294.478214125376559.22693089
3497333.634376755376545.017033163497363.948825235376531.28079869
3497384.158457555376522.439084553497405.479999955376513.32999987
3497428.998579275376508.702850083497449.208205675376510.59750312
3497469.102062495376513.75525817