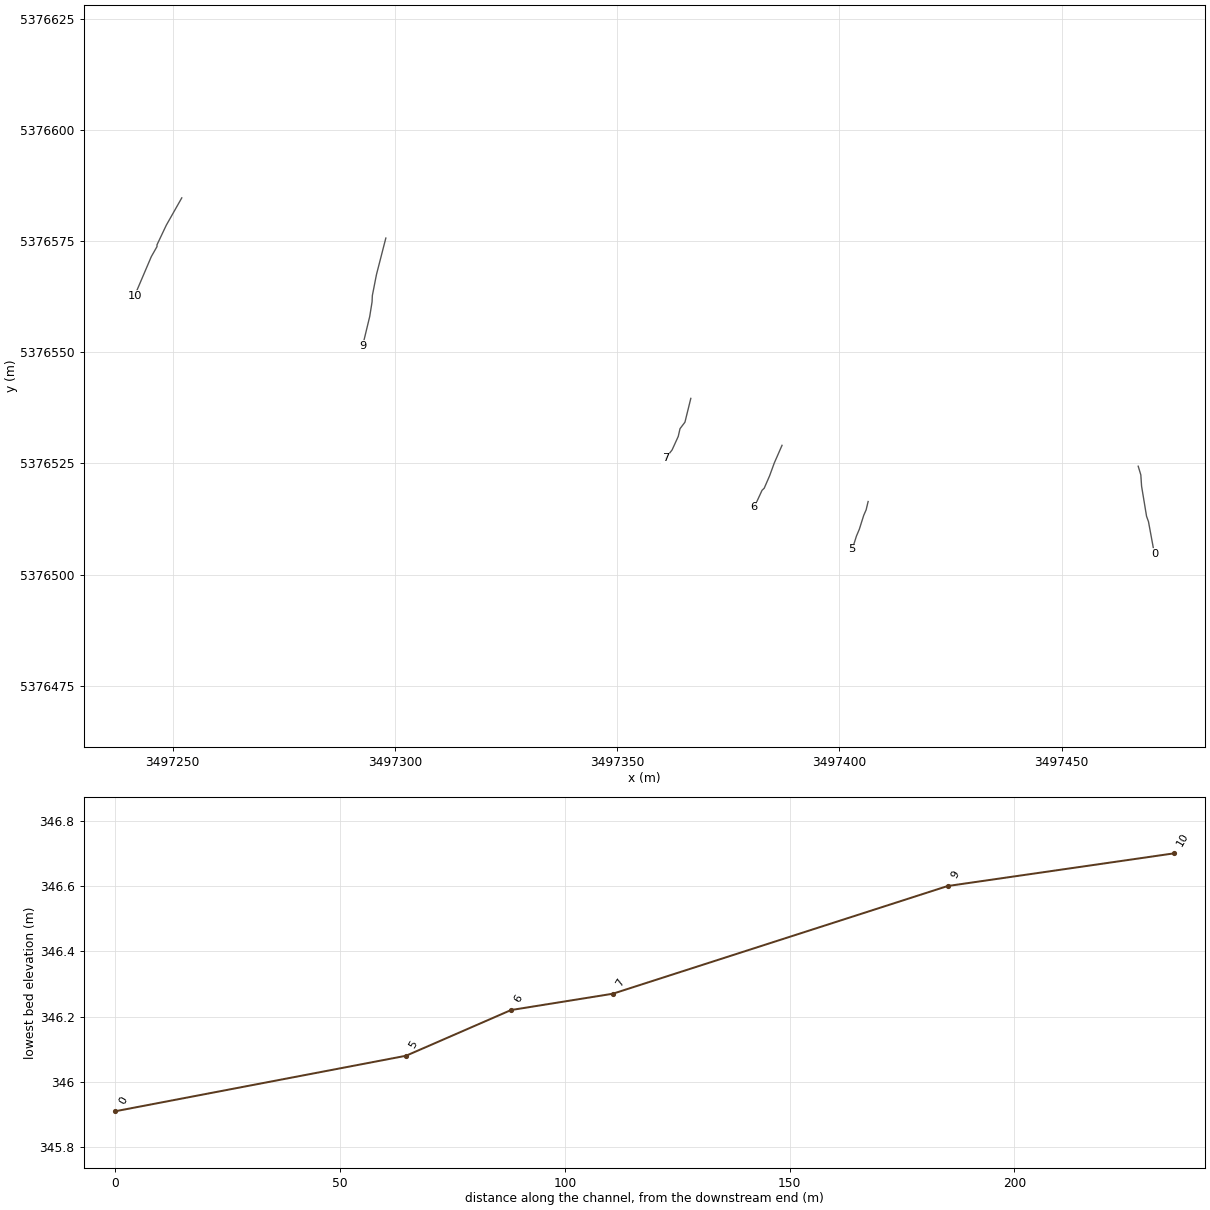
HEC-RAS study Amm_final.prj: Amm_final

--- Amm_final.g04 (geometry) --- (continued)

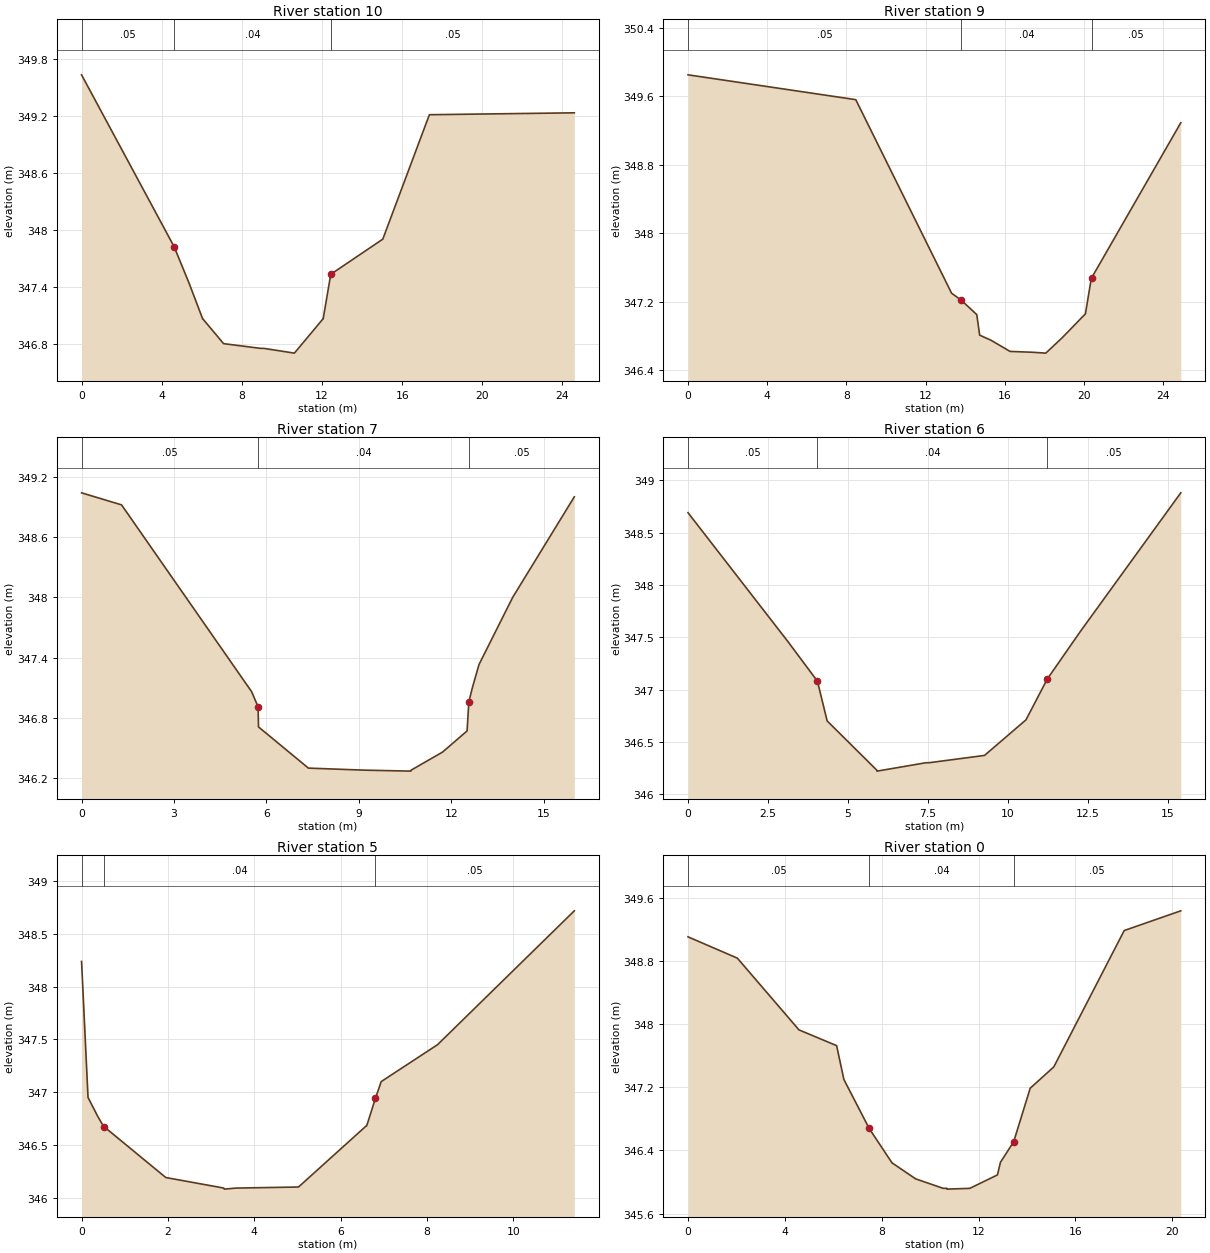
Type RM Length L Ch R = 1 ,10      ,50.3,50.3,50.3
XS GIS Cut Line= 6
      3497252.05      5376584.75      3497248.57      5376578.61
      3497246.47      5376574.18      3497246.48       5376573.8
       3497245.2      5376571.54      3497241.45      5376562.75
#Sta/Elev= 15
       0  349.63   4.621  347.82   5.379  347.43   6.045  347.06   6.055  347.06
   7.088   346.8   8.935  346.75   9.096  346.75  10.622   346.7  12.047  347.06
  12.057  347.06  12.437  347.53  15.034   347.9  17.358  349.21  24.591  349.23
#Mann= 3 , 0 , 0
       0     .05       0   4.621     .04       0  12.437     .05       0
Bank Sta=4.621,12.437
XS Rating Curve= 0 ,0
Exp/Cntr=0.3,0.1

Type RM Length L Ch R = 1 ,9       ,74.49,74.49,74.49
XS GIS Cut Line= 6
      3497297.96      5376575.71      3497295.85       5376567.5
      3497294.92      5376562.75      3497294.86      5376561.34
      3497294.33      5376558.05      3497292.73      5376551.43
#Sta/Elev= 16
       0  349.85   8.477  349.56  13.317   347.3  13.797  347.22  14.591  347.05
  14.737  346.81  15.314  346.75  16.273  346.62  17.408  346.61  18.079   346.6
  18.908  346.78  20.085  347.06  20.095  347.08  20.383  347.48  20.397  347.48
  24.899  349.29
#Mann= 3 , 0 , 0
       0     .05       0  13.797     .04       0  20.397     .05       0
Bank Sta=13.797,20.397
XS Rating Curve= 0 ,0
Exp/Cntr=0.3,0.1

Type RM Length L Ch R = 1 ,7       ,22.64,22.64,22.64
XS GIS Cut Line= 6
      3497366.57      5376539.64      3497365.25      5376534.29
      3497364.14      5376532.82      3497363.74      5376531.08
      3497362.36      5376528.053497360.895099785376526.17128434
#Sta/Elev= 16
       0  349.04   1.299  348.92   5.524  347.06   5.732  346.91   5.746  346.71
   7.366   346.3   9.152  346.28  10.693  346.27  10.703  346.28  11.724  346.46
  12.518  346.67  12.576  346.96   12.69   347.1  12.904  347.33      14     348
      16     349
#Mann= 3 , 0 , 0
       0     .05       0   5.732     .04       0  12.576     .05       0
Bank Sta=5.732,12.576
XS Rating Curve= 0 ,0
Exp/Cntr=0.3,0.1

Type RM Length L Ch R = 1 ,6       ,23.35,23.35,23.35
XS GIS Cut Line= 6
      3497387.09      5376529.08      3497385.35      5376525.11
      3497384.29      5376522.21      3497383.08      5376519.43
       3497382.6      5376518.97      3497380.85      5376515.18
#Sta/Elev= 13
       0  348.69   3.119  347.46   4.046  347.08    4.35   346.7     5.9  346.23
    5.91  346.22   7.436   346.3   7.531   346.3    9.27  346.37  10.567  346.71
  11.232   347.1  12.279  347.56  15.407  348.88
#Mann= 3 , 0 , 0
       0     .05       0   4.046     .04       0  11.232     .05       0
Bank Sta=4.046,11.232
XS Rating Curve= 0 ,0
Exp/Cntr=0.3,0.1

Type RM Length L Ch R = 1 ,5       ,64.66,64.66,64.66
XS GIS Cut Line= 6
      3497406.46      5376516.44      3497406.01      5376514.56
      3497405.47      5376513.33      3497404.48       5376510.2
      3497403.84      5376508.69      3497402.88      5376505.67
#Sta/Elev= 16
       0  348.24     .15  346.95    .375  346.77    .518  346.67    .528  346.67
   1.952  346.19   3.296  346.09   3.306  346.08   3.581  346.09   5.026   346.1
   6.596  346.68   6.606  346.68   6.808  346.94   6.942   347.1   8.247  347.45
  11.416  348.72
#Mann= 3 , 0 , 0
       0     .05       0    .528     .04       0   6.808     .05       0
Bank Sta=0.528,6.808
XS Rating Curve= 0 ,0
Exp/Cntr=0.3,0.1

Type RM Length L Ch R = 1 ,0       ,0,0,0
XS GIS Cut Line= 6
      3497467.22      5376524.38      3497467.81      5376522.43
      3497467.98      5376519.89       3497469.1      5376513.11
      3497469.53      5376511.92      3497470.87      5376504.67
#Sta/Elev= 20
       0  349.11   2.037  348.84   4.583  347.93   6.138  347.73   6.439   347.3
   7.483  346.68   8.432  346.24   8.442  346.24   9.404  346.04  10.537  345.92
   10.69  345.92    10.7  345.91  11.638  345.92   12.78  346.09  12.904  346.25
   13.45  346.51  14.134  347.19  15.108  347.46  18.017  349.19  20.353  349.44
#Mann= 3 , 0 , 0
       0     .05       0   7.483     .04       0   13.45     .05       0
Bank Sta=7.483,13.45
XS Rating Curve= 0 ,0
Exp/Cntr=0.3,0.1
LCMann Table=0

Chan Stop Cuts=-1
Use User Specified Reach Order=0
Composite Channel Slope=5